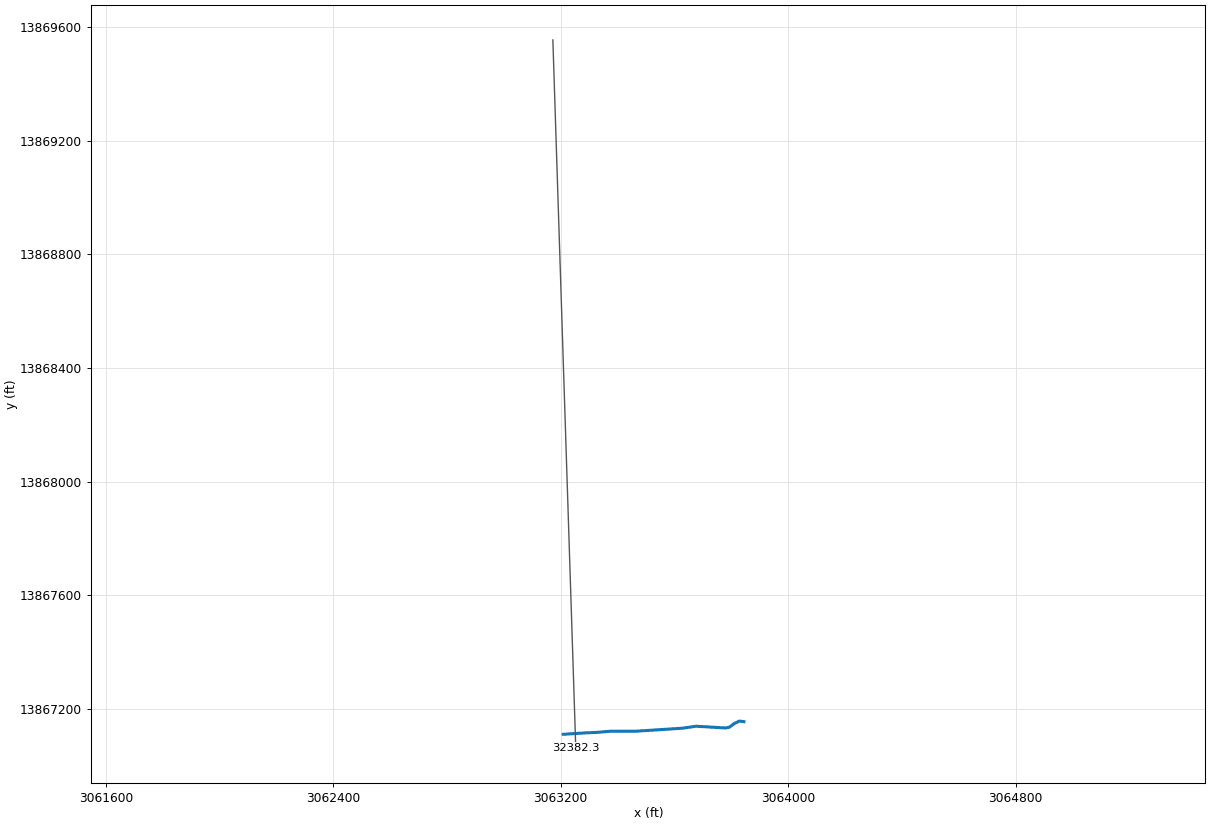
--- E115-00-00.prj (project) ---

Proj Title=E115-00-00
Current Plan=p01
Default Exp/Contr=.3,.1
English Units
Geom File=g01
Flow File=f01
Flow File=f02
Plan File=p01
Plan File=p02
Y Axis Title=Elevation
X Axis Title(PF)=Main Channel Distance
X Axis Title(XS)=Station
BEGIN DESCRIPTION:
HCFCD MODEL SUMMARY METADATA
The purpose of this summary is to document the high points of hydrologic and hydraulic models filed within the HCFCD Model and Map Management (M3) system.  The document includes references to the project that prompted the creation or update of the model.
DESCRIPTION OF PROJECT:
The following model was the hydraulic model which represented the effective condition of Harris County's watersheds.
PURPOSE OF PROJECT:
Development of effective models to support the National Flood Insurance Program.
HCFCD Watershed Unit ID: E
M3 Study Identifier: 2007_Effective_E
Engineer: HCFCD
Project Name: EffectiveFEMA Study for watershed White Oak Bayou (E)
Study Completion Date: 6/18/2007
FEMA Case Number: [No Data]
FEMA Approval Date: [No Date in Database]
Vertical Datum: NAVD 1988
Datum Note: 2001 ADJ
HYDRAULICS
HCFCD Unit No.:  E115-00-00
Hydraulic Program Name: HEC-RAS
Hydraulic Program Version: 3.0.1
Steady Hydraulic Model: Yes
Unsteady Hydraulic Model: No
Update1:
The effective FEMA hydraulic model for unit number E115-00-00 has been updated by FEMA LOMR 15-06-0275P with an effective date of 11/13/2015.
END DESCRIPTION:
DSS Export Rating Curves= 0
DSS Export Rating Curve Sorted= 0
DSS Export Volume Flow Curves= 0
DXF OffsetX= 0
DXF OffsetY= 0
DXF ScaleX= 1
DXF ScaleY= 10

--- E115-00-00.p01 (plan) ---

Plan Title=FEMA Effective Multi-Profile 2015
Version=Version 3.0.1  May 2012
Short Identifier=Eff+LOMR MP
Simulation Date=01/01/1999,0015,01/04/1999,0000
Geom File=g01
Flow File=f01
Subcritical Flow
K Sum by GR= 0
Std Step Tol= 0.01
Critical Tol= 0.01
Num of Std Step Trials= 20
Max Error Tol= 0.3
Flow Tol Ratio= 0.001
Split Flow NTrial= 30
Split Flow Tol= 0.02
Split Flow Ratio= 0.02
Log Output Level= 0
Friction Slope Method= 1
Unsteady Friction Slope Method= 2
Parabolic Critical Depth
Global Vel Dist= 1 , 1 , 1
Vel Dist Location=E115-00-00      ,E115-00-00_0008 ,32382.3 , 1 , 1 , 1
Vel Dist Location=E115-00-00      ,E115-00-00_0008 ,32282.3 , 1 , 1 , 1
Vel Dist Location=E115-00-00      ,E115-00-00_0008 ,32267.5 , 1 , 1 , 1
Vel Dist Location=E115-00-00      ,E115-00-00_0008 ,32234.4 , 1 , 1 , 1
Vel Dist Location=E115-00-00      ,E115-00-00_0008 ,32088.3 , 1 , 1 , 1
Vel Dist Location=E115-00-00      ,E115-00-00_0008 ,31967.0 , 1 , 1 , 1
Vel Dist Location=E115-00-00      ,E115-00-00_0008 ,31836.0 , 1 , 1 , 1
Vel Dist Location=E115-00-00      ,E115-00-00_0008 ,31683.4 , 1 , 1 , 1
Vel Dist Location=E115-00-00      ,E115-00-00_0008 ,31559.8 , 1 , 1 , 1
Vel Dist Location=E115-00-00      ,E115-00-00_0008 ,31545.6 , 1 , 1 , 1
Vel Dist Location=E115-00-00      ,E115-00-00_0008 ,31512.4 , 1 , 1 , 1
Vel Dist Location=E115-00-00      ,E115-00-00_0008 ,31413.3 , 1 , 1 , 1
Vel Dist Location=E115-00-00      ,E115-00-00_0008 ,31303.0 , 1 , 1 , 1
Vel Dist Location=E115-00-00      ,E115-00-00_0008 ,31210.3 , 1 , 1 , 1
Vel Dist Location=E115-00-00      ,E115-00-00_0008 ,31186.8 , 1 , 1 , 1
Vel Dist Location=E115-00-00      ,E115-00-00_0008 ,31163.3 , 1 , 1 , 1
Vel Dist Location=E115-00-00      ,E115-00-00_0008 ,31058.5 , 1 , 1 , 1
Vel Dist Location=E115-00-00      ,E115-00-00_0008 ,30876.1 , 1 , 1 , 1
Vel Dist Location=E115-00-00      ,E115-00-00_0008 ,30772.2 , 1 , 1 , 1
Vel Dist Location=E115-00-00      ,E115-00-00_0008 ,30744.2 , 1 , 1 , 1
Vel Dist Location=E115-00-00      ,E115-00-00_0008 ,30716.2 , 1 , 1 , 1
Vel Dist Location=E115-00-00      ,E115-00-00_0008 ,30620.  , 1 , 1 , 1
Vel Dist Location=E115-00-00      ,E115-00-00_0008 ,29947.0 , 1 , 1 , 1
Vel Dist Location=E115-00-00      ,E115-00-00_0008 ,29455.4 , 1 , 1 , 1
Vel Dist Location=E115-00-00      ,E115-00-00_0008 ,29360.2 , 1 , 1 , 1
Vel Dist Location=E115-00-00      ,E115-00-00_0008 ,29314.2 , 1 , 1 , 1
Vel Dist Location=E115-00-00      ,E115-00-00_0008 ,29268.2 , 1 , 1 , 1
Vel Dist Location=E115-00-00      ,E115-00-00_0008 ,29137.9 , 1 , 1 , 1
Vel Dist Location=E115-00-00      ,E115-00-00_0008 ,28685.1 , 1 , 1 , 1
Vel Dist Location=E115-00-00      ,E115-00-00_0008 ,28586.7 , 1 , 1 , 1
Vel Dist Location=E115-00-00      ,E115-00-00_0008 ,28566.0 , 1 , 1 , 1
Vel Dist Location=E115-00-00      ,E115-00-00_0008 ,28545.6 , 1 , 1 , 1
Vel Dist Location=E115-00-00      ,E115-00-00_0008 ,28447.5 , 1 , 1 , 1
Vel Dist Location=E115-00-00      ,E115-00-00_0008 ,28126.  , 1 , 1 , 1
Vel Dist Location=E115-00-00      ,E115-00-00_0008 ,28025.6 , 1 , 1 , 1
Vel Dist Location=E115-00-00      ,E115-00-00_0008 ,28003.6 , 1 , 1 , 1
Vel Dist Location=E115-00-00      ,E115-00-00_0008 ,27981.6 , 1 , 1 , 1
Vel Dist Location=E115-00-00      ,E115-00-00_0008 ,27878.3 , 1 , 1 , 1
Vel Dist Location=E115-00-00      ,E115-00-00_0008 ,27792.7 , 1 , 1 , 1
Vel Dist Location=E115-00-00      ,E115-00-00_0008 ,27694.0 , 1 , 1 , 1
Vel Dist Location=E115-00-00      ,E115-00-00_0008 ,27574.0 , 1 , 1 , 1
Vel Dist Location=E115-00-00      ,E115-00-00_0008 ,27466.2 , 1 , 1 , 1
Vel Dist Location=E115-00-00      ,E115-00-00_0008 ,26924.0 , 1 , 1 , 1
Vel Dist Location=E115-00-00      ,E115-00-00_0008 ,26768.1 , 1 , 1 , 1
Vel Dist Location=E115-00-00      ,E115-00-00_0008 ,26731.1 , 1 , 1 , 1
Vel Dist Location=E115-00-00      ,E115-00-00_0008 ,26694.1 , 1 , 1 , 1
Vel Dist Location=E115-00-00      ,E115-00-00_0008 ,26592.7 , 1 , 1 , 1
Vel Dist Location=E115-00-00      ,E115-00-00_0008 ,26206.4 , 1 , 1 , 1
Vel Dist Location=E115-00-00      ,E115-00-00_0008 ,25817.  , 1 , 1 , 1
Vel Dist Location=E115-00-00      ,E115-00-00_0008 ,25717.2 , 1 , 1 , 1
Vel Dist Location=E115-00-00      ,E115-00-00_0008 ,25700.7 , 1 , 1 , 1
Vel Dist Location=E115-00-00      ,E115-00-00_0008 ,25676.2 , 1 , 1 , 1
Vel Dist Location=E115-00-00      ,E115-00-00_0008 ,25569.5 , 1 , 1 , 1
Vel Dist Location=E115-00-00      ,E115-00-00_0008 ,25168.3 , 1 , 1 , 1
Vel Dist Location=E115-00-00      ,E115-00-00_0008 ,25073.7 , 1 , 1 , 1
Vel Dist Location=E115-00-00      ,E115-00-00_0008 ,25046.2 , 1 , 1 , 1
Vel Dist Location=E115-00-00      ,E115-00-00_0008 ,25018.7 , 1 , 1 , 1
Vel Dist Location=E115-00-00      ,E115-00-00_0008 ,24912.8 , 1 , 1 , 1
Vel Dist Location=E115-00-00      ,E115-00-00_0008 ,24695.0 , 1 , 1 , 1
Vel Dist Location=E115-00-00      ,E115-00-00_0008 ,24323.  , 1 , 1 , 1
Vel Dist Location=E115-00-00      ,E115-00-00_0008 ,24223.1 , 1 , 1 , 1
Vel Dist Location=E115-00-00      ,E115-00-00_0008 ,24166.1 , 1 , 1 , 1
Vel Dist Location=E115-00-00      ,E115-00-00_0008 ,24109.1 , 1 , 1 , 1
Vel Dist Location=E115-00-00      ,E115-00-00_0008 ,24010.9 , 1 , 1 , 1
Vel Dist Location=E115-00-00      ,E115-00-00_0008 ,23509.6 , 1 , 1 , 1
Vel Dist Location=E115-00-00      ,E115-00-00_0008 ,23119.4 , 1 , 1 , 1
Vel Dist Location=E115-00-00      ,E115-00-00_0008 ,22950   , 1 , 1 , 1
Vel Dist Location=E115-00-00      ,E115-00-00_0008 ,22930.4 , 1 , 1 , 1
Vel Dist Location=E115-00-00      ,E115-00-00_0008 ,22903.4 , 1 , 1 , 1
Vel Dist Location=E115-00-00      ,E115-00-00_0008 ,22749.1 , 1 , 1 , 1
Vel Dist Location=E115-00-00      ,E115-00-00_0008 ,22580.1 , 1 , 1 , 1
Vel Dist Location=E115-00-00      ,E115-00-00_0008 ,22469.6 , 1 , 1 , 1
Vel Dist Location=E115-00-00      ,E115-00-00_0008 ,22442.1 , 1 , 1 , 1
Vel Dist Location=E115-00-00      ,E115-00-00_0008 ,22414.6 , 1 , 1 , 1
Vel Dist Location=E115-00-00      ,E115-00-00_0008 ,22256.2 , 1 , 1 , 1
Vel Dist Location=E115-00-00      ,E115-00-00_0008 ,21928.0 , 1 , 1 , 1
Vel Dist Location=E115-00-00      ,E115-00-00_0008 ,20792.6 , 1 , 1 , 1
Vel Dist Location=E115-00-00      ,E115-00-00_0008 ,20146.5 , 1 , 1 , 1
Vel Dist Location=E115-00-00      ,E115-00-00_0008 ,18986.6 , 1 , 1 , 1
Vel Dist Location=E115-00-00      ,E115-00-00_0008 ,18689.2 , 1 , 1 , 1
Vel Dist Location=E115-00-00      ,E115-00-00_0008 ,18584.6 , 1 , 1 , 1
Vel Dist Location=E115-00-00      ,E115-00-00_0008 ,18556.1 , 1 , 1 , 1
Vel Dist Location=E115-00-00      ,E115-00-00_0008 ,18527.6 , 1 , 1 , 1
Vel Dist Location=E115-00-00      ,E115-00-00_0008 ,18433.3 , 1 , 1 , 1
Vel Dist Location=E115-00-00      ,E115-00-00_0008 ,17975.5 , 1 , 1 , 1
Vel Dist Location=E115-00-00      ,E115-00-00_0008 ,17701.5 , 1 , 1 , 1
Vel Dist Location=E115-00-00      ,E115-00-00_0008 ,17296.9 , 1 , 1 , 1
Vel Dist Location=E115-00-00      ,E115-00-00_0008 ,16862.9 , 1 , 1 , 1
Vel Dist Location=E115-00-00      ,E115-00-00_0008 ,16274.8 , 1 , 1 , 1
Vel Dist Location=E115-00-00      ,E115-00-00_0008 ,15262.0 , 1 , 1 , 1
Vel Dist Location=E115-00-00      ,E115-00-00_0008 ,14506.7 , 1 , 1 , 1
Vel Dist Location=E115-00-00      ,E115-00-00_0008 ,14412.3 , 1 , 1 , 1
Vel Dist Location=E115-00-00      ,E115-00-00_0008 ,14355.3 , 1 , 1 , 1
Vel Dist Location=E115-00-00      ,E115-00-00_0008 ,14289.1 , 1 , 1 , 1
Vel Dist Location=E115-00-00      ,E115-00-00_0008 ,14004.3 , 1 , 1 , 1
Vel Dist Location=E115-00-00      ,E115-00-00_0008 ,13336.3 , 1 , 1 , 1
Vel Dist Location=E115-00-00      ,E115-00-00_0008 ,12740.2 , 1 , 1 , 1
Vel Dist Location=E115-00-00      ,E115-00-00_0008 ,12552.6 , 1 , 1 , 1
Vel Dist Location=E115-00-00      ,E115-00-00_0008 ,12532.3 , 1 , 1 , 1
Vel Dist Location=E115-00-00      ,E115-00-00_0008 ,12512.0 , 1 , 1 , 1
Vel Dist Location=E115-00-00      ,E115-00-00_0008 ,12473.4 , 1 , 1 , 1
Vel Dist Location=E115-00-00      ,E115-00-00_0008 ,12430.4 , 1 , 1 , 1
Vel Dist Location=E115-00-00      ,E115-00-00_0008 ,12387.4 , 1 , 1 , 1
Vel Dist Location=E115-00-00      ,E115-00-00_0008 ,12246.2 , 1 , 1 , 1
Vel Dist Location=E115-00-00      ,E115-00-00_0008 ,11915.1 , 1 , 1 , 1
Vel Dist Location=E115-00-00      ,E115-00-00_0008 ,11812.3 , 1 , 1 , 1
Vel Dist Location=E115-00-00      ,E115-00-00_0008 ,11806.2 , 1 , 1 , 1
Vel Dist Location=E115-00-00      ,E115-00-00_0008 ,11752.8 , 1 , 1 , 1
Vel Dist Location=E115-00-00      ,E115-00-00_0008 ,11652.  , 1 , 1 , 1
Vel Dist Location=E115-00-00      ,E115-00-00_0008 ,11351.7 , 1 , 1 , 1
Vel Dist Location=E115-00-00      ,E115-00-00_0008 ,10368.6 , 1 , 1 , 1
Vel Dist Location=E115-00-00      ,E115-00-00_0008 ,9371.10 , 1 , 1 , 1
Vel Dist Location=E115-00-00      ,E115-00-00_0008 ,9275.2  , 1 , 1 , 1
Vel Dist Location=E115-00-00      ,E115-00-00_0008 ,9239.2  , 1 , 1 , 1
Vel Dist Location=E115-00-00      ,E115-00-00_0008 ,9203.2  , 1 , 1 , 1
Vel Dist Location=E115-00-00      ,E115-00-00_0008 ,9096.10 , 1 , 1 , 1
Vel Dist Location=E115-00-00      ,E115-00-00_0008 ,8157.3  , 1 , 1 , 1
Vel Dist Location=E115-00-00      ,E115-00-00_0008 ,7902.6  , 1 , 1 , 1
Vel Dist Location=E115-00-00      ,E115-00-00_0008 ,7751.6  , 1 , 1 , 1
Vel Dist Location=E115-00-00      ,E115-00-00_0008 ,7598.1  , 1 , 1 , 1
Vel Dist Location=E115-00-00      ,E115-00-00_0008 ,7444.6  , 1 , 1 , 1
Vel Dist Location=E115-00-00      ,E115-00-00_0008 ,7330.4  , 1 , 1 , 1
Vel Dist Location=E115-00-00      ,E115-00-00_0008 ,6852.1  , 1 , 1 , 1
Vel Dist Location=E115-00-00      ,E115-00-00_0008 ,6427.9  , 1 , 1 , 1
Vel Dist Location=E115-00-00      ,E115-00-00_0008 ,6273.6  , 1 , 1 , 1
Vel Dist Location=E115-00-00      ,E115-00-00_0008 ,6202.3  , 1 , 1 , 1
Vel Dist Location=E115-00-00      ,E115-00-00_0008 ,6116.7  , 1 , 1 , 1
Vel Dist Location=E115-00-00      ,E115-00-00_0008 ,6016.   , 1 , 1 , 1
Vel Dist Location=E115-00-00      ,E115-00-00_0008 ,5602.8  , 1 , 1 , 1
Vel Dist Location=E115-00-00      ,E115-00-00_0008 ,5016.7  , 1 , 1 , 1
Vel Dist Location=E115-00-00      ,E115-00-00_0008 ,4894.1  , 1 , 1 , 1
Vel Dist Location=E115-00-00      ,E115-00-00_0008 ,4863.6  , 1 , 1 , 1
Vel Dist Location=E115-00-00      ,E115-00-00_0008 ,4833.1  , 1 , 1 , 1
Vel Dist Location=E115-00-00      ,E115-00-00_0008 ,4713.5  , 1 , 1 , 1
Vel Dist Location=E115-00-00      ,E115-00-00_0008 ,4024.5  , 1 , 1 , 1
Vel Dist Location=E115-00-00      ,E115-00-00_0008 ,3095.3  , 1 , 1 , 1
Vel Dist Location=E115-00-00      ,E115-00-00_0008 ,2552.5  , 1 , 1 , 1
Vel Dist Location=E115-00-00      ,E115-00-00_0008 ,2460.5  , 1 , 1 , 1
Vel Dist Location=E115-00-00      ,E115-00-00_0008 ,2418.5  , 1 , 1 , 1
Vel Dist Location=E115-00-00      ,E115-00-00_0008 ,2376.5  , 1 , 1 , 1
Vel Dist Location=E115-00-00      ,E115-00-00_0008 ,2276.   , 1 , 1 , 1
Vel Dist Location=E115-00-00      ,E115-00-00_0008 ,2090.4  , 1 , 1 , 1
Vel Dist Location=E115-00-00      ,E115-00-00_0008 ,1698.   , 1 , 1 , 1
Vel Dist Location=E115-00-00      ,E115-00-00_0008 ,1598.5  , 1 , 1 , 1
Vel Dist Location=E115-00-00      ,E115-00-00_0008 ,1567.2  , 1 , 1 , 1
Vel Dist Location=E115-00-00      ,E115-00-00_0008 ,1563.1  , 1 , 1 , 1
Vel Dist Location=E115-00-00      ,E115-00-00_0008 ,1457.4  , 1 , 1 , 1
Vel Dist Location=E115-00-00      ,E115-00-00_0008 ,1304.   , 1 , 1 , 1
Vel Dist Location=E115-00-00      ,E115-00-00_0008 ,1203.8  , 1 , 1 , 1
Vel Dist Location=E115-00-00      ,E115-00-00_0008 ,1148.8  , 1 , 1 , 1
Vel Dist Location=E115-00-00      ,E115-00-00_0008 ,1093.8  , 1 , 1 , 1
Vel Dist Location=E115-00-00      ,E115-00-00_0008 ,1016.5  , 1 , 1 , 1
Vel Dist Location=E115-00-00      ,E115-00-00_0008 ,794.3   , 1 , 1 , 1
Global Log Level= 0
CheckData=True
Encroach Param=-1 ,0,0, 2
BEGIN DESCRIPTION:
FEMA Effective Floodway 2007 + LOMR 15-06-0275P
END DESCRIPTION:
Computation Interval=15MIN
Output Interval=30MIN
Run HTab= 1
Run UNet= 1
Run PostProcess= 1
UNET Theta= 1
UNET ZTol= 0.02
UNET ZSATol= 0.1
UNET MxIter= 20
UNET MaxInSteps= 20
UNET DtIC= 0
UNET DtMin= 0
UNET MaxCRTS= 20
UNET WFStab= 2
UNET SFStab= 1
UNET WFX= 1
UNET SFX= 1
UNET Convert EG Bridges=-1
UNET Use Existing IB Tables=-1
Instantaneous Interval=30MIN
DSS File=dss
Write IC File= 0
IC Time=0
Write Velocity= 1
Write Detailed= 0
Stage Flow Hydrograph=E115-00-00      ,E115-00-00_0008 ,32382.3
Stage Flow Hydrograph=E115-00-00      ,E115-00-00_0008 ,32282.3
Stage Flow Hydrograph=E115-00-00      ,E115-00-00_0008 ,32234.4
Stage Flow Hydrograph=E115-00-00      ,E115-00-00_0008 ,32088.3
Stage Flow Hydrograph=E115-00-00      ,E115-00-00_0008 ,31967.0
Stage Flow Hydrograph=E115-00-00      ,E115-00-00_0008 ,31836.0
Stage Flow Hydrograph=E115-00-00      ,E115-00-00_0008 ,31683.4
Stage Flow Hydrograph=E115-00-00      ,E115-00-00_0008 ,31559.8
Stage Flow Hydrograph=E115-00-00      ,E115-00-00_0008 ,31512.4
Stage Flow Hydrograph=E115-00-00      ,E115-00-00_0008 ,31413.3
Stage Flow Hydrograph=E115-00-00      ,E115-00-00_0008 ,31303.0
Stage Flow Hydrograph=E115-00-00      ,E115-00-00_0008 ,31210.3
Stage Flow Hydrograph=E115-00-00      ,E115-00-00_0008 ,31163.3
Stage Flow Hydrograph=E115-00-00      ,E115-00-00_0008 ,31058.5
Stage Flow Hydrograph=E115-00-00      ,E115-00-00_0008 ,30876.1
Stage Flow Hydrograph=E115-00-00      ,E115-00-00_0008 ,30772.2
Stage Flow Hydrograph=E115-00-00      ,E115-00-00_0008 ,30716.2
Stage Flow Hydrograph=E115-00-00      ,E115-00-00_0008 ,30620.
Stage Flow Hydrograph=E115-00-00      ,E115-00-00_0008 ,29947.0
Stage Flow Hydrograph=E115-00-00      ,E115-00-00_0008 ,29455.4
Stage Flow Hydrograph=E115-00-00      ,E115-00-00_0008 ,29360.2
Stage Flow Hydrograph=E115-00-00      ,E115-00-00_0008 ,29268.2
Stage Flow Hydrograph=E115-00-00      ,E115-00-00_0008 ,29137.9
Stage Flow Hydrograph=E115-00-00      ,E115-00-00_0008 ,28685.1
Stage Flow Hydrograph=E115-00-00      ,E115-00-00_0008 ,28586.7
Stage Flow Hydrograph=E115-00-00      ,E115-00-00_0008 ,28545.6
Stage Flow Hydrograph=E115-00-00      ,E115-00-00_0008 ,28447.5
Stage Flow Hydrograph=E115-00-00      ,E115-00-00_0008 ,28126.
Stage Flow Hydrograph=E115-00-00      ,E115-00-00_0008 ,28025.6
Stage Flow Hydrograph=E115-00-00      ,E115-00-00_0008 ,27981.6
Stage Flow Hydrograph=E115-00-00      ,E115-00-00_0008 ,27878.3
Stage Flow Hydrograph=E115-00-00      ,E115-00-00_0008 ,27792.7
Stage Flow Hydrograph=E115-00-00      ,E115-00-00_0008 ,27694.0
Stage Flow Hydrograph=E115-00-00      ,E115-00-00_0008 ,27574.0
Stage Flow Hydrograph=E115-00-00      ,E115-00-00_0008 ,27466.2
Stage Flow Hydrograph=E115-00-00      ,E115-00-00_0008 ,26924.0
Stage Flow Hydrograph=E115-00-00      ,E115-00-00_0008 ,26768.1
Stage Flow Hydrograph=E115-00-00      ,E115-00-00_0008 ,26694.1
Stage Flow Hydrograph=E115-00-00      ,E115-00-00_0008 ,26592.7
Stage Flow Hydrograph=E115-00-00      ,E115-00-00_0008 ,26206.4
Stage Flow Hydrograph=E115-00-00      ,E115-00-00_0008 ,25817.
Stage Flow Hydrograph=E115-00-00      ,E115-00-00_0008 ,25717.2
Stage Flow Hydrograph=E115-00-00      ,E115-00-00_0008 ,25676.2
Stage Flow Hydrograph=E115-00-00      ,E115-00-00_0008 ,25569.5
Stage Flow Hydrograph=E115-00-00      ,E115-00-00_0008 ,25168.3
Stage Flow Hydrograph=E115-00-00      ,E115-00-00_0008 ,25073.7
Stage Flow Hydrograph=E115-00-00      ,E115-00-00_0008 ,25018.7
Stage Flow Hydrograph=E115-00-00      ,E115-00-00_0008 ,24912.8
Stage Flow Hydrograph=E115-00-00      ,E115-00-00_0008 ,24695.0
Stage Flow Hydrograph=E115-00-00      ,E115-00-00_0008 ,24323.
Stage Flow Hydrograph=E115-00-00      ,E115-00-00_0008 ,24223.1
Stage Flow Hydrograph=E115-00-00      ,E115-00-00_0008 ,24109.1
Stage Flow Hydrograph=E115-00-00      ,E115-00-00_0008 ,24010.9
Stage Flow Hydrograph=E115-00-00      ,E115-00-00_0008 ,23509.6
Stage Flow Hydrograph=E115-00-00      ,E115-00-00_0008 ,23119.4
Stage Flow Hydrograph=E115-00-00      ,E115-00-00_0008 ,22950
Stage Flow Hydrograph=E115-00-00      ,E115-00-00_0008 ,22903.4
Stage Flow Hydrograph=E115-00-00      ,E115-00-00_0008 ,22749.1
Stage Flow Hydrograph=E115-00-00      ,E115-00-00_0008 ,22580.1
Stage Flow Hydrograph=E115-00-00      ,E115-00-00_0008 ,22469.6
Stage Flow Hydrograph=E115-00-00      ,E115-00-00_0008 ,22414.6
Stage Flow Hydrograph=E115-00-00      ,E115-00-00_0008 ,22256.2
Stage Flow Hydrograph=E115-00-00      ,E115-00-00_0008 ,21928.0
Stage Flow Hydrograph=E115-00-00      ,E115-00-00_0008 ,20792.6
Stage Flow Hydrograph=E115-00-00      ,E115-00-00_0008 ,20146.5
Stage Flow Hydrograph=E115-00-00      ,E115-00-00_0008 ,18986.6
Stage Flow Hydrograph=E115-00-00      ,E115-00-00_0008 ,18689.2
Stage Flow Hydrograph=E115-00-00      ,E115-00-00_0008 ,18584.6
Stage Flow Hydrograph=E115-00-00      ,E115-00-00_0008 ,18527.6
Stage Flow Hydrograph=E115-00-00      ,E115-00-00_0008 ,18433.3
Stage Flow Hydrograph=E115-00-00      ,E115-00-00_0008 ,17975.5
Stage Flow Hydrograph=E115-00-00      ,E115-00-00_0008 ,17701.5
Stage Flow Hydrograph=E115-00-00      ,E115-00-00_0008 ,17296.9
Stage Flow Hydrograph=E115-00-00      ,E115-00-00_0008 ,16862.9
Stage Flow Hydrograph=E115-00-00      ,E115-00-00_0008 ,16274.8
Stage Flow Hydrograph=E115-00-00      ,E115-00-00_0008 ,15262.0
Stage Flow Hydrograph=E115-00-00      ,E115-00-00_0008 ,14506.7
Stage Flow Hydrograph=E115-00-00      ,E115-00-00_0008 ,14412.3
Stage Flow Hydrograph=E115-00-00      ,E115-00-00_0008 ,14289.1
Stage Flow Hydrograph=E115-00-00      ,E115-00-00_0008 ,14004.3
Stage Flow Hydrograph=E115-00-00      ,E115-00-00_0008 ,13336.3
Stage Flow Hydrograph=E115-00-00      ,E115-00-00_0008 ,12740.2
Stage Flow Hydrograph=E115-00-00      ,E115-00-00_0008 ,12552.6
Stage Flow Hydrograph=E115-00-00      ,E115-00-00_0008 ,12512.0
Stage Flow Hydrograph=E115-00-00      ,E115-00-00_0008 ,12473.4
Stage Flow Hydrograph=E115-00-00      ,E115-00-00_0008 ,12387.4
Stage Flow Hydrograph=E115-00-00      ,E115-00-00_0008 ,12246.2
Stage Flow Hydrograph=E115-00-00      ,E115-00-00_0008 ,11915.1
Stage Flow Hydrograph=E115-00-00      ,E115-00-00_0008 ,11812.3
Stage Flow Hydrograph=E115-00-00      ,E115-00-00_0008 ,11752.8
Stage Flow Hydrograph=E115-00-00      ,E115-00-00_0008 ,11652.
Stage Flow Hydrograph=E115-00-00      ,E115-00-00_0008 ,11351.7
Stage Flow Hydrograph=E115-00-00      ,E115-00-00_0008 ,10368.6
Stage Flow Hydrograph=E115-00-00      ,E115-00-00_0008 ,9371.10
Stage Flow Hydrograph=E115-00-00      ,E115-00-00_0008 ,9275.2
Stage Flow Hydrograph=E115-00-00      ,E115-00-00_0008 ,9203.2
Stage Flow Hydrograph=E115-00-00      ,E115-00-00_0008 ,9096.10
Stage Flow Hydrograph=E115-00-00      ,E115-00-00_0008 ,8157.3
Stage Flow Hydrograph=E115-00-00      ,E115-00-00_0008 ,7902.6
Stage Flow Hydrograph=E115-00-00      ,E115-00-00_0008 ,7751.6
Stage Flow Hydrograph=E115-00-00      ,E115-00-00_0008 ,7444.6
Stage Flow Hydrograph=E115-00-00      ,E115-00-00_0008 ,7330.4
Stage Flow Hydrograph=E115-00-00      ,E115-00-00_0008 ,6852.1
Stage Flow Hydrograph=E115-00-00      ,E115-00-00_0008 ,6427.9
Stage Flow Hydrograph=E115-00-00      ,E115-00-00_0008 ,6273.6
Stage Flow Hydrograph=E115-00-00      ,E115-00-00_0008 ,6116.7
Stage Flow Hydrograph=E115-00-00      ,E115-00-00_0008 ,6016.
Stage Flow Hydrograph=E115-00-00      ,E115-00-00_0008 ,5602.8
Stage Flow Hydrograph=E115-00-00      ,E115-00-00_0008 ,5016.7
Stage Flow Hydrograph=E115-00-00      ,E115-00-00_0008 ,4894.1
Stage Flow Hydrograph=E115-00-00      ,E115-00-00_0008 ,4833.1
Stage Flow Hydrograph=E115-00-00      ,E115-00-00_0008 ,4713.5
Stage Flow Hydrograph=E115-00-00      ,E115-00-00_0008 ,4024.5
Stage Flow Hydrograph=E115-00-00      ,E115-00-00_0008 ,3095.3
Stage Flow Hydrograph=E115-00-00      ,E115-00-00_0008 ,2552.5
Stage Flow Hydrograph=E115-00-00      ,E115-00-00_0008 ,2460.5
Stage Flow Hydrograph=E115-00-00      ,E115-00-00_0008 ,2376.5
Stage Flow Hydrograph=E115-00-00      ,E115-00-00_0008 ,2276.
Stage Flow Hydrograph=E115-00-00      ,E115-00-00_0008 ,2090.4
Stage Flow Hydrograph=E115-00-00      ,E115-00-00_0008 ,1698.
Stage Flow Hydrograph=E115-00-00      ,E115-00-00_0008 ,1598.5
Stage Flow Hydrograph=E115-00-00      ,E115-00-00_0008 ,1563.1
Stage Flow Hydrograph=E115-00-00      ,E115-00-00_0008 ,1457.4
Stage Flow Hydrograph=E115-00-00      ,E115-00-00_0008 ,1304.
Stage Flow Hydrograph=E115-00-00      ,E115-00-00_0008 ,1203.8
Stage Flow Hydrograph=E115-00-00      ,E115-00-00_0008 ,1093.8
Stage Flow Hydrograph=E115-00-00      ,E115-00-00_0008 ,1016.5
Stage Flow Hydrograph=E115-00-00      ,E115-00-00_0008 ,794.3

--- E115-00-00.p02 (plan) ---

Plan Title=FEMA Effective Floodway 2015
Version=Version 3.0.1  May 2012
Short Identifier=Eff+LOMR FW
Geom File=g01
Flow File=f02
Subcritical Flow
K Sum by GR= 0
Std Step Tol= 0.01
Critical Tol= 0.01
Num of Std Step Trials= 20
Max Error Tol= 0.3
Flow Tol Ratio= 0.001
Split Flow NTrial= 30
Split Flow Tol= 0.02
Split Flow Ratio= 0.02
Log Output Level= 0
Friction Slope Method= 1
Unsteady Friction Slope Method= 2
Parabolic Critical Depth
Global Vel Dist= 0 , 0 , 0
Global Log Level= 0
CheckData=True
Encroach Param= 0 ,0,0, 2
Encroach River=E115-00-00
Encroach Reach=Reach - 1
Encroach Node=32382.3
       1  4977.6  5172.4
Encroach Node=32282.3
       1  4977.6  5172.4
Encroach Node=32267.5
       1  4977.6  5172.4
Encroach Node=32234.4
       1  4977.6  5172.4
Encroach Node=32088.3
       1  4974.1  5172.4
Encroach Node=31967.0
       1  4973.6    5150
Encroach Node=31888.1
       1  4973.6    5150
Encroach Node=31836.0
       1  4973.6    5150
Encroach Node=31683.4
       1  4974.2 5123.79
Encroach Node=31559.8
       1  4981.5  5118.6
Encroach Node=31545.6
       1  4981.5  5118.6
Encroach Node=31512.4
       1  4981.5    5186
Encroach Node=31413.3
       1 4981.47    5318
Encroach Node=31303.0
       1 4981.43    5318
Encroach Node=31210.3
       1  4981.4    5318
Encroach Node=31186.8
       1  4981.4    5318
Encroach Node=31163.3
       1  4981.4    5318
Encroach Node=31058.5
       1 4977.12    5318
Encroach Node=30876.1
       1  4941.3    5341
Encroach Node=30772.2
       1 4959.82    5334
Encroach Node=30744.2
       1 4959.82    5234
Encroach Node=30716.2
       1 4959.82    5234
Encroach Node=30620.
       1  4946.8  5040.2
Encroach Node=29947.0
       1    4969  5030.5
Encroach Node=29455.4
       1    4610 5025.81
Encroach Node=29360.2
       1    4610  5024.9
Encroach Node=29314.2
       1    4590  5024.9
Encroach Node=29268.2
       1    4570  5024.9
Encroach Node=29137.9
       1    4540 5024.38
Encroach Node=28685.1
       1    4215 5022.59
Encroach Node=28586.7
       1    4280  5022.2
Encroach Node=28566.0
       1    4280  5022.2
Encroach Node=28545.6
       1    4280  5022.2
Encroach Node=28447.5
       1    4310 5031.99
Encroach Node=28126.
       1  4920.6 5031.31
Encroach Node=28025.6
       1  4976.7  5021.1
Encroach Node=28003.6
       1  4976.7  5021.1
Encroach Node=27981.6
       1  4976.7  5021.1
Encroach Node=27878.3
       1 4974.19 5023.36
Encroach Node=27792.7
       1  4965.7 5025.24
Encroach Node=27694.0
       1  4969.7  5027.4
Encroach Node=27634.0
       1  4969.7  5027.4
Encroach Node=27574.0
       1  4969.7  5027.4
Encroach Node=27466.2
       1 4970.93  5020.6
Encroach Node=26924.0
       1  4977.1  5023.1
Encroach Node=26768.1
       1  4970.8  5026.9
Encroach Node=26731.1
       1  4970.8  5026.9
Encroach Node=26694.1
       1  4970.8  5026.9
Encroach Node=26592.7
       1 4971.92 5026.19
Encroach Node=26206.4
       1  4976.2  5023.5
Encroach Node=25817.
       1 4976.79 5020.24
Encroach Node=25717.2
       1  4977.6  5021.8
Encroach Node=25700.7
       1  4977.6  5021.8
Encroach Node=25676.2
       1  4977.6  5021.8
Encroach Node=25569.5
       1 4976.33 5020.43
Encroach Node=25168.3
       1  4979.3 5021.06
Encroach Node=25073.7
       1    4974  5021.6
Encroach Node=25046.2
       1    4974  5021.6
Encroach Node=25018.7
       1    4974  5021.6
Encroach Node=24912.8
       1  4967.2  5022.2
Encroach Node=24695.0
       1  4967.2  5022.2
Encroach Node=24323.
       1  4967.2  5022.2
Encroach Node=24223.1
       1  4963.4  5025.3
Encroach Node=24166.1
       1  4963.4  5025.3
Encroach Node=24109.1
       1  4963.4  5025.3
Encroach Node=24010.9
       1    4965 5021.87
Encroach Node=23509.6
       1    4965  5023.4
Encroach Node=23119.4
       1    4965  5023.4
Encroach Node=22950
       1 4960.07 5021.91
Encroach Node=22930.4
       1 4960.07 5028.93
Encroach Node=22903.4
       1 4967.08 5028.93
Encroach Node=22749.1
       1 4962.59 5024.51
Encroach Node=22580.1
       1 4965.67    5125
Encroach Node=22469.6
       1 4953.93    5185
Encroach Node=22442.1
       1 4953.92    5250
Encroach Node=22414.6
       1 4956.81    5250
Encroach Node=22256.2
       1    4900    5100
Encroach Node=21928.0
       1    4900    5100
Encroach Node=20792.6
       1    4900    5100
Encroach Node=20146.5
       1    4900    5100
Encroach Node=18986.6
       1    4800    5200
Encroach Node=18689.2
       1    4800    5200
Encroach Node=18584.6
       1    4800    5200
Encroach Node=18556.1
       1    4800    5200
Encroach Node=18527.6
       1  4877.9 5149.71
Encroach Node=18433.3
       1  4935.3  5055.3
Encroach Node=17975.5
       1    4936  5046.4
Encroach Node=17701.5
       1  4929.6  5119.6
Encroach Node=17296.9
       1  4933.3 5071.22
Encroach Node=16862.9
       1    4523    5250
Encroach Node=16274.8
       1    4450    5350
Encroach Node=15262.0
       1    4400    5400
Encroach Node=14506.7
       1    4500    5300
Encroach Node=14412.3
       1    4550    5200
Encroach Node=14355.3
       1    4600    5200
Encroach Node=14289.1
       1    4600    5200
Encroach Node=14004.3
       1    4600    5200
Encroach Node=13336.3
       1    4600    5200
Encroach Node=12740.2
       1    4737  5135.5
Encroach Node=12552.6
       1    4600    5400
Encroach Node=12532.3
       1    4600    5400
Encroach Node=12512.0
       1    4600    5400
Encroach Node=12473.4
       1    4700    5300
Encroach Node=12430.4
       1    4700    5300
Encroach Node=12387.4
       1    4700    5300
Encroach Node=12246.2
       1    4825    5175
Encroach Node=11915.1
       1 4938.01    5147
Encroach Node=11812.3
       1    4870    5130
Encroach Node=11806.2
       1    4870    5130
Encroach Node=11752.8
       1    4870 5042.18
Encroach Node=11652.
       1    4900    5047
Encroach Node=11351.7
       1 4806.05    5090
Encroach Node=10368.6
       1 4792.55 5192.55
Encroach Node=9371.10
       1 4798.15 5198.15
Encroach Node=9275.2
       1 4798.15 5198.15
Encroach Node=9239.2
       1 4798.15 5198.15
Encroach Node=9203.2
       1 4798.15 5198.15
Encroach Node=9096.10
       1 4798.15 5198.15
Encroach Node=8157.3
       1 4823.15 5163.15
Encroach Node=7902.6
       1    4856    5254
Encroach Node=7751.6
       1    4856    5254
Encroach Node=7598.1
       1    4856    5254
Encroach Node=7444.6
       1    4856  5085.7
Encroach Node=7330.4
       1    4856 5230.24
Encroach Node=6852.1
       1  4795.7    5175
Encroach Node=6427.9
       1 4718.68 5281.53
Encroach Node=6273.6
       1 4718.68 5281.53
Encroach Node=6202.3
       1 4718.68 5281.53
Encroach Node=6116.7
       1 4882.01 5281.53
Encroach Node=6016.
       1 4882.01 5103.01
Encroach Node=5602.8
       1 4780.08    5180
Encroach Node=5016.7
       1    4785 5303.06
Encroach Node=4894.1
       1    4730 5267.42
Encroach Node=4863.6
       1    4730 5267.42
Encroach Node=4833.1
       1    4730 5267.14
Encroach Node=4713.5
       1    4730 5225.52
Encroach Node=4024.5
       1    4830    5132
Encroach Node=3095.3
       1    4770 5077.75
Encroach Node=2552.5
       1    4930 5063.37
Encroach Node=2460.5
       1    4930 5052.75
Encroach Node=2418.5
       1    4930 5052.75
Encroach Node=2376.5
       1 4952.26 5045.38
Encroach Node=2276.
       1 4935.38  5059.6
Encroach Node=2090.4
       1  4918.3  5061.7
Encroach Node=1698.
       1    4935 5049.68
Encroach Node=1598.5
       1    4935 5057.47
Encroach Node=1567.2
       1    4935 5057.47
Encroach Node=1563.1
       1    4935 5042.93
Encroach Node=1457.4
       1  4915.5  5087.7
Encroach Node=1304.
       1  4915.5  5093.5
Encroach Node=1203.8
       1  4915.5  5090.9
Encroach Node=1148.8
       1  4915.5  5090.9
Encroach Node=1093.8
       1  4915.5  5090.9
Encroach Node=1016.5
       1  4909.2  5123.6
Encroach Node=794.3
       1  4916.7  5113.2
Encroach Reach=E115-00-00_0008
Encroach Node=32382.3
       1  4977.6  5172.4
Encroach Node=32282.3
       1  4977.6  5172.4
Encroach Node=32267.5
       1  4977.6  5172.4
Encroach Node=32234.4
       1  4977.6  5172.4
Encroach Node=32088.3
       1  4974.1  5172.4
Encroach Node=31967.0
       1  4973.6  5030.2
Encroach Node=31888.1
       1  4973.6    5150
Encroach Node=31836.0
       1  4973.6    5150
Encroach Reach=E115-00-00_0009
Encroach Node=27466.2
       1 4970.93  5020.6
Encroach Node=26924.0
       1  4977.1  5023.1
Encroach Node=26768.1
       1  4970.8  5026.9
Encroach Node=26731.1
       1  4970.8  5026.9
Encroach Node=26694.1
       1  4970.8  5026.9
Encroach Node=26592.7
       1 4971.92 5026.19
Encroach Node=26206.4
       1  4976.2  5023.5
Encroach Node=25817.
       1 4976.79 5020.24
Encroach Node=25717.2
       1  4977.6  5021.8
Encroach Node=25700.7
       1  4977.6  5021.8
Encroach Node=25676.2
       1  4977.6  5021.8
Encroach Node=25569.5
       1 4976.33 5020.43
Encroach Node=25168.3
       1  4979.3 5021.06
Encroach Node=25073.7
       1    4974  5021.6
Encroach Node=25046.2
       1    4974  5021.6
Encroach Node=25018.7
       1    4974  5021.6
Encroach Node=24912.8
       1  4967.2  5022.2
Encroach Node=24695.0
       1  4967.2  5022.2
Encroach Node=24323.
       1  4967.2  5022.2
Encroach Node=24223.1
       1  4963.4  5025.3
Encroach Node=24166.1
       1  4963.4  5025.3
Encroach Node=24109.1
       1  4963.4  5025.3
Encroach Node=24010.9
       1    4965 5021.87
Encroach Node=23509.6
       1    4965  5023.4
Encroach Node=23119.4
       1    4965  5023.4
Encroach Node=22950
       1 4960.07 5021.91
Encroach Node=22930.4
       1 4960.07 5028.93
Encroach Node=22903.4
       1 4967.08 5028.93
Encroach Node=22749.1
       1 4962.59 5024.51
Encroach Node=22580.1
       1 4965.67    5125
Encroach Node=22469.6
       1 4953.93    5185
Encroach Node=22442.1
       1 4953.92    5250
Encroach Node=22414.6
       1 4956.81    5250
Encroach Node=22256.2
       1    4900    5100
Encroach Node=21928.0
       1    4900    5100
Encroach Node=20792.6
       1    4900    5100
Encroach Node=20146.5
       1    4900    5100
Encroach Node=18986.6
       1    4800    5200
Encroach Node=18689.2
       1    4800    5200
Encroach Node=18584.6
       1    4800    5200
Encroach Node=18556.1
       1    4800    5200
Encroach Node=18527.6
       1  4877.9 5149.71
Encroach Node=18433.3
       1  4935.3  5055.3
Encroach Node=17975.5
       1    4936  5046.4
Encroach Node=17701.5
       1  4929.6  5119.6
Encroach Node=17296.9
       1  4933.3 5071.22
Encroach Node=16862.9
       1    4523    5250
Encroach Node=16274.8
       1    4450    5350
Encroach Node=15262.0
       1    4400    5400
Encroach Node=14506.7
       1    4500    5300
Encroach Node=14412.3
       1    4550    5200
Encroach Node=14355.3
       1    4600    5200
Encroach Node=14289.1
       1    4600    5200
Encroach Node=14004.3
       1    4600    5200
Encroach Node=13336.3
       1    4600    5200
Encroach Node=12740.2
       1    4737  5135.5
Encroach Node=12552.6
       1    4600    5400
Encroach Node=12532.3
       1    4600    5400
Encroach Node=12512.0
       1    4600    5400
Encroach Node=12473.4
       1    4700    5300
Encroach Node=12430.4
       1    4700    5300
Encroach Node=12387.4
       1    4700    5300
Encroach Node=12246.2
       1    4825    5175
Encroach Node=11915.1
       1 4938.01    5147
Encroach Node=11812.3
       1    4870    5130
Encroach Node=11806.2
       1    4870    5130
Encroach Node=11752.8
       1    4870 5042.18
Encroach Node=11652.
       1    4900    5047
Encroach Node=11351.7
       1 4806.05    5090
Encroach Node=10368.6
       1 4792.55 5192.55
Encroach Node=9371.10
       1 4798.15 5198.15
Encroach Node=9275.2
       1 4798.15 5198.15
Encroach Node=9239.2
       1 4798.15 5198.15
Encroach Node=9203.2
       1 4798.15 5198.15
Encroach Node=9096.10
       1 4798.15 5198.15
Encroach Node=8157.3
       1 4823.15 5163.15
Encroach Node=7902.6
       1    4856    5254
Encroach Node=7751.6
       1    4856    5254
Encroach Node=7598.1
       1    4856    5254
Encroach Node=7444.6
       1    4856  5085.7
Encroach Node=7330.4
       1    4856 5230.24
Encroach Node=6852.1
       1  4795.7    5175
Encroach Node=6427.9
       1 4718.68 5281.53
Encroach Node=6273.6
       1 4718.68 5281.53
Encroach Node=6202.3
       1 4718.68 5281.53
Encroach Node=6116.7
       1 4882.01 5281.53
Encroach Node=6016.
       1 4882.01 5103.01
Encroach Node=5602.8
       1 4780.08    5180
Encroach Node=5016.7
       1    4785 5303.06
Encroach Node=4894.1
       1    4730 5267.42
Encroach Node=4863.6
       1    4730 5267.42
Encroach Node=4833.1
       1    4730 5267.14
Encroach Node=4713.5
       1    4730 5225.52
Encroach Node=4024.5
       1    4830    5132
Encroach Node=3095.3
       1    4770 5077.75
Encroach Node=2552.5
       1    4930 5063.37
Encroach Node=2460.5
       1    4930 5052.75
Encroach Node=2418.5
       1    4930 5052.75
Encroach Node=2376.5
       1 4952.26 5045.38
Encroach Node=2276.
       1 4935.38  5059.6
Encroach Node=2090.4
       1  4918.3  5061.7
Encroach Node=1698.
       1    4935 5049.68
Encroach Node=1598.5
       1    4935 5057.47
Encroach Node=1567.2
       1    4935 5057.47
Encroach Node=1563.1
       1    4935 5042.93
Encroach Node=1457.4
       1  4915.5  5087.7
Encroach Node=1304.
       1  4915.5  5093.5
Encroach Node=1203.8
       1  4915.5  5090.9
Encroach Node=1148.8
       1  4915.5  5090.9
Encroach Node=1093.8
       1  4915.5  5090.9
Encroach Node=1016.5
       1  4909.2  5123.6
Encroach Node=794.3
       1  4916.7  5113.2
Encroach Reach=E115-00-00_0010
Encroach Node=31683.4
       1  4974.2 5123.79
Encroach Node=31559.8
       1  4981.5  5118.6
Encroach Node=31545.6
       1  4981.5  5118.6
Encroach Node=31512.4
       1  4981.5    5186
Encroach Node=31413.3
       1 4981.47    5318
Encroach Node=31303.0
       1 4981.43    5318
Encroach Node=31210.3
       1  4981.4    5318
Encroach Node=31186.8
       1  4981.4    5318
Encroach Node=31163.3
       1  4981.4    5318
Encroach Node=31058.5
       1 4977.12    5318
Encroach Node=30876.1
       1  4941.3    5341
Encroach Node=30772.2
       1 4959.82    5334
Encroach Node=30744.2
       1 4959.82    5234
Encroach Node=30716.2
       1 4959.82    5234
Encroach Node=30620.
       1  4946.8  5040.2
Encroach Node=29947.0
       1    4969  5030.5
Encroach Node=29455.4
       1    4610 5025.81
Encroach Node=29360.2
       1    4610  5024.9
Encroach Node=29314.2
       1    4590  5024.9
Encroach Node=29268.2
       1    4570  5024.9
Encroach Node=29137.9
       1    4540 5024.38
Encroach Node=28685.1
       1    4215 5022.59
Encroach Node=28586.7
       1    4280  5022.2
Encroach Node=28566.0
       1    4280  5022.2
Encroach Node=28545.6
       1    4280  5022.2
Encroach Node=28447.5
       1    4310 5031.99
Encroach Node=28126.
       1  4920.6 5031.31
Encroach Node=28025.6
       1  4976.7  5021.1
Encroach Node=28003.6
       1  4976.7  5021.1
Encroach Node=27981.6
       1  4976.7  5021.1
Encroach Node=27878.3
       1 4974.19 5023.36
Encroach Node=27792.7
       1  4965.7 5025.24
Encroach Node=27694.0
       1  4969.7  5027.4
Encroach Node=27634.0
       1  4969.7  5027.4
Encroach Node=27574.0
       1  4969.7  5027.4
Encroach River=GolfCourse
Encroach Reach=Split
Encroach Node=4319.499
       1  838.57 1242.89
Encroach Node=4152.239
       1     792 1210.41
Encroach Node=4090.019
       1  719.62 1214.36
Encroach Node=3570.969
       1  828.86 1123.65
Encroach Node=3375.425
       1  818.71 1086.44
Encroach Node=3189.31
       1  639.09  1032.5
Encroach Node=2966.023
       1  744.08 1101.53
Encroach Node=2746.428
       1  597.55 1036.38
Encroach Node=2237.353
       1  808.52  982.78
Encroach Node=1537.91
       1  848.92 1116.91
Encroach Node=1132.226
       1  873.54 1349.58
Encroach Node=963.1334
       1  724.21 1014.34
Encroach Node=675.0079
       1  609.06  818.08
Encroach Node=231.8512
       1   203.1  306.57
BEGIN DESCRIPTION:
FEMA Effective Floodway 2007 + LOMR 15-06-0275P
END DESCRIPTION:
Computation Interval=1HOUR
Output Interval=1HOUR
Run HTab= 0
Run UNet= 0
Run PostProcess= 0
UNET Theta= 1
UNET ZTol= 0.02
UNET ZSATol= 0.1
UNET MxIter= 20
UNET MaxInSteps= 20
UNET DtIC= 0
UNET DtMin= 0
UNET MaxCRTS= 20
UNET WFStab= 2
UNET SFStab= 1
UNET WFX= 1
UNET SFX= 1
UNET Convert EG Bridges=-1
UNET Use Existing IB Tables=-1
Instantaneous Interval=1HOUR
Write IC File= 0
IC Time=0
Write Velocity= 0
Write Detailed= 0

--- E115-00-00.f01 (steady flow) ---

Flow Title=FEMA Effective November 2015
Version=Version 3.0.1  May 2012
Number of Profiles= 4
Profile Names=10PCT_10yr, 2PCT_50yr, 1PCT_100yr, 0.2PCT_500yr
River Rch & RM=E115-00-00,E115-00-00_0008 ,32382.3
     840    1000    1100    1150
River Rch & RM=E115-00-00,E115-00-00_0008 ,31967.0
     900    1080    1200    1280
River Rch & RM=E115-00-00,E115-00-00_0008 ,31836.0
     410     400     350     180
River Rch & RM=E115-00-00,E115-00-00_0010 ,31683.4
     410     400     350     180
River Rch & RM=E115-00-00,E115-00-00_0010 ,31559.8
     490     520     500     400
River Rch & RM=E115-00-00,E115-00-00_0010 ,31210.3
     510     540     520     440
River Rch & RM=E115-00-00,E115-00-00_0010 ,30772.2
     580     600     600     600
River Rch & RM=E115-00-00,E115-00-00_0010 ,29360.2
     620     640     650     690
River Rch & RM=E115-00-00,E115-00-00_0010 ,28586.7
     650     670     680     760
River Rch & RM=E115-00-00,E115-00-00_0010 ,28025.6
     710     720     750     900
River Rch & RM=E115-00-00,E115-00-00_0009 ,27466.2
     710     720     750     900
River Rch & RM=E115-00-00,E115-00-00_0009 ,26924.0
    1240    1420    1660    2050
River Rch & RM=E115-00-00,E115-00-00_0009 ,26206.4
    1260    1440    1700    2080
River Rch & RM=E115-00-00,E115-00-00_0009 ,25073.7
    1320    1480    1790    2160
River Rch & RM=E115-00-00,E115-00-00_0009 ,24695.0
    1350    1500    1850    2200
River Rch & RM=E115-00-00,E115-00-00_0009 ,23509.6
    1950    2600    2900    3800
River Rch & RM=E115-00-00,E115-00-00_0009 ,20146.5
    3230    4690    5430    7540
River Rch & RM=E115-00-00,E115-00-00_0009 ,18986.6
    3327    4847    5616    7768
River Rch & RM=E115-00-00,E115-00-00_0009 ,18584.6
    3380    4860    5600    7770
River Rch & RM=E115-00-00,E115-00-00_0009 ,17975.5
    3630    4920    5520    7750
River Rch & RM=E115-00-00,E115-00-00_0009 ,15262.0
    3810    4960    5460    7740
River Rch & RM=E115-00-00,E115-00-00_0009 ,13336.3
    3970    4990    5420    7730
River Rch & RM=E115-00-00,E115-00-00_0009 ,11812.3
    4130    5030    5370    7720
River Rch & RM=E115-00-00,E115-00-00_0009 ,10368.6
    4250    5050    5340    7710
River Rch & RM=E115-00-00,E115-00-00_0009 ,9275.2
    4254    5052    5340    7714
River Rch & RM=E115-00-00,E115-00-00_0009 ,8157.3
    5270    6510    7060   10120
River Rch & RM=E115-00-00,E115-00-00_0009 ,6852.1
    5350    6610    7180   10270
River Rch & RM=E115-00-00,E115-00-00_0009 ,6273.6
    5530    6840    7470   10660
River Rch & RM=E115-00-00,E115-00-00_0009 ,4894.1
    5650    7000    7660   10920
River Rch & RM=E115-00-00,E115-00-00_0009 ,4024.5
    5780    7160    7870   11190
River Rch & RM=E115-00-00,E115-00-00_0009 ,3095.3
    5920    7350    8100   11500
River Rch & RM=E115-00-00,E115-00-00_0009 ,2090.4
    6230    7743    8598   12166
River Rch & RM=GolfCourse,Split           ,4319.499
     490     680     850    1100
River Rch & RM=GolfCourse,Split           ,4152.239
     490     680     850    1100
River Rch & RM=GolfCourse,Split           ,3570.969
     490     680     850    1100
River Rch & RM=GolfCourse,Split           ,2966.023
     490     680     850    1100
River Rch & RM=GolfCourse,Split           ,1132.226
     490     680     850    1100
River Rch & RM=GolfCourse,Split           ,963.1334
     490     680     850    1100
River Rch & RM=GolfCourse,Split           ,675.0079
     490     680     850    1100
River Rch & RM=GolfCourse,Split           ,231.8512
     490     680     850    1100
Boundary for River Rch & Prof#=E115-00-00,E115-00-00_0008 , 1
Up Type= 0
Dn Type= 0
Boundary for River Rch & Prof#=E115-00-00,E115-00-00_0008 , 2
Up Type= 0
Dn Type= 0
Boundary for River Rch & Prof#=E115-00-00,E115-00-00_0008 , 3
Up Type= 0
Dn Type= 0
Boundary for River Rch & Prof#=E115-00-00,E115-00-00_0008 , 4
Up Type= 0
Dn Type= 0
Boundary for River Rch & Prof#=E115-00-00,E115-00-00_0010 , 1
Up Type= 0
Dn Type= 3
Dn Slope=.001
Boundary for River Rch & Prof#=E115-00-00,E115-00-00_0010 , 2
Up Type= 0
Dn Type= 3
Dn Slope=.001
Boundary for River Rch & Prof#=E115-00-00,E115-00-00_0010 , 3
Up Type= 0
Dn Type= 3
Dn Slope=.001
Boundary for River Rch & Prof#=E115-00-00,E115-00-00_0010 , 4
Up Type= 0
Dn Type= 3
Dn Slope=.001
Boundary for River Rch & Prof#=E115-00-00,E115-00-00_0009 , 1
Up Type= 0
Dn Type= 3
Dn Slope=.001
Boundary for River Rch & Prof#=E115-00-00,E115-00-00_0009 , 2
Up Type= 0
Dn Type= 3
Dn Slope=.001
Boundary for River Rch & Prof#=E115-00-00,E115-00-00_0009 , 3
Up Type= 0
Dn Type= 3
Dn Slope=.001
Boundary for River Rch & Prof#=E115-00-00,E115-00-00_0009 , 4
Up Type= 0
Dn Type= 3
Dn Slope=.001
Boundary for River Rch & Prof#=GolfCourse,Split           , 1
Up Type= 0
Dn Type= 3
Dn Slope=.001
Boundary for River Rch & Prof#=GolfCourse,Split           , 2
Up Type= 0
Dn Type= 3
Dn Slope=.001
Boundary for River Rch & Prof#=GolfCourse,Split           , 3
Up Type= 0
Dn Type= 3
Dn Slope=.001
Boundary for River Rch & Prof#=GolfCourse,Split           , 4
Up Type= 0
Dn Type= 3
Dn Slope=.001
Observed WS=E115-00-00      ,E115-00-00_0008 ,794.3   , 0 ,62.68,64.76,65.58,68.35
DSS Import GetInterval= 0
DSS Import GetPeak= 0
DSS Import FillOption= 0

--- E115-00-00.f02 (steady flow) ---

Flow Title=Floodway
Version=Version 3.0.1  May 2012
Number of Profiles= 2
Profile Names=1PCT_100yr, 1PCTFloodway_100yrFW
River Rch & RM=E115-00-00,E115-00-00_0008 ,32382.3
    1100    1100
River Rch & RM=E115-00-00,E115-00-00_0008 ,31967.0
    1200    1200
River Rch & RM=E115-00-00,E115-00-00_0008 ,31836.0
     350     350
River Rch & RM=E115-00-00,E115-00-00_0010 ,31683.4
     350     350
River Rch & RM=E115-00-00,E115-00-00_0010 ,31559.8
     500     500
River Rch & RM=E115-00-00,E115-00-00_0010 ,31210.3
     520     520
River Rch & RM=E115-00-00,E115-00-00_0010 ,30772.2
     600     600
River Rch & RM=E115-00-00,E115-00-00_0010 ,29360.2
     650     650
River Rch & RM=E115-00-00,E115-00-00_0010 ,28586.7
     680     680
River Rch & RM=E115-00-00,E115-00-00_0010 ,28025.6
     750     750
River Rch & RM=E115-00-00,E115-00-00_0009 ,27466.2
     750     750
River Rch & RM=E115-00-00,E115-00-00_0009 ,26924.0
    1660    1660
River Rch & RM=E115-00-00,E115-00-00_0009 ,26206.4
    1700    1700
River Rch & RM=E115-00-00,E115-00-00_0009 ,25073.7
    1790    1790
River Rch & RM=E115-00-00,E115-00-00_0009 ,24695.0
    1850    1850
River Rch & RM=E115-00-00,E115-00-00_0009 ,23509.6
    2900    2900
River Rch & RM=E115-00-00,E115-00-00_0009 ,20146.5
    5430    5430
River Rch & RM=E115-00-00,E115-00-00_0009 ,18986.6
    5616    5616
River Rch & RM=E115-00-00,E115-00-00_0009 ,18584.6
    5600    5600
River Rch & RM=E115-00-00,E115-00-00_0009 ,17975.5
    5520    5520
River Rch & RM=E115-00-00,E115-00-00_0009 ,15262.0
    5460    5460
River Rch & RM=E115-00-00,E115-00-00_0009 ,13336.3
    5420    5420
River Rch & RM=E115-00-00,E115-00-00_0009 ,11812.3
    5370    5370
River Rch & RM=E115-00-00,E115-00-00_0009 ,10368.6
    5340    5340
River Rch & RM=E115-00-00,E115-00-00_0009 ,9275.2
    5340    5340
River Rch & RM=E115-00-00,E115-00-00_0009 ,8157.3
    7060    7060
River Rch & RM=E115-00-00,E115-00-00_0009 ,6852.1
    7180    7180
River Rch & RM=E115-00-00,E115-00-00_0009 ,6273.6
    7470    7470
River Rch & RM=E115-00-00,E115-00-00_0009 ,4894.1
    7660    7660
River Rch & RM=E115-00-00,E115-00-00_0009 ,4024.5
    7870    7870
River Rch & RM=E115-00-00,E115-00-00_0009 ,3095.3
    8100    8100
River Rch & RM=E115-00-00,E115-00-00_0009 ,2090.4
    8598    8598
River Rch & RM=GolfCourse,Split           ,4319.499
     850     850
River Rch & RM=GolfCourse,Split           ,4152.239
     850     850
River Rch & RM=GolfCourse,Split           ,3570.969
     850     850
River Rch & RM=GolfCourse,Split           ,2966.023
     850     850
River Rch & RM=GolfCourse,Split           ,1132.226
     850     850
River Rch & RM=GolfCourse,Split           ,963.1334
     850     850
River Rch & RM=GolfCourse,Split           ,675.0079
     850     850
River Rch & RM=GolfCourse,Split           ,231.8512
     850     850
Boundary for River Rch & Prof#=E115-00-00,E115-00-00_0008 , 1
Up Type= 0
Dn Type= 3
Dn Slope=.001
Boundary for River Rch & Prof#=E115-00-00,E115-00-00_0008 , 2
Up Type= 0
Dn Type= 3
Dn Slope=.001
Boundary for River Rch & Prof#=E115-00-00,E115-00-00_0010 , 1
Up Type= 0
Dn Type= 0
Boundary for River Rch & Prof#=E115-00-00,E115-00-00_0010 , 2
Up Type= 0
Dn Type= 0
Boundary for River Rch & Prof#=E115-00-00,E115-00-00_0009 , 1
Up Type= 0
Dn Type= 3
Dn Slope=.001
Boundary for River Rch & Prof#=E115-00-00,E115-00-00_0009 , 2
Up Type= 0
Dn Type= 3
Dn Slope=.001
Boundary for River Rch & Prof#=GolfCourse,Split           , 1
Up Type= 0
Dn Type= 0
Boundary for River Rch & Prof#=GolfCourse,Split           , 2
Up Type= 0
Dn Type= 0
Observed WS=E115-00-00      ,E115-00-00_0008 ,794.3   , 0 ,62.68,64.76
DSS Import GetInterval= 0
DSS Import GetPeak= 0
DSS Import FillOption= 0

--- E115-00-00.g01 (geometry) ---

Geom Title=E115-00-00
Version=Version 3.0.1  May 2012

Junct Name=Golf_DS
Junct Desc=, 0 , 0 ,-1
Up River,Reach=GolfCourse      ,Split
Up River,Reach=E115-00-00      ,E115-00-00_0010
Dn River,Reach=E115-00-00      ,E115-00-00_0009
Junc L&A=231.85,
Junc L&A=107.8,

Junct Name=Golf_US
Junct Desc=, 0 , 0 ,-1
Up River,Reach=E115-00-00      ,E115-00-00_0008
Dn River,Reach=GolfCourse      ,Split
Dn River,Reach=E115-00-00      ,E115-00-00_0010
Junc L&A=50,
Junc L&A=152.6,

River Reach=E115-00-00      ,E115-00-00_0008
Reach XY= 12
     3063209.025     13867111.81      3063286.47     13867116.72
      3063325.53     13867118.46      3063378.48      13867122.8
       3063461.9     13867122.44      3063628.48     13867133.22
      3063676.23     13867140.16      3063779.53     13867134.08
      3063793.42     13867136.69      3063810.78     13867149.71
 3063828.715075613867158.2451841 3063844.710307913867156.2320472

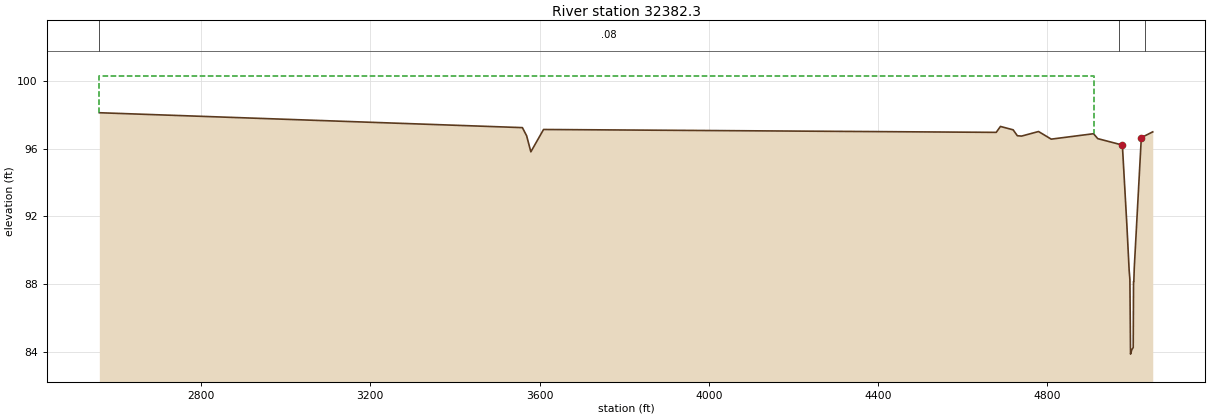
Type RM Length L Ch R = 1 ,32382.3 ,101,100,99
BEGIN DESCRIPTION:
STEFFANI - XS 4
Interplotated channel, LIDAR overbanks
Levees are not FEMA regulated levees, only RAS levees to prevent spilling into E115-09-00.
END DESCRIPTION:
XS GIS Cut Line= 2
      3063172.57     13869553.82 3063253.081226213867065.0838898
#Sta/Elev= 28
  2559.4   98.12  3559.4   97.24  3569.4   96.76  3579.4   95.81  3609.4   97.13
  4679.4   96.96  4689.4   97.31  4719.4   97.11  4729.4   96.76  4739.4   96.74
  4779.4   97.01  4809.4   96.56  4909.4   96.88  4919.4   96.59    4970   96.26
  4977.6   96.21  4988.4   91.41  4993.6   88.83  4995.4   88.27  4996.9   83.86
  5000.1   84.13 5003.21   84.25    5004   88.15  5004.7   88.15  5005.7   88.94
  5022.4   96.65    5030  96.746  5049.4   96.99
#Mann= 3 ,-1 , 0
  2559.4     .08       0    4970     .04       0    5030     .99       0
#XS Ineff= 2 , 0
       0  4909.4   100.3  5022.4       0      96
Permanent Ineff=
       F       F
Bank Sta=4977.6,5022.4
XS Rating Curve= 0
Exp/Cntr=.5,.3