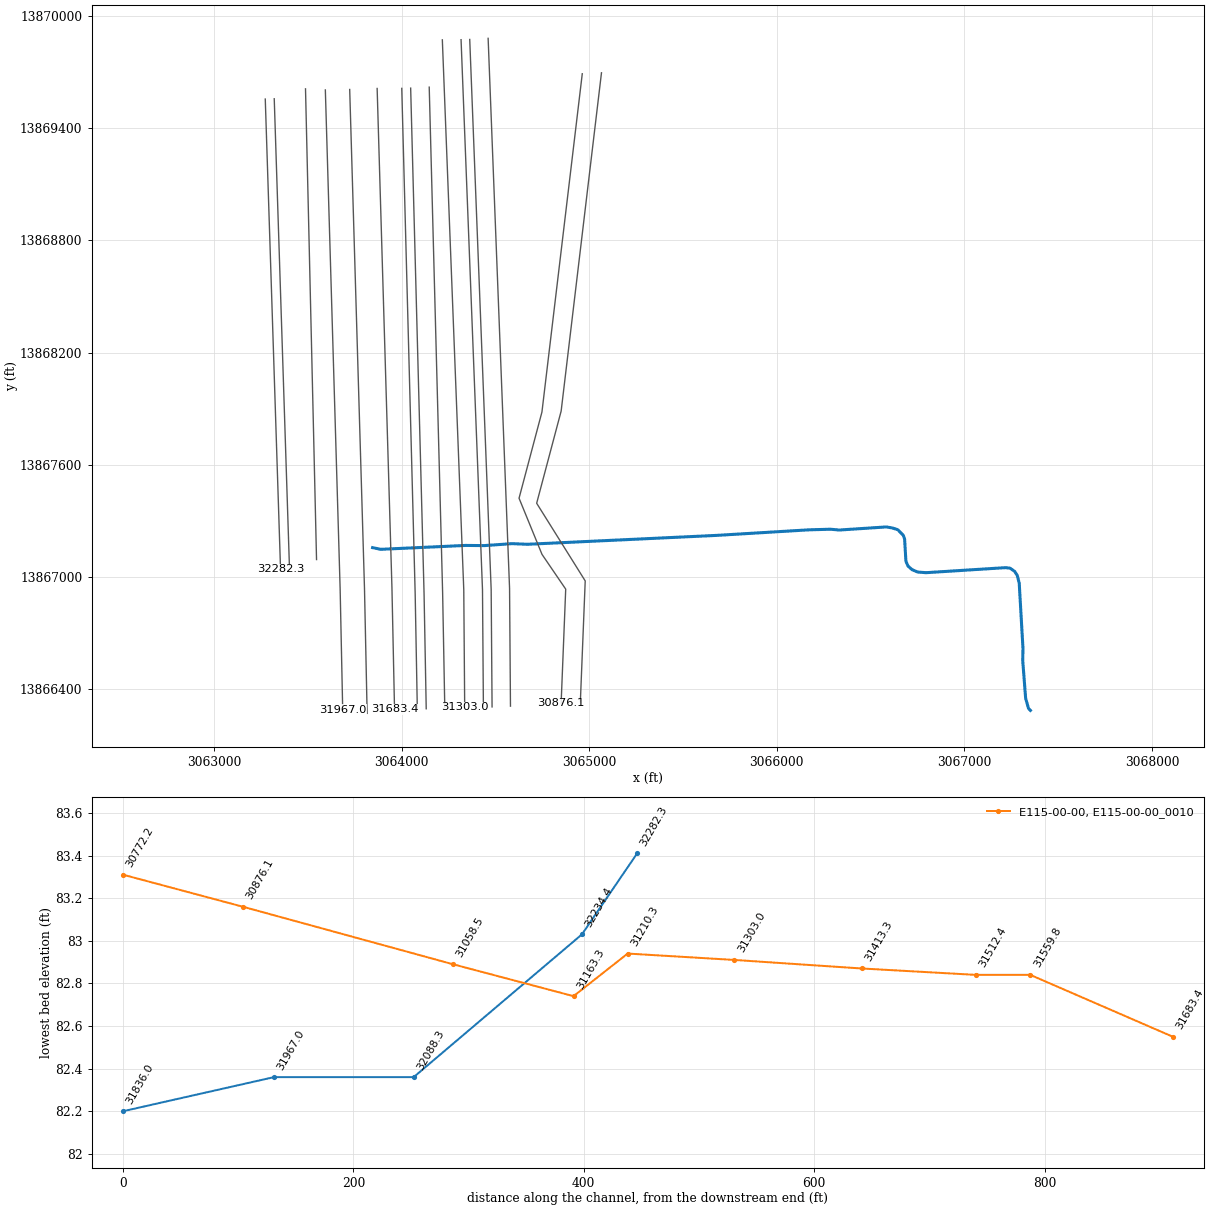
HEC-RAS study E115-00-00.prj: E115-00-00

--- E115-00-00.g01 (geometry) --- (continued)

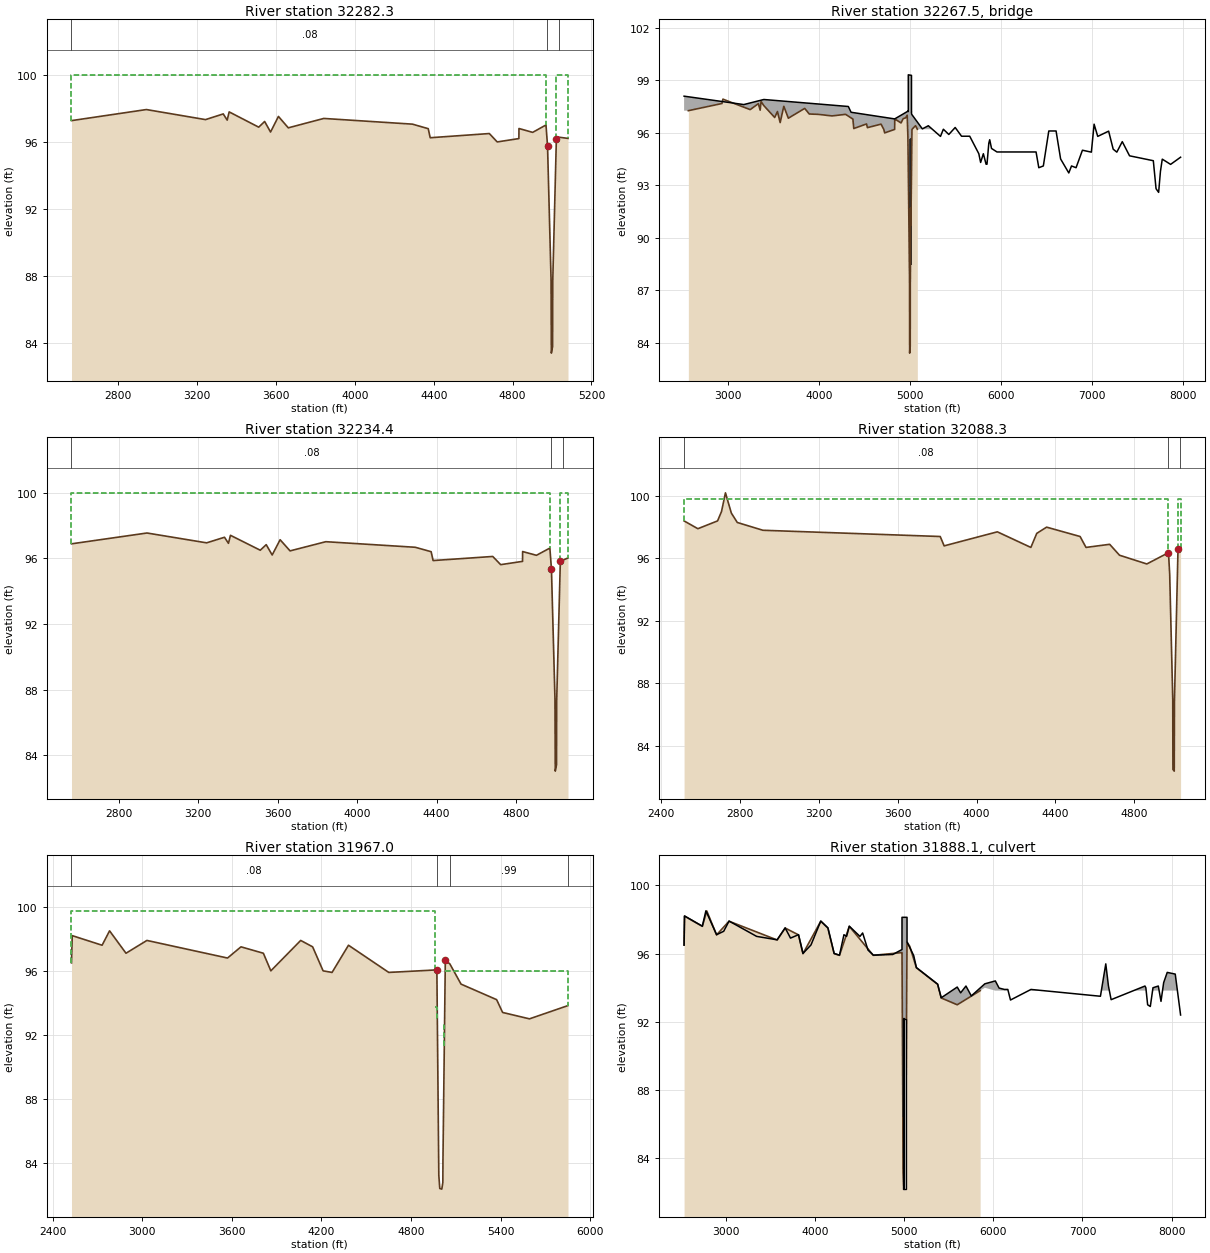
Type RM Length L Ch R = 1 ,32282.3 ,46.7,47.9,48.7
BEGIN DESCRIPTION:
STEFFANI - XS 3
Levees are not FEMA regulated levees, only RAS levees to prevent spilling into E115-09-00.
END DESCRIPTION:
XS GIS Cut Line= 2
      3063272.51       13869557. 3063353.973718613867039.1387816
#Sta/Elev= 30
  2562.2   97.27  2942.2   97.93  3242.2   97.33  3332.2   97.67  3352.2    97.3
  3362.2   97.79  3512.2   96.88  3542.2   97.22  3572.2   96.59  3612.2   97.52
  3662.2   96.84  3842.2    97.4  4292.2   97.06  4372.2   96.79  4382.2   96.25
  4682.2    96.5  4722.2      96  4832.2    96.2  4832.6    96.8  4902.2   96.57
  4969.7   97.01  4976.5   95.93  4977.6   95.76  4995.4   87.82  4996.9   83.41
 5003.21    83.8    5004    87.7  5022.4    96.2  5036.5   96.28  5081.4   96.21
#Mann= 3 ,-1 , 0
  2562.2     .08       0  4976.5     .04       0  5036.5     .99       0
#XS Ineff= 2 , 0
       0  4969.7     100  5022.4       0     100
Permanent Ineff=
       F       F
Bank Sta=4977.6,5022.4
XS Rating Curve= 0
Exp/Cntr=.5,.3

Type RM Length L Ch R = 3 ,32267.5 ,,,
BEGIN DESCRIPTION:
STEFFANI
Structure ID: E115-00-00-27
END DESCRIPTION:
Bridge Culvert--1,0,-1,-1, 0
Deck Dist Width WeirC Skew NumUp NumDn MinLoCord MaxHiCord MaxSubmerge Is_Ogee
10,27,2.6,0, 60, 60, , , .95, 0, ,,,
    2515  3172.2  3392.2  4322.2  4352.2  4832.2  4977.6  4981.2 4981.62 4981.73
 4981.84  4981.9    5017 5017.11 5017.19  5017.3  5017.6  5022.4  5136.5  5202.2
    5336  5367.6  5427.6  5497.6  5567.6  5657.6  5757.6  5777.6  5807.6  5837.6
  5847.6  5867.6  5877.6  5897.6  5957.6  6387.6  6417.6  6467.6  6527.6  6607.6
  6657.6  6747.6  6777.6  6827.6  6897.6    6996    7026    7066    7186    7236
    7276    7336    7416  7677.6  7707.6    7736    7756    7776  7867.6  7977.6
    98.1   97.62   97.91   97.51   97.18    96.8   97.24   97.25   97.22   99.32
   99.32   99.32   99.29   97.19   97.19   97.19   97.09   97.04   96.23   96.41
    95.8   96.21   95.91   96.31   95.81   95.81   94.81   94.31   94.81   94.21
   94.21   95.41   95.61   95.11   94.91   94.91   94.01   94.11   96.11   96.11
   94.51   93.71   94.11   94.01   95.01    94.9    96.5    95.8    96.1   95.07
    94.9    95.5   94.69   94.41   92.81    92.6    93.8    94.5    94.2   94.61
                                                           94.16   93.97   93.92
   93.88   95.72   95.69   95.69   95.69   93.85   93.99
                                                                                
                                                                                
                                                                                
                                                                                
    2515  3172.2  3392.2  4322.2  4352.2  4832.2  4977.6  4981.2 4981.62 4981.73
 4981.84  4981.9    5017 5017.11 5017.19  5017.3  5017.6  5022.4  5136.5  5202.2
    5336  5367.6  5427.6  5497.6  5567.6  5657.6  5757.6  5777.6  5807.6  5837.6
  5847.6  5867.6  5877.6  5897.6  5957.6  6387.6  6417.6  6467.6  6527.6  6607.6
  6657.6  6747.6  6777.6  6827.6  6897.6    6996    7026    7066    7186    7236
    7276    7336    7416  7677.6  7707.6    7736    7756    7776  7867.6  7977.6
    98.1   97.62   97.91   97.51   97.18    96.8   97.24   97.25   97.22   99.32
   99.32   99.32   99.29   97.19   97.19   97.19   97.09   97.04   96.23   96.41
    95.8   96.21   95.91   96.31   95.81   95.81   94.81   94.31   94.81   94.21
   94.21   95.41   95.61   95.11   94.91   94.91   94.01   94.11   96.11   96.11
   94.51   93.71   94.11   94.01   95.01    94.9    96.5    95.8    96.1   95.07
    94.9    95.5   94.69   94.41   92.81    92.6    93.8    94.5    94.2   94.61
                                                           94.16   93.97   93.92
   93.88   95.72   95.69   95.69   95.69   93.85   93.99
                                                                                
                                                                                
                                                                                
                                                                                
Pier Skew, UpSta & Num, DnSta & Num=  ,4993.6, 2 ,4993.6, 2 , 0 , 0 , 0 ,,
     1.5     1.5
   87.15   96.71
     1.5     1.5
   86.81   96.37
Pier Skew, UpSta & Num, DnSta & Num=  ,5005.7, 2 ,5005.7, 2 , 0 , 0 , 0 ,,
     1.5     1.5
    86.9    96.7
     1.5     1.5
   86.56   96.36
BR Coef= 1 , 1 , 1 ,1.05, 0 ,,,.8,0,1.2,0,
WSPro=,,,, 1 ,,,, 0 ,,,, 0 ,,,,-1 ,-1 ,-1 , 0 , 0 , 0 , 0 , 0
BR U #Sta/Elev= 67
  2562.2   97.27  2932.2   97.68  2942.2   97.93  3242.2   97.33  3332.2   97.67
  3352.2    97.3  3362.2   97.79  3392.2   97.56  3512.2   96.88  3542.2   97.22
  3572.2   96.59  3612.2   97.52  3662.2   96.84  3842.2    97.4  3892.2   97.08
  3992.2   97.06  4142.2   96.97  4292.2   97.06  4372.2   96.79  4382.2   96.25
  4522.2   96.51  4532.2    96.3  4682.2    96.5  4712.2    96.2  4722.2      96
  4832.2    96.2  4832.6    96.8  4832.7    96.8  4889.5   96.61  4902.2   96.57
  4925.2   96.81  4940.1   96.84  4952.3   96.86  4969.7   97.01  4976.5   95.93
  4977.6   95.76  4981.2   94.16  4981.3   94.12 4981.41   94.07 4981.51   94.02
 4981.62   93.97 4981.73   93.92 4981.84   93.88  4981.9   93.85  4988.4   90.96
  4993.6   88.38  4995.3   87.85  4995.4   87.82  4996.9   83.41  5000.1   83.68
 5003.21    83.8    5004    87.7  5004.7    87.7  5005.7   88.49  5011.5   91.18
 5016.89   93.66    5017   93.71 5017.11   93.76 5017.19    93.8  5017.3   93.85
 5017.41    93.9  5017.5   93.94  5017.6   93.99  5022.4    96.2  5036.5   96.28
    5061   96.41  5081.4   96.21
BR U #Mann= 3
  2562.2     .08  4976.5     .04  5036.5     .99
BR D #Sta/Elev= 66
  2562.2   96.89  2932.2    97.3  2942.2   97.55  3242.2   96.95  3332.2   97.29
  3352.2   96.92  3362.2   97.41  3392.2   97.18  3512.2    96.5  3542.2   96.84
  3572.2   96.21  3612.2   97.14  3662.2   96.46  3842.2   97.02  3892.2    96.7
  3992.2   96.68  4142.2   96.59  4292.2   96.68  4372.2   96.41  4382.2   95.87
  4522.2   96.13  4532.2   95.92  4682.2   96.12  4712.2   95.82  4722.2   95.62
  4832.2   95.82  4832.6   96.42  4832.7   96.42  4889.5   96.23  4902.2   96.19
  4925.2   96.43  4940.1   96.46  4952.3   96.48  4969.7   96.63  4976.5   95.55
  4977.6   95.38  4981.2   93.78  4981.3   93.74 4981.41   93.69 4981.51   93.64
 4981.62   93.59 4981.73   93.54 4981.84    93.5  4981.9   93.47  4988.4   90.58
  4993.6      88  4995.3   87.47  4995.4   87.44  4996.9   83.03  5000.1    83.3
 5003.21   83.42    5004   87.32  5004.7   87.32  5005.7   88.11  5011.5    90.8
 5016.89   93.28    5017   93.33 5017.11   93.38 5017.19   93.42  5017.3   93.47
 5017.41   93.52  5017.5   93.56  5017.6   93.61  5022.4   95.82  5036.5    95.9
    5061   96.03
BR D #Mann= 3
  2562.2     .08  4976.5     .04  5036.5     .99
BC Design=,, 0 ,, 0 ,,,,,,
BC HTab HWMax=99.12

Type RM Length L Ch R = 1 ,32234.4 ,146.4,146.1,145.6
BEGIN DESCRIPTION:
STEFFANI - XS 2
Levees are not FEMA regulated levees, only RAS levees to prevent spilling into E115-09-00.
END DESCRIPTION:
XS GIS Cut Line= 2
      3063320.34      13869558.6 3063401.160489613867060.1882052
#Sta/Elev= 30
  2562.2   96.89  2942.2   97.55  3242.2   96.95  3332.2   97.29  3352.2   96.92
  3362.2   97.41  3512.2    96.5  3542.2   96.84  3572.2   96.21  3612.2   97.14
  3662.2   96.46  3842.2   97.02  4292.2   96.68  4372.2   96.41  4382.2   95.87
  4682.2   96.12  4722.2   95.62  4832.2   95.82  4832.6   96.42  4902.2   96.19
  4969.7   96.63  4976.5   95.55  4977.6   95.38  4995.4   87.44  4996.9   83.03
 5003.21   83.42    5004   87.32  5022.4   95.82  5036.5    95.9    5061   96.03
#Mann= 3 ,-1 , 0
  2562.2     .08       0  4976.5     .04       0  5036.5     .99       0
#XS Ineff= 2 , 0
       0  4969.7     100  5022.4       0     100
Permanent Ineff=
       F       F
Bank Sta=4977.6,5022.4
XS Rating Curve= 0
Exp/Cntr=.5,.3

Type RM Length L Ch R = 1 ,32088.3 ,121,121.3,121.2
BEGIN DESCRIPTION:
GESSNER - XS 4
Cross Section x23
Located At: US GESSNER ROAD
Levees are not FEMA regulated levees, only RAS levees to prevent spilling into E115-09-00.
END DESCRIPTION:
XS GIS Cut Line= 2
       3063487.1     13869611.62 3063545.872239113867092.2841533
#Sta/Elev= 30
  2515.5    98.4  2585.5    97.9  2685.5    98.4  2705.5      99  2725.5   100.2
  2755.5    98.9  2785.5    98.3  2915.5    97.8  3815.5    97.4  3835.5    96.8
  4105.5    97.7  4275.5    96.7  4305.5    97.6  4355.5      98  4525.5    97.4
  4555.5    96.7  4675.5    96.9  4725.5    96.2  4864.2   95.64  4973.5   96.36
  4974.1   96.37  4980.2   94.98  4995.8   86.93  4996.2    84.2  4996.7   82.47
  5003.3   82.36  5004.4   86.88  5022.5   96.63  5031.1   96.64  5035.5    96.7
#Mann= 3 ,-1 , 0
  2515.5     .08       0  4973.5     .04       0  5031.1     .99       0
#XS Ineff= 2 , 0
       0  4974.1    99.8  5022.5       0    99.8
Permanent Ineff=
       F       F
Bank Sta=4974.1,5022.5
XS Rating Curve= 0
Exp/Cntr=.5,.3

Type RM Length L Ch R = 1 ,31967.0 ,130.1,131,129.9
BEGIN DESCRIPTION:
GESSNER - XS 3
Levees are not FEMA regulated levees, only RAS levees to prevent spilling into E115-09-00.
END DESCRIPTION:
XS GIS Cut Line= 3
      3063592.84      13869605.8      3063671.73     13866934.87
 3063685.408721313866287.0375748
#Sta/Elev= 30
  2526.7    96.5  2531.7    98.2  2731.7    97.6  2781.7    98.5  2891.7    97.1
  3031.7    97.9  3571.7    96.8  3661.7    97.5  3811.7    97.1  3861.7      96
  4061.7    97.9  4141.7    97.5  4211.7      96  4271.7    95.9  4381.7    97.6
  4651.7    95.9  4973.5   96.06  4973.6   96.06  4986.6   83.23  4993.1    82.4
  5006.6   82.36  5013.6   82.77  5014.5   84.26  5030.2   96.67  5060.8   96.43
  5135.6   95.17  5373.8    94.2  5413.8    93.4  5593.8      93  5851.8   93.83
#Mann= 4 ,-1 , 0
  2526.7     .08       0  4973.5     .04       0  5060.8     .99       0
  5851.8     .05       0
#XS Ineff= 4 ,-1
  2526.7  4960.7   99.75  4960.7  4976.7   93.74 5023.44  5030.2   92.64
  5030.2  5851.3      96
Permanent Ineff=
       F       F       F       F
Bank Sta=4973.6,5030.2
XS Rating Curve= 0
Exp/Cntr=.5,.3

Type RM Length L Ch R = 2 ,31888.1 ,,,
BEGIN DESCRIPTION:
GESSNER ROAD
Structure ID: E115-00-00-26
END DESCRIPTION:
Bridge Culvert--1,0,-1,-1, 0
Deck Dist Width WeirC Skew NumUp NumDn MinLoCord MaxHiCord MaxSubmerge Is_Ogee
10,108,3,0, 60, 60, , , .95, 0, ,,,
  2526.7  2531.7  2731.7  2771.7  2891.7  2971.7  3031.7  3341.7  3571.7  3661.7
  3721.7  3811.7  3861.7  3951.7  4061.7  4141.7  4211.7  4271.7  4321.7  4351.7
  4381.7  4501.7  4531.7  4591.7  4651.7  4869.8  4973.5  4973.6  5030.1  5030.2
  5104.9  5135.6  5373.8  5413.8  5593.8  5631.8  5691.8  5751.8  5903.8  6021.8
  6063.8  6123.8  6161.8  6191.8  6421.8  7201.8  7261.8  7291.8  7321.8  7701.8
  7711.8  7731.8  7761.8  7791.8  7851.8  7881.8  7911.8  7951.8  8041.8  8101.8
    96.5   98.21   97.61   98.51   97.11   97.31   97.91   97.01   96.81   97.51
   96.91   97.11   96.01   96.51   97.91   97.51   96.01   95.91   97.11   97.01
   97.61   97.01   97.21   96.21   95.91   95.95   96.24   98.13   98.13   96.68
   95.89   95.18   94.21   93.41   94.04    93.7    94.1   93.52   94.23    94.4
   93.98    93.9    93.9   93.28    93.9    93.5    95.4    94.1    93.3    94.1
      94      93    92.9      94    94.1    93.2    94.3    94.9    94.8    92.4
    96.5    98.2    97.6    98.5    97.1    97.3    97.9      97    96.8    97.5
    96.9    97.1      96    96.5    97.9    97.5      96    95.9    97.1      97
    97.6      97    97.2    96.2    95.9   95.57   96.06      80      80   96.67
   95.88   95.17    94.2    93.4      93   93.12   93.32   93.51      94   93.48
    93.3    93.8    93.5   93.27   93.53   92.73   92.63   92.59   92.54    92.3
   92.29   92.29   92.28   92.27   92.24   92.23   92.22   92.21   92.18   92.15
  2526.7  2531.7  2731.7  2771.7  2891.7  2971.7  3031.7  3341.7  3571.7  3661.7
  3721.7  3811.7  3861.7  3951.7  4061.7  4141.7  4211.7  4271.7  4321.7  4351.7
  4381.7  4501.7  4531.7  4591.7  4651.7  4869.8  4960.7  4973.5  4973.6  5030.1
  5030.2    5062    5168  5373.8  5431.8  5593.8  5631.8  5691.8  5751.8  5903.8
  6021.8  6063.8  6123.8  6161.8  6191.8  6421.8  7201.8  7261.8  7321.8  7701.8
  7711.8  7731.8  7761.8  7791.8  7851.8  7881.8  7911.8  7951.8  8041.8  8101.8
    96.5   98.21   97.61   98.51   97.11   97.31   97.91   97.01   96.81   97.51
   96.91   97.11   96.01   96.51   97.91   97.51   96.01   95.91   97.11   97.01
   97.61   97.01   97.21   96.21   95.91   95.95   96.21   96.24   98.13   98.13
   96.68   96.43   94.91   94.21   93.37   94.04    93.7    94.1   93.52   94.23
    94.4   93.98    93.9    93.9   93.28    93.9    93.5    95.4    93.3    94.1
      94      93    92.9      94    94.1    93.2    94.3    94.9    94.8    92.4
    96.5    98.2    97.6    98.5    97.1    97.3    97.9      97    96.8    97.5
    96.9    97.1      96    96.5    97.9    97.5      96    95.9    97.1      97
    97.6      97    97.2    96.2    95.9   95.57   95.98   95.87      80      80
   96.48   96.42    94.9    94.2   93.36      93   93.12   93.32   93.51      94
   93.48    93.3    93.8    93.5   93.27   93.53   92.73   92.63   92.54    92.3
   92.29   92.29   92.28   92.27   92.24   92.23   92.22   92.21   92.18   92.15
BR Coef= 1 , 0 , 0 ,1.25, 0 ,,,.8,-1,2,0,
WSPro=,,,, 1 ,,,, 0 ,,,, 0 ,,,,-1 ,-1 ,-1 , 0 , 0 , 0 , 0 , 0
Culvert=2,10,12,108,.015,.4,1,8,1,82.2,4992.7,81.91,4992.7,Culvert #1  , 0 ,10
Culvert Bottom n=.015
Culvert=2,10,12,108,.015,.4,1,8,1,82.19,5007.5,81.91,5007.5,Culvert #2  , 0 ,10
Culvert Bottom n=.015
BC Design=,, 0 ,, 0 ,,,,,,
BC HTab HWMax=98.5

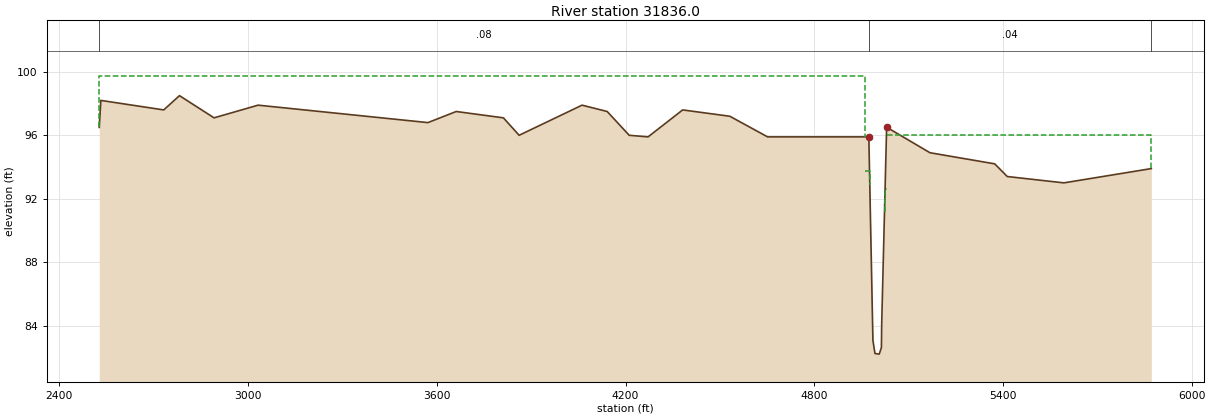
Type RM Length L Ch R = 1 ,31836.0 ,0,0,0
BEGIN DESCRIPTION:
GESSNER - XS 2
Levees are not FEMA regulated levees, only RAS levees to prevent spilling into E115-09-00.
END DESCRIPTION:
XS GIS Cut Line= 3
      3063722.68     13869608.26      3063801.57     13866937.12
 3063815.676212613866269.0819322
#Sta/Elev= 30
  2526.7    96.5  2531.7    98.2  2731.7    97.6  2781.7    98.5  2891.7    97.1
  3031.7    97.9  3571.7    96.8  3661.7    97.5  3811.7    97.1  3861.7      96
  4061.7    97.9  4141.7    97.5  4211.7      96  4271.7    95.9  4381.7    97.6
  4531.7    97.2  4651.7    95.9  4973.5    95.9  4973.6    95.9  4986.6   83.07
  4993.1   82.24  5006.6    82.2  5013.6   82.61  5014.5    84.1  5030.2   96.51
    5168    94.9  5373.8    94.2  5413.8    93.4  5593.8      93  5871.8    93.9
#Mann= 3 ,-1 , 0
  2526.7     .08       0  4973.5     .04       0  5871.8     .05       0
#XS Ineff= 4 ,-1
  2526.7  4960.7   99.75  4960.7  4976.7   93.74 5023.44  5030.2   92.64
  5030.2    5871      96
Permanent Ineff=
       F       F       F       F
Bank Sta=4973.6,5030.2
XS Rating Curve= 0
Exp/Cntr=.5,.3

River Reach=E115-00-00      ,E115-00-00_0010
Reach XY= 30
 3063844.710307913867156.2320472      3063888.03     13867147.11
      3064341.16     13867167.94      3064439.75       13867167.
      3064589.42     13867177.49      3064668.75       13867174.
      3065680.57     13867221.76      3066168.42     13867251.27
       3066285.6     13867254.74      3066333.35      13867250.4
      3066583.35      13867266.9      3066615.46     13867261.69
      3066645.25       13867252.      3066674.49     13867221.76
      3066681.44     13867201.79      3066688.38     13867082.87
      3066699.67      13867057.7       3066720.5      13867038.6
      3066750.88     13867025.58      3066796.02     13867022.11
      3067219.63     13867049.02      3067243.07     13867046.41
      3067268.24     13867029.05      3067282.13     13867007.35
      3067292.55     13866965.68       3067312.5       13866617.
      3067311.25       13866551.      3067326.75       13866350.
      3067342.03     13866295.54 3067352.1176145 13866285.040838

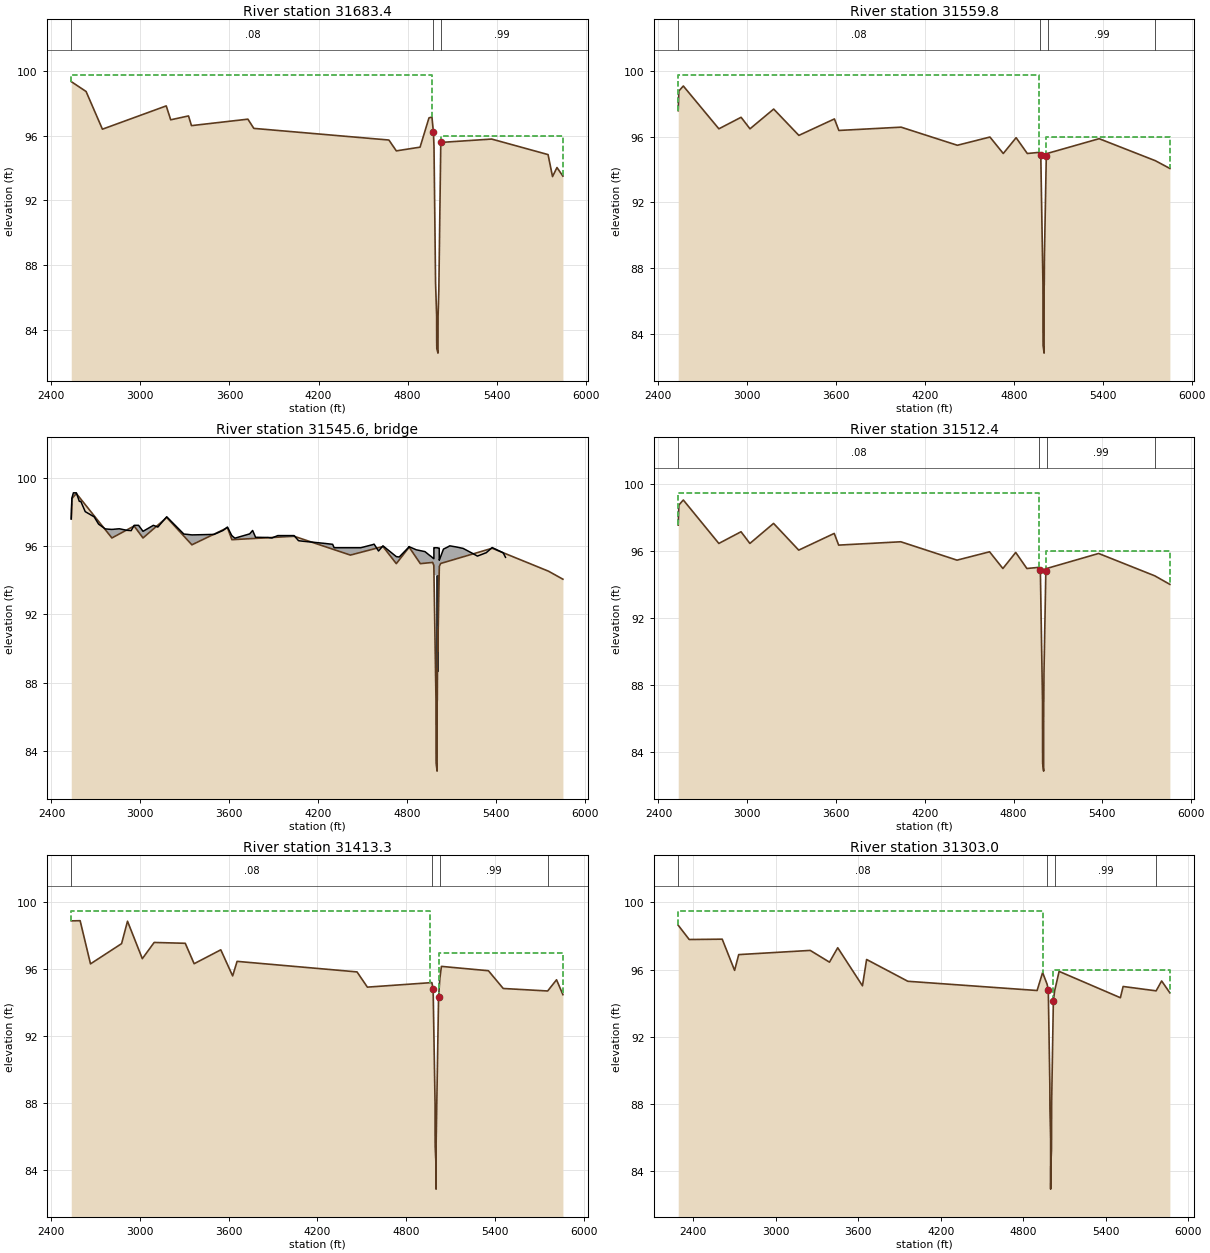
Type RM Length L Ch R = 1 ,31683.4 ,124,123.6,123.5
BEGIN DESCRIPTION:
TALINA WAY - XS 4
Interplotated channel, LIDAR overbanks
Levees are not FEMA regulated levees, only RAS levees to prevent spilling into E115-09-00.
END DESCRIPTION:
XS GIS Cut Line= 3
      3063869.02     13869613.63      3063947.91     13866942.49
      3063961.71     13866291.67
#Sta/Elev= 30
  2534.2   99.33  2634.2   98.72  2744.2   96.39  3174.2   97.83  3204.2   96.97
  3324.2   97.21  3344.2   96.61  3724.2   97.01  3764.2   96.44  4674.2   95.72
  4724.2   95.05  4884.2   95.28  4944.2   97.09  4964.2   97.14  4974.2   96.19
 4977.96   95.33 4988.61   86.88 4995.87   84.84 4996.23   83.29 4996.84   82.83
    5005   82.55  5005.5   84.83 5010.57   86.47 5023.79   95.57    5028  95.574
  5366.5   95.78  5746.5   94.82  5776.5   93.46  5806.5   94.02  5846.5   93.49
#Mann= 3 ,-1 , 0
  2534.2     .08       0  4974.2     .04       0    5028     .99       0
#XS Ineff= 2 ,-1
  2534.2  4964.2   99.75 5023.79    5876      96
Permanent Ineff=
       F       F
Bank Sta=4974.2,5023.79
XS Rating Curve= 0
Exp/Cntr=.5,.3

Type RM Length L Ch R = 1 ,31559.8 ,47.6,47.4,47.8
BEGIN DESCRIPTION:
TALINA WAY - XS 3
Levees are not FEMA regulated levees, only RAS levees to prevent spilling into E115-09-00.
END DESCRIPTION:
XS GIS Cut Line= 4
       3064000.3     13869614.21      3064071.84     13866907.91
      3064082.84     13866313.87      3064083.18     13866295.71
#Sta/Elev= 30
  2533.7   97.57  2538.2   98.77  2568.2   99.07  2808.2   96.47  2958.2   97.17
  3018.2   96.47  3178.2   97.67  3348.2   96.07  3588.2   97.07  3618.2   96.37
  4038.2   96.57  4418.2   95.47  4638.2   95.97  4728.2   94.97  4814.9   95.93
  4890.4   94.97  4973.8   95.04  4981.5   94.86  4996.2   86.95  4996.5   84.14
    4997   83.31  5003.7   82.84  5004.1   86.93  5004.9   87.01    5006   88.72
  5018.6   94.81  5027.9   94.98  5375.4   95.87  5755.3   94.53    5853   94.06
#Mann= 4 ,-1 , 0
  2533.7     .08       0  4973.8     .04       0  5027.9     .99       0
  5755.3    .015       0
#XS Ineff= 2 ,-1
  2533.7 4972.52   99.75  5018.6  5865.3      96
Permanent Ineff=
       F       F
Bank Sta=4981.5,5018.6
XS Rating Curve= 0
Exp/Cntr=.5,.3

Type RM Length L Ch R = 3 ,31545.6 ,,,
BEGIN DESCRIPTION:
TALINA WAY
Structure ID: E115-00-00-25
END DESCRIPTION:
Bridge Culvert--1,0,-1,-1, 0
Deck Dist Width WeirC Skew NumUp NumDn MinLoCord MaxHiCord MaxSubmerge Is_Ogee
10,27,2.6,0, 116, 116, , , .95, 0, ,,,
  2533.7  2538.2  2548.2  2568.2  2588.2  2598.2  2628.2  2683.7  2688.2  2718.2
  2763.7  2808.2  2858.2  2908.2  2938.2  2958.2  2988.2  3018.2  3088.2  3118.2
  3178.2  3293.7  3318.2  3348.2  3498.5  3558.2  3588.2  3618.2  3618.5  3638.5
  3698.5  3738.2  3758.2  3778.2  3858.2  3858.5  3888.2  3928.2  4038.2  4068.2
  4108.2  4158.2  4248.2  4298.2  4298.5  4308.5  4378.2  4418.2  4458.2  4488.2
  4568.5  4578.2  4598.5  4608.2  4638.2  4728.2  4748.2  4808.5  4814.8  4814.9
    4863  4890.4  4917.7  4922.1  4949.2  4964.8  4973.8  4981.5  4981.8  4981.9
 4982.01 4982.11 4982.19  4982.3  4982.4 4982.51  4989.7  4994.1  4995.3  4995.4
  4996.2  4996.5    4997  5000.1  5003.7  5004.1  5004.9    5005    5006  5011.6
 5017.39  5017.5 5017.61 5017.69  5017.8 5017.91    5018  5018.3  5018.6  5027.9
  5038.3  5046.5  5072.2  5089.2    5103  5130.3  5179.3  5179.4  5238.5  5255.4
  5269.9  5275.4  5335.4  5375.4  5449.9  5465.4
    97.6   98.81   99.11   99.11   98.61   98.61   98.01   97.73   97.71   97.28
      97   96.97   97.01   96.92    96.9   97.21   97.21   96.86   97.21   97.11
   97.71    96.7   96.68   96.65   96.68   96.91   97.11    96.6    96.6   96.46
   96.61   96.71   96.91   96.51    96.5    96.5   96.47   96.61   96.61   96.31
   96.27   96.23   96.15    96.1    96.1    95.9    95.9    95.9    95.9    95.9
   96.08   96.11   95.84   95.71   96.01   95.38   95.36    95.9   95.97   95.96
   95.78   95.73   95.68   95.67   95.48   95.38   95.31   95.26   95.26   95.89
    95.9    95.9    95.9    95.9    95.9    95.9    95.9    95.9    95.9    95.9
    95.9    95.9    95.9    95.9    95.9    95.9    95.9    95.9    95.9   95.87
   95.87   95.87   95.87   95.87   95.87   95.88   95.72   95.17   95.18   95.39
   95.63   95.82   95.93   96.01   95.99   95.95   95.86   95.86   95.59   95.51
   95.44   95.41   95.61   95.91    95.6   95.34
                                                                                
                                                                                
                                                                                
                                                                                
                                                                                
                                                                                
                                                                                
                                           94.32   94.29   94.29   94.29   94.29
   94.29   94.29   94.29   94.28   94.28   94.28   94.28   94.28   94.28   94.27
   94.27   94.27
                                                                                
                                                
  2533.7  2538.2  2548.2  2568.2  2588.2  2598.2  2628.2  2683.7  2688.2  2718.2
  2763.7  2808.2  2858.2  2908.2  2938.2  2958.2  2988.2  3018.2  3088.2  3118.2
  3178.2  3293.7  3318.2  3348.2  3498.5  3558.2  3588.2  3618.2  3618.5  3638.5
  3698.5  3738.2  3758.2  3778.2  3858.2  3858.5  3888.2  3928.2  4038.2  4068.2
  4108.2  4158.2  4248.2  4298.2  4298.5  4308.5  4378.2  4418.2  4458.2  4488.2
  4568.5  4578.2  4598.5  4608.2  4638.2  4728.2  4748.2  4808.5  4814.8  4814.9
    4863  4890.4  4917.7  4922.1  4949.2  4964.8  4973.8  4981.5  4981.8  4981.9
 4982.01 4982.11 4982.19  4982.3  4982.4 4982.51  4989.7  4994.1  4995.3  4995.4
  4996.2  4996.5    4997  5000.1  5003.7  5004.1  5004.9    5005    5006  5011.6
 5017.39  5017.5 5017.61 5017.69  5017.8 5017.91    5018  5018.3  5018.6  5027.9
  5038.3  5046.5  5072.2  5089.2    5103  5130.3  5179.3  5179.4  5238.5  5255.4
  5269.9  5275.4  5335.4  5375.4  5449.9  5465.4
    97.6   98.81   99.11   99.11   98.61   98.61   98.01   97.73   97.71   97.28
      97   96.97   97.01   96.92    96.9   97.21   97.21   96.86   97.21   97.11
   97.71    96.7   96.68   96.65   96.68   96.91   97.11    96.6    96.6   96.46
   96.61   96.71   96.91   96.51    96.5    96.5   96.47   96.61   96.61   96.31
   96.27   96.23   96.15    96.1    96.1    95.9    95.9    95.9    95.9    95.9
   96.08   96.11   95.84   95.71   96.01   95.38   95.36    95.9   95.97   95.96
   95.78   95.73   95.68   95.67   95.48   95.38   95.31   95.26   95.26   95.89
    95.9    95.9    95.9    95.9    95.9    95.9    95.9    95.9    95.9    95.9
    95.9    95.9    95.9    95.9    95.9    95.9    95.9    95.9    95.9   95.87
   95.87   95.87   95.87   95.87   95.87   95.88   95.72   95.17   95.18   95.39
   95.63   95.82   95.93   96.01   95.99   95.95   95.86   95.86   95.59   95.51
   95.44   95.41   95.61   95.91    95.6   95.34
                                                                                
                                                                                
                                                                                
                                                                                
                                                                                
                                                                                
                                                                                
                                           94.32   94.29   94.29   94.29   94.29
   94.29   94.29   94.29   94.28   94.28   94.28   94.28   94.28   94.28   94.27
   94.27   94.27
                                                                                
                                                
Pier Skew, UpSta & Num, DnSta & Num=  ,4994.1, 2 ,4994.1, 2 , 0 , 0 , 0 ,,
     1.5     1.5
   86.48   95.29
     1.5     1.5
   86.92   95.73
Pier Skew, UpSta & Num, DnSta & Num=  ,5006, 2 ,5006, 2 , 0 , 0 , 0 ,,
     1.5     1.5
   86.59   95.28
     1.5     1.5
   87.03   95.72
BR Coef= 1 , 1 , 1 ,1.05, 0 ,,,.8,0,1.2,0,
WSPro=,,,, 1 ,,,, 0 ,,,, 0 ,,,,-1 ,-1 ,-1 , 0 , 0 , 0 , 0 , 0
BC Design=,, 0 ,, 0 ,,,,,,
BC HTab HWMax=99.07

Type RM Length L Ch R = 1 ,31512.4 ,99,99.1,99.3
BEGIN DESCRIPTION:
TALINA WAY - XS 2
Levees are not FEMA regulated levees, only RAS levees to prevent spilling into E115-09-00.
END DESCRIPTION:
XS GIS Cut Line= 3
      3064047.74      13869615.5      3064119.22     13866909.04
       3064130.7     13866293.72
#Sta/Elev= 30
  2533.7   97.57  2538.2   98.77  2568.2   99.07  2808.2   96.47  2958.2   97.17
  3018.2   96.47  3178.2   97.67  3348.2   96.07  3588.2   97.07  3618.2   96.37
  4038.2   96.57  4418.2   95.47  4638.2   95.97  4728.2   94.97  4814.9   95.93
  4890.4   94.97  4973.8   95.04  4981.5   94.86  4996.2   86.95  4996.5   84.14
    4997   83.31  5003.7   82.84  5004.1   86.93  5004.9   87.01    5006   88.72
  5018.6   94.81  5027.9   94.98  5375.4   95.87  5755.3   94.53 5857.03   94.02
#Mann= 4 ,-1 , 0
  2533.7     .08       0  4973.8     .04       0  5027.9     .99       0
  5755.3    .015       0
#XS Ineff= 2 ,-1
  2533.7    4972    99.5  5018.6  5865.3      96
Permanent Ineff=
       F       F
Bank Sta=4981.5,5018.6
XS Rating Curve= 0
Exp/Cntr=.5,.3

Type RM Length L Ch R = 1 ,31413.3 ,109.6,110.3,110.8
BEGIN DESCRIPTION:
TALINA WAY - XS 1
Interplotated channel, LIDAR overbanks
Levees are not FEMA regulated levees, only RAS levees to prevent spilling into E115-09-00.
END DESCRIPTION:
XS GIS Cut Line= 3
       3064146.7     13869620.74      3064218.18     13866914.25
      3064229.66     13866301.51
#Sta/Elev= 30
  2537.5    98.9  2597.5   98.91  2667.5   96.33  2877.5   97.54  2917.5   98.88
  3017.5   96.64  3097.5   97.61  3307.5   97.56  3367.5   96.34  3547.5   97.17
  3627.5   95.61  3657.5   96.48  4467.5   95.85  4537.5   94.94    4973  95.212
 4981.47   94.83 4994.61   87.97 4994.87   86.05 4995.32   85.42  5000.9   84.33
 5001.31   82.87 5001.77   85.63 5018.15   94.33    5027  95.466  5037.5   96.18
  5354.9   95.92  5454.9   94.86  5754.9   94.71  5814.9   95.38    5858   94.49
#Mann= 4 ,-1 , 0
  2537.5     .08       0    4973     .04       0    5027     .99       0
  5754.9    .015       0
#XS Ineff= 2 ,-1
  2537.5  4957.5    99.5 5018.15    5864      97
Permanent Ineff=
       F       F
Bank Sta=4981.47,5018.15
XS Rating Curve= 0
Exp/Cntr=.3,.1

Type RM Length L Ch R = 1 ,31303.0 ,99.8,92.7,99.8
BEGIN DESCRIPTION:
HOLLOW HOOK RD - XS 4
Interplotated channel, LIDAR overbanks
Levees are not FEMA regulated levees, only RAS levees to prevent spilling into E115-09-00.
END DESCRIPTION:
XS GIS Cut Line= 3
      3064216.65     13869873.85      3064330.92     13866930.49
      3064335.82     13866301.67
#Sta/Elev= 30
  2290.2   98.64  2370.2   97.79  2610.2   97.81  2700.2   95.95  2730.2   96.89
  3250.2   97.14  3390.2   96.44  3450.2    97.3  3630.2   95.03  3660.2    96.6
  3960.2    95.3  4900.2   94.75  4940.2   95.82    4973  95.122 4981.43    94.8
 4992.83   89.11 4993.45   87.78 4998.29   85.96 4998.65   82.91 4999.18   84.19
  5004.8   85.28 5005.95    88.1 5018.29   94.11    5027  94.701  5060.2   95.89
  5505.8   94.32  5525.8   94.99  5765.8   94.73  5805.8   95.32  5865.8   94.61
#Mann= 4 ,-1 , 0
  2290.2     .08       0    4973     .04       0    5027     .99       0
  5765.8    .015       0
#XS Ineff= 2 ,-1
  2290.2  4940.2    99.5 5018.29  5865.8      96
Permanent Ineff=
       F       F
Bank Sta=4981.43,5018.29
XS Rating Curve= 0
Exp/Cntr=.5,.3

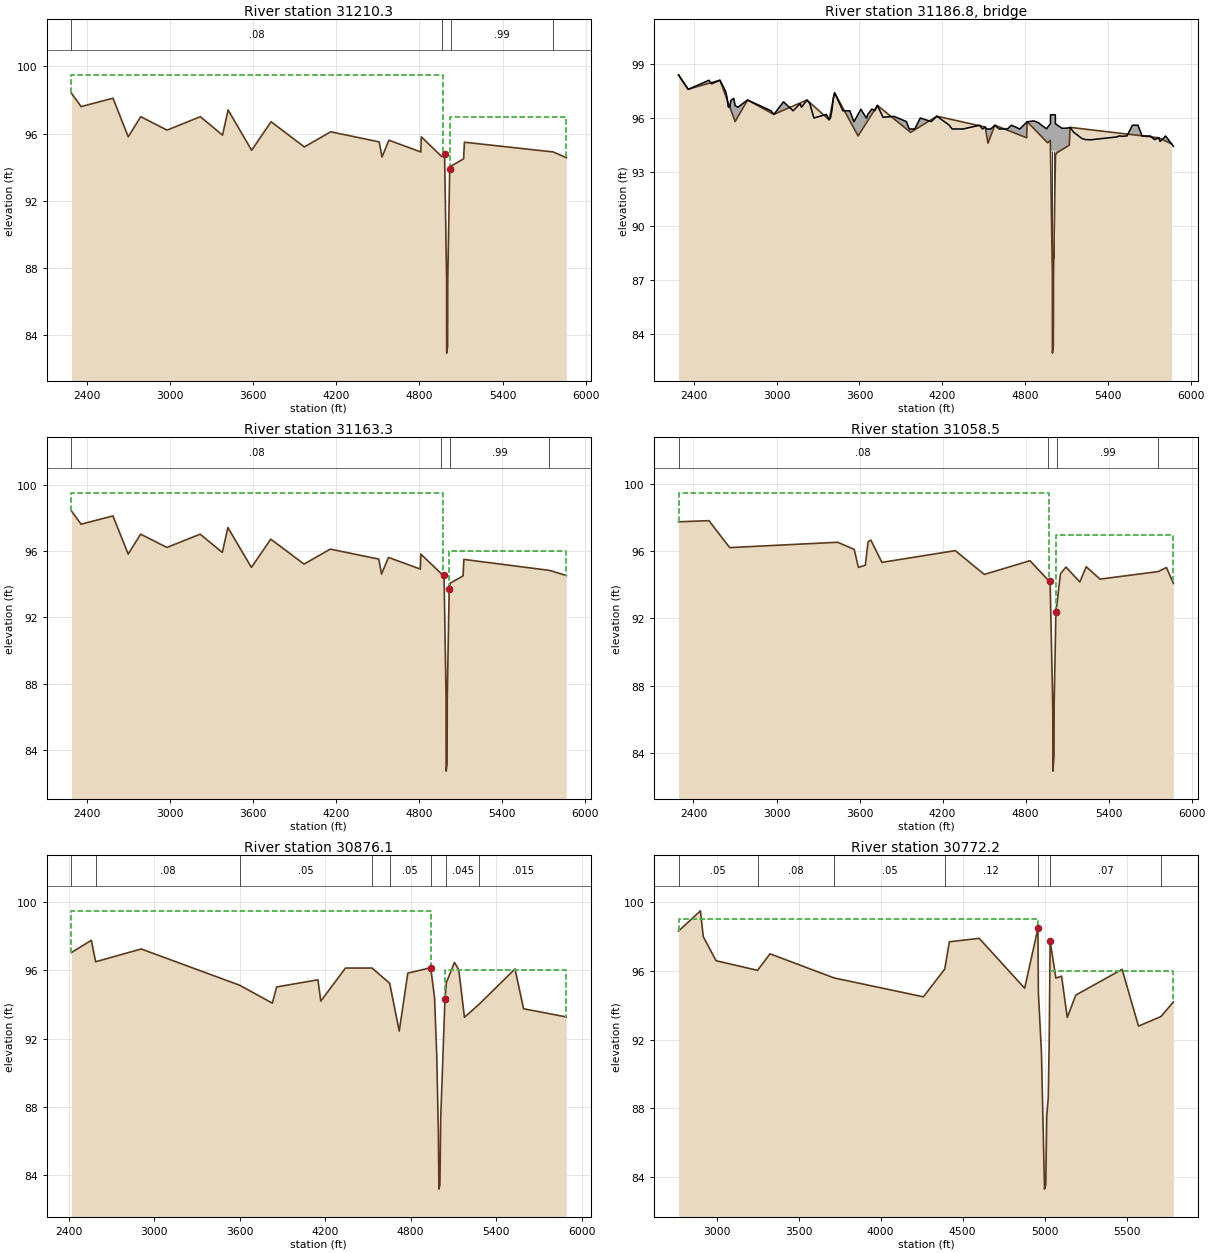
Type RM Length L Ch R = 1 ,31210.3 ,46.2,47,47.2
BEGIN DESCRIPTION:
HOLLOW HOOK RD - XS 3
Levees are not FEMA regulated levees, only RAS levees to prevent spilling into E115-09-00.
END DESCRIPTION:
XS GIS Cut Line= 4
      3064316.48      13869874.7      3064430.74     13866931.36
      3064435.34     13866331.87      3064435.52     13866307.74
#Sta/Elev= 30
    2290   98.41    2360   97.61    2590   98.11    2700   95.81    2790   97.01
    2980   96.21    3220   97.01    3380   95.91    3420   97.41    3590   95.01
    3730   96.71    3970   95.21    4160   96.11    4510   95.51    4530   94.61
    4580   95.61    4810   94.91  4813.5   95.81  4961.8   94.63  4981.4   94.77
  4996.1   87.33 4996.41   82.94  5003.3   83.35  5004.4   87.26  5018.4   93.92
  5025.5   94.06  5118.8    94.5  5124.4   95.49  5765.6   94.91 5859.47   94.57
#Mann= 4 ,-1 , 0
    2290     .08       0  4961.8     .04       0  5025.5     .99       0
  5765.6    .015       0
#XS Ineff= 2 ,-1
    2290    4972    99.5  5018.4  5882.3      97
Permanent Ineff=
       F       F
Bank Sta=4981.4,5018.4
XS Rating Curve= 0
Exp/Cntr=.5,.3

Type RM Length L Ch R = 3 ,31186.8 ,,,
BEGIN DESCRIPTION:
HOLLOW HOOK ROAD
Structure ID: E115-00-00-24
END DESCRIPTION:
Bridge Culvert--1,0,-1,-1, 0
Deck Dist Width WeirC Skew NumUp NumDn MinLoCord MaxHiCord MaxSubmerge Is_Ogee
10,27,2.6,0, 166, 166, , , .95, 0, ,,,
    2290    2360  2450.1  2500.1    2510  2510.1    2530  2550.1    2590  2600.1
    2630  2630.1    2640    2650    2660  2660.1  2670.1    2680    2690  2690.1
    2700  2700.1    2720  2730.1  2770.1    2790  2820.1  2870.1  2920.1  2940.1
    2960    2980    3050    3120    3170    3180    3220    3240    3270    3360
    3380    3390    3400    3410    3420    3480    3530  3560.1    3570    3580
    3590    3600    3610  3610.1    3620    3630  3650.1    3660  3680.1    3690
    3710    3730    3770  3850.1    3940  3950.1  3960.1    3970    4000    4040
    4120    4160    4250    4270    4350    4470    4490    4510    4520    4530
    4540    4550    4580  4610.1    4640    4670    4700    4760  4760.1    4790
    4810  4813.4  4813.5  4861.1  4880.9  4895.2    4921  4934.5  4953.6  4961.8
  4981.4 4982.11 4982.21 4982.29  4982.4  4982.5 4982.61    4991  4994.3  4995.7
  4996.1  4996.3 4996.41  5003.3  5003.7  5004.4  5004.7  5006.4  5009.9 5017.69
  5017.8 5017.91 5017.99 5018.11  5018.2  5018.4  5025.5  5027.7  5065.6  5076.2
  5103.3  5118.8  5124.3  5124.4    5150  5210.1  5235.6  5272.3  5275.6  5415.6
  5455.6  5465.6  5475.6  5485.6  5505.6  5512.3  5525.6  5535.6  5575.6  5602.3
  5612.3  5615.6  5627.8  5645.6  5705.6  5735.6  5742.3  5765.6  5775.6  5802.3
  5807.6  5812.3  5815.6  5842.3  5852.3  5872.3
    98.4    97.6   97.91   98.08   98.11   98.11   97.91   97.98   98.11   97.96
   97.51   97.51   97.21   96.63    96.6    96.6      97   97.05    97.1    97.1
    96.7    96.7   96.61   96.67    96.9   97.01    96.9   96.73   96.55   96.48
   96.41   96.21   96.91   96.41   96.81   96.61   97.01   96.81   96.01   96.21
   95.92   96.01   96.41   97.11   97.41   96.41   96.41    95.8   95.94   96.08
   96.22   96.36    96.5    96.5   96.38   96.25      96   96.21   96.41   96.51
   96.41   96.71   96.05    96.1   95.81    95.6    95.4    95.4    95.4   96.01
   95.81   96.11   95.61    95.4    95.4   95.61    95.4   95.51    95.4    95.4
    95.4    95.4   95.61    95.4    95.4    95.4   95.61    95.4    95.4   95.62
   95.77    95.8    95.8   95.85   95.79   95.75   95.59   95.52   95.41   95.49
   95.69    95.7    95.7    95.7   96.19   96.19   96.19   96.19   96.19   96.19
   96.19   96.19   96.19   96.19   96.19   96.19   96.19   96.19   96.19   96.19
   96.19   95.69   95.69   95.69   95.69   95.69   95.65   95.64   95.44   95.44
   95.45   95.47   95.48   95.48   95.22   94.87   94.81    94.8    94.8   94.92
   94.95   94.96   95.01   95.01   94.99      95   95.01   95.01   95.61   95.61
   95.61   95.61   95.37   95.01   95.01   94.81   94.83   94.91   94.71    94.9
   94.95   94.99   95.01   94.74   94.64   94.44
                                                                                
                                                                                
                                                                                
                                                                                
                                                                                
                                                                                
                                                                                
                                                                                
                                                                                
                                                                           94.62
   94.76   94.43   94.38   94.34   94.29   94.24    94.2    94.2    94.2    94.2
    94.2    94.2    94.2   94.19   94.19   94.19   94.19   94.19   94.19   94.19
   94.19   94.19   94.19   93.78   93.82   93.91   94.05   94.07
                                                                                
                                                                                
                                                                                
                                                
    2290    2360  2450.1  2500.1    2510  2510.1    2530  2550.1    2590  2600.1
    2630  2630.1    2640    2650    2660  2660.1  2670.1    2680    2690  2690.1
    2700  2700.1    2720  2730.1  2770.1    2790  2820.1  2870.1  2920.1  2940.1
    2960    2980    3050    3120    3170    3180    3220    3240    3270    3360
    3380    3390    3400    3410    3420    3480    3530  3560.1    3570    3580
    3590    3600    3610  3610.1    3620    3630  3650.1    3660  3680.1    3690
    3710    3730    3770  3850.1    3940  3950.1  3960.1    3970    4000    4040
    4120    4160    4250    4270    4350    4470    4490    4510    4520    4530
    4540    4550    4580  4610.1    4640    4670    4700    4760  4760.1    4790
    4810  4813.4  4813.5  4861.1  4880.9  4895.2    4921  4934.5  4953.6  4961.8
  4981.4 4982.11 4982.21 4982.29  4982.4  4982.5 4982.61    4991  4994.3  4995.7
  4996.1  4996.3 4996.41  5003.3  5003.7  5004.4  5004.7  5006.4  5009.9 5017.69
  5017.8 5017.91 5017.99 5018.11  5018.2  5018.4  5025.5  5027.7  5065.6  5076.2
  5103.3  5118.8  5124.3  5124.4    5150  5210.1  5235.6  5272.3  5275.6  5415.6
  5455.6  5465.6  5475.6  5485.6  5505.6  5512.3  5525.6  5535.6  5575.6  5602.3
  5612.3  5615.6  5627.8  5645.6  5705.6  5735.6  5742.3  5765.6  5775.6  5802.3
  5807.6  5812.3  5815.6  5842.3  5852.3  5872.3
    98.4    97.6   97.91   98.08   98.11   98.11   97.91   97.98   98.11   97.96
   97.51   97.51   97.21   96.63    96.6    96.6      97   97.05    97.1    97.1
    96.7    96.7   96.61   96.67    96.9   97.01    96.9   96.73   96.55   96.48
   96.41   96.21   96.91   96.41   96.81   96.61   97.01   96.81   96.01   96.21
   95.92   96.01   96.41   97.11   97.41   96.41   96.41    95.8   95.94   96.08
   96.22   96.36    96.5    96.5   96.38   96.25      96   96.21   96.41   96.51
   96.41   96.71   96.05    96.1   95.81    95.6    95.4    95.4    95.4   96.01
   95.81   96.11   95.61    95.4    95.4   95.61    95.4   95.51    95.4    95.4
    95.4    95.4   95.61    95.4    95.4    95.4   95.61    95.4    95.4   95.62
   95.77    95.8    95.8   95.85   95.79   95.75   95.59   95.52   95.41   95.49
   95.69    95.7    95.7    95.7   96.19   96.19   96.19   96.19   96.19   96.19
   96.19   96.19   96.19   96.19   96.19   96.19   96.19   96.19   96.19   96.19
   96.19   95.69   95.69   95.69   95.69   95.69   95.65   95.64   95.44   95.44
   95.45   95.47   95.48   95.48   95.22   94.87   94.81    94.8    94.8   94.92
   94.95   94.96   95.01   95.01   94.99      95   95.01   95.01   95.61   95.61
   95.61   95.61   95.37   95.01   95.01   94.81   94.83   94.91   94.71    94.9
   94.95   94.99   95.01   94.74   94.64   94.44
                                                                                
                                                                                
                                                                                
                                                                                
                                                                                
                                                                                
                                                                                
                                                                                
                                                                                
                                                                           94.62
      94    94.2    94.2    94.2    94.2    94.2    94.2    94.2    94.2    94.2
    94.2    94.2    94.2   94.19   94.19   94.19   94.19   94.19   94.19   94.19
   94.19   94.19   93.53    93.6    93.6    93.6   94.05   94.07
                                                                                
                                                                                
                                                                                
                                                
Pier Skew, UpSta & Num, DnSta & Num=  ,4994.3, 2 ,4994.3, 2 , 0 , 0 , 0 ,,
     1.5     1.5
   86.81    95.2
     1.5     1.5
   86.61      95
Pier Skew, UpSta & Num, DnSta & Num=  ,5006.4, 2 ,5006.4, 2 , 0 , 0 , 0 ,,
     1.5     1.5
   86.84   95.19
     1.5     1.5
   86.64   94.99
BR Coef= 1 , 1 , 1 ,1.05, 0 ,,,.8,0,1.2,0,
WSPro=,,,, 1 ,,,, 0 ,,,, 0 ,,,,-1 ,-1 ,-1 , 0 , 0 , 0 , 0 , 0
BC Design=,, 0 ,, 0 ,,,,,,
BC HTab HWMax=98.41

Type RM Length L Ch R = 1 ,31163.3 ,98.3,104.8,99.3
BEGIN DESCRIPTION:
HOLLOW HOOK RD - XS 2
Levees are not FEMA regulated levees, only RAS levees to prevent spilling into E115-09-00.
END DESCRIPTION:
XS GIS Cut Line= 3
      3064362.71      13869875.9        3064477.     13866931.78
      3064481.82     13866303.72
#Sta/Elev= 30
    2290   98.41    2360   97.61    2590   98.11    2700   95.81    2790   97.01
    2980   96.21    3220   97.01    3380   95.91    3420   97.41    3590   95.01
    3730   96.71    3970   95.21    4160   96.11    4510   95.51    4530   94.61
    4580   95.61    4810   94.91  4813.5   95.81  4961.8   94.63  4981.4   94.57
  4996.1   87.13 4996.41   82.74  5003.3   83.15  5004.4   87.06  5018.4   93.72
  5025.5   94.06  5118.8    94.5  5124.4   95.49  5742.3   94.83 5864.49   94.52
#Mann= 4 ,-1 , 0
    2290     .08       0  4961.8     .04       0  5025.5     .99       0
  5742.3    .015       0
#XS Ineff= 2 ,-1
    2290    4972    99.5  5018.4  5872.3      96
Permanent Ineff=
       F       F
Bank Sta=4981.4,5018.4
XS Rating Curve= 0
Exp/Cntr=.5,.3

Type RM Length L Ch R = 1 ,31058.5 ,184.2,182.4,180.6
BEGIN DESCRIPTION:
HOLLOW HOOK RD - XS 1
Interplotated channel, LIDAR overbanks
Levees are not FEMA regulated levees, only RAS levees to prevent spilling into E115-09-00.
END DESCRIPTION:
XS GIS Cut Line= 3
       3064460.8     13869881.98      3064575.09     13866937.85
       3064579.9     13866307.76
#Sta/Elev= 30
  2291.8   97.77  2511.8   97.84  2661.8   96.23  3441.8   96.55  3561.8   96.12
  3591.8   95.05  3641.8   95.18  3661.8   96.58  3681.8   96.68  3761.8   95.35
  4291.8   96.05  4501.8   94.63  4831.8   95.45  4961.8    94.3 4977.12   94.26
  4994.7   87.48 4996.92   86.18 4997.37   82.89 5005.29   83.76 5006.56   86.97
 5018.96   92.38    5027  92.906  5051.8   94.67  5091.8   95.07  5191.8   94.18
  5238.1   95.09  5338.1   94.35  5758.1    94.8  5818.1   95.04 5868.25   94.09
#Mann= 4 ,-1 , 0
  2291.8     .08       0  4961.8     .04       0    5027     .99       0
  5758.1    .015       0
#XS Ineff= 2 ,-1
  2291.8 4969.69    99.5 5018.96  5888.1      97
Permanent Ineff=
       F       F
Bank Sta=4977.12,5018.96
XS Rating Curve= 0
Exp/Cntr=.3,.1

Type RM Length L Ch R = 1 ,30876.1 ,72.1,103.9,127.7
BEGIN DESCRIPTION:
SP RR (2) - XS 4
Interplotated channel, LIDAR overbanks
Levees are not FEMA regulated levees, only RAS levees to prevent spilling into E115-09-00.
END DESCRIPTION:
XS GIS Cut Line= 6
      3064962.76     13869692.46      3064747.73     13867882.05
      3064625.65     13867420.64      3064748.06     13867120.09
      3064874.45     13866934.04      3064850.06     13866324.16
#Sta/Elev= 30
  2420.1   97.05  2560.1   97.77  2590.1   96.51  2910.1   97.26    3600  95.134
  3830.1   94.08  3860.1   95.03  4150.1   95.45  4170.1    94.2  4343.2   96.14
    4530  96.141  4653.2   95.25  4720.5   92.44  4780.5   95.84  4941.3   96.16
 4968.37    94.4 4983.71   91.03    4995    86.6 4999.05   83.16 5005.86   83.42
 5011.71   87.38  5041.3    94.3  5051.3   95.29  5108.1   96.47  5138.1   96.05
  5178.1   93.25    5283   94.03    5533   96.09    5593   93.75    5893   93.27
#Mann= 8 ,-1 , 0
  2420.1     .05       0  2590.1     .08       0    3600     .05       0
    4530     .12       0  4653.2     .05       0  4941.3     .04       0
  5051.3    .045       0    5283    .015       0
#XS Ineff= 2 ,-1
  2420.1  4941.3    99.5  5041.3    5893      96
Permanent Ineff=
       F       F
Bank Sta=4941.3,5041.3
XS Rating Curve= 0
Exp/Cntr=.5,.3

Type RM Length L Ch R = 1 ,30772.2 ,57.3,56,59.7
BEGIN DESCRIPTION:
SP RR (2) - XS 3
Levees are not FEMA regulated levees, only RAS levees to prevent spilling into E115-09-00.
END DESCRIPTION:
XS GIS Cut Line= 6
      3065065.19      13869697.6      3064850.16     13867887.25
      3064719.58     13867393.73      3064978.44     13866978.05
      3064953.65     13866358.13       3064952.6     13866331.88
#Sta/Elev= 30
2767.907   98.312901.621   99.492918.942   97.992996.884   96.593249.937   96.03
3325.974   96.993716.464   95.594261.281   94.494391.358    96.1 4419.85   97.69
4601.715   97.894878.844   94.994959.817   98.474962.588   94.754981.295   91.26
    5000   83.315007.881   83.585013.424   87.515022.864   88.645028.839   92.07
5034.295   97.735034.902   97.695069.196   95.58 5104.01   95.695138.651   93.29
5190.613   94.59 5473.09   96.09 5573.09   92.79 5709.49   93.34 5786.09   94.19
#Mann= 7 ,-1 , 0
2767.907     .05       03249.937     .08       03716.464     .05       0
4391.358     .12       04959.817    .045       05034.902     .07       0
 5709.49    .015       0
#XS Ineff= 3 ,-1
 2767.91 4959.82      99 4959.82 4963.37      94  5034.3 5803.09      96
Permanent Ineff=
       F       F       F
Bank Sta=4959.817,5034.295
XS Rating Curve= 0
Skew Angle= 30
Exp/Cntr=.5,.3