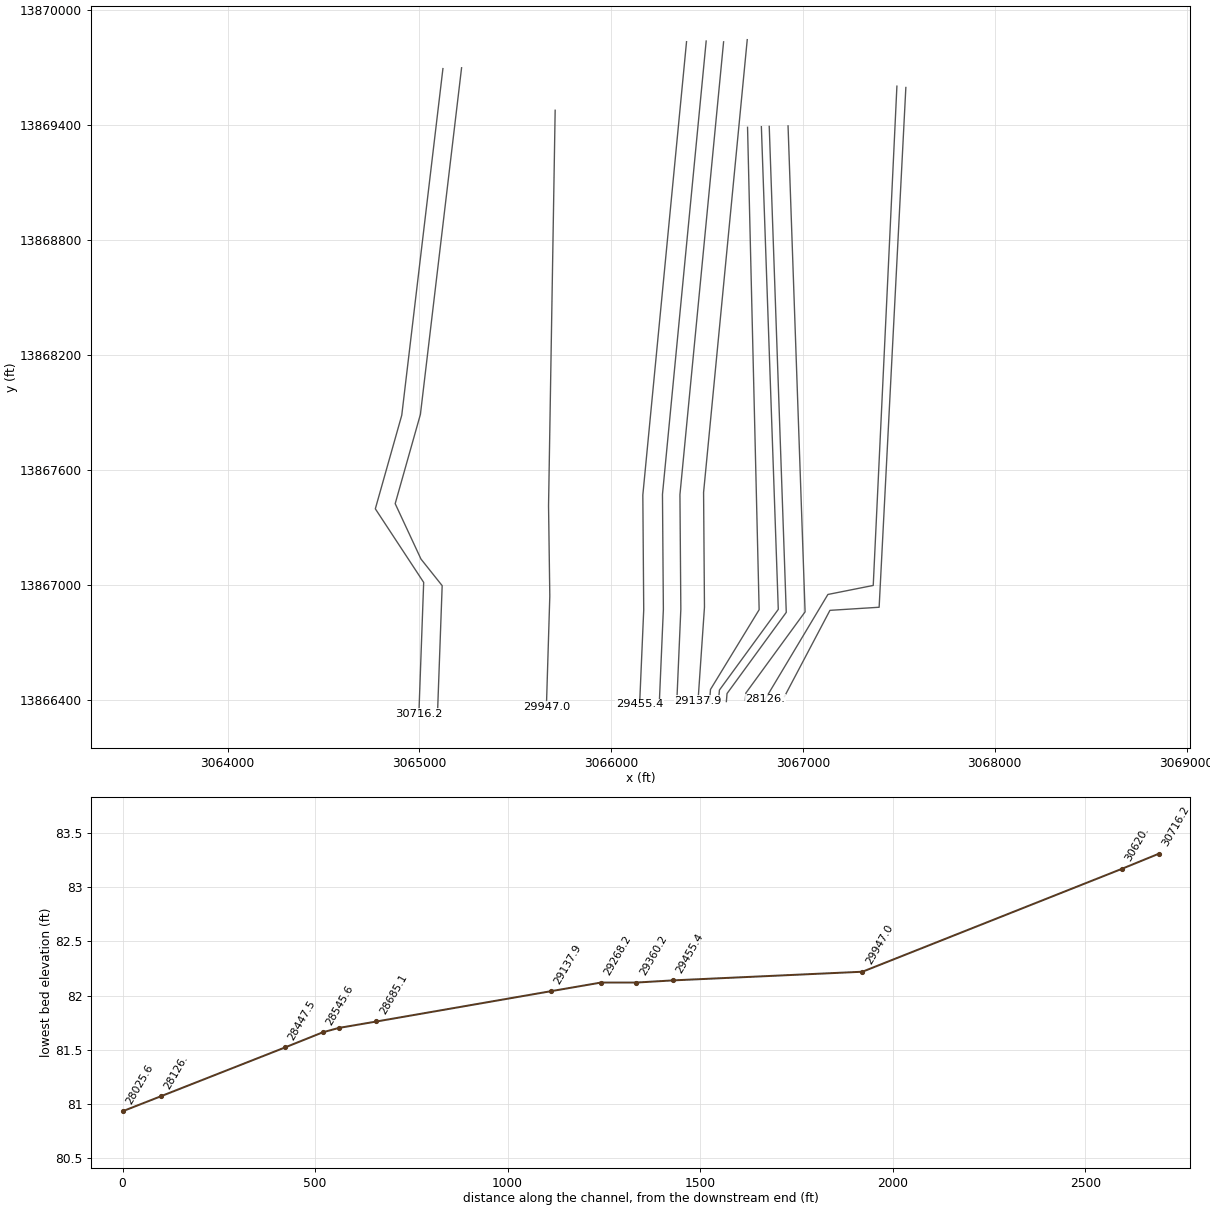
HEC-RAS study E115-00-00.prj: E115-00-00

--- E115-00-00.g01 (geometry) --- (continued)

Type RM Length L Ch R = 3 ,30744.2 ,,,
BEGIN DESCRIPTION:
SOUTHERN PACIFIC RR
Structure ID: E115-00-00-23
Ground data is not skewed on the right overbank
END DESCRIPTION:
Bridge Culvert--1,0,-1,-1, 0
Deck Dist Width WeirC Skew NumUp NumDn MinLoCord MaxHiCord MaxSubmerge Is_Ogee
10,36,2.6,30, 60, 60, , , .95, 0, ,,,
2767.9083003.6384294.0184419.8484701.1384735.7784958.8584958.9484972.0384972.118
5029.2685034.2985035.4185035.5185115.1785142.8085473.0885573.0885913.0886033.088
6083.0886213.0886373.0886393.0886473.0886513.0886613.0886653.0886743.0886773.088
6963.0887093.0887203.0887303.0887383.0887603.0887653.0887753.0887823.0887883.088
7953.0887993.0888053.0888213.0888303.0888373.0888403.0888413.0888453.0888463.088
8483.0888553.0888673.0888713.0888753.0889243.0889273.0889343.0889373.0889535.888
   98.31    96.6   94.76   97.71    97.9    96.7   99.38  104.48  104.47  104.47
  104.46  104.47  104.47   99.37   98.54   93.31   96.09   92.79   94.59   93.99
   91.19   91.19   97.99   97.59   90.89   92.59   89.99   91.59   90.29   92.19
   94.69   92.39   93.69   91.69   93.59   92.69   94.19   91.49   94.29   94.19
   93.79   91.39   93.29   92.29   94.49   93.99   88.39   84.29   86.99   89.79
   92.39   94.19   94.09   92.59   93.99   93.66   91.29   91.02   92.62   93.25
                                                                           92.95
   92.53
                                                                                
                                                                                
                                                                                
                                                                                
2767.9083003.6384294.0184419.8484701.1384735.7784958.8584958.9484972.0384972.118
5029.2685034.2985035.4185035.5185115.1785142.8085473.0885573.0885913.0886033.088
6083.0886213.0886373.0886393.0886473.0886513.0886613.0886653.0886743.0886773.088
6963.0887093.0887203.0887303.0887383.0887603.0887653.0887753.0887823.0887883.088
7953.0887993.0888053.0888213.0888303.0888373.0888403.0888413.0888453.0888463.088
8483.0888553.0888673.0888713.0888753.0889243.0889273.0889343.0889373.0889535.888
   98.31    96.6   94.76   97.71    97.9    96.7   99.38  104.48  104.47  104.47
  104.46  104.47  104.47   99.37   98.54   93.31   96.09   92.79   94.59   93.99
   91.19   91.19   97.99   97.59   90.89   92.59   89.99   91.59   90.29   92.19
   94.69   92.39   93.69   91.69   93.59   92.69   94.19   91.49   94.29   94.19
   93.79   91.39   93.29   92.29   94.49   93.99   88.39   84.29   86.99   89.79
   92.39   94.19   94.09   92.59   93.99   93.66   91.29   91.02   92.62   93.25
                                                                           92.95
   92.53
                                                                                
                                                                                
                                                                                
                                                                                
Pier Skew, UpSta & Num, DnSta & Num=  ,4989.695, 2 ,4989.695, 2 , 0 , 0 , 0 ,,
     1.2     1.2
   86.46   93.86
     1.2     1.2
   86.55   93.95
Pier Skew, UpSta & Num, DnSta & Num=  ,5011.952, 2 ,5011.952, 2 , 0 , 0 , 0 ,,
     1.2     1.2
   84.93   93.85
     1.2     1.2
   85.02   93.94
BR Coef= 1 , 1 , 1 ,1.25, 0 ,,,.8,-1,2,0,
WSPro=,,,, 1 ,,,, 0 ,,,, 0 ,,,,-1 ,-1 ,-1 , 0 , 0 , 0 , 0 , 0
BC Design=,, 0 ,, 0 ,,,,,,
BC HTab HWMax=101.19

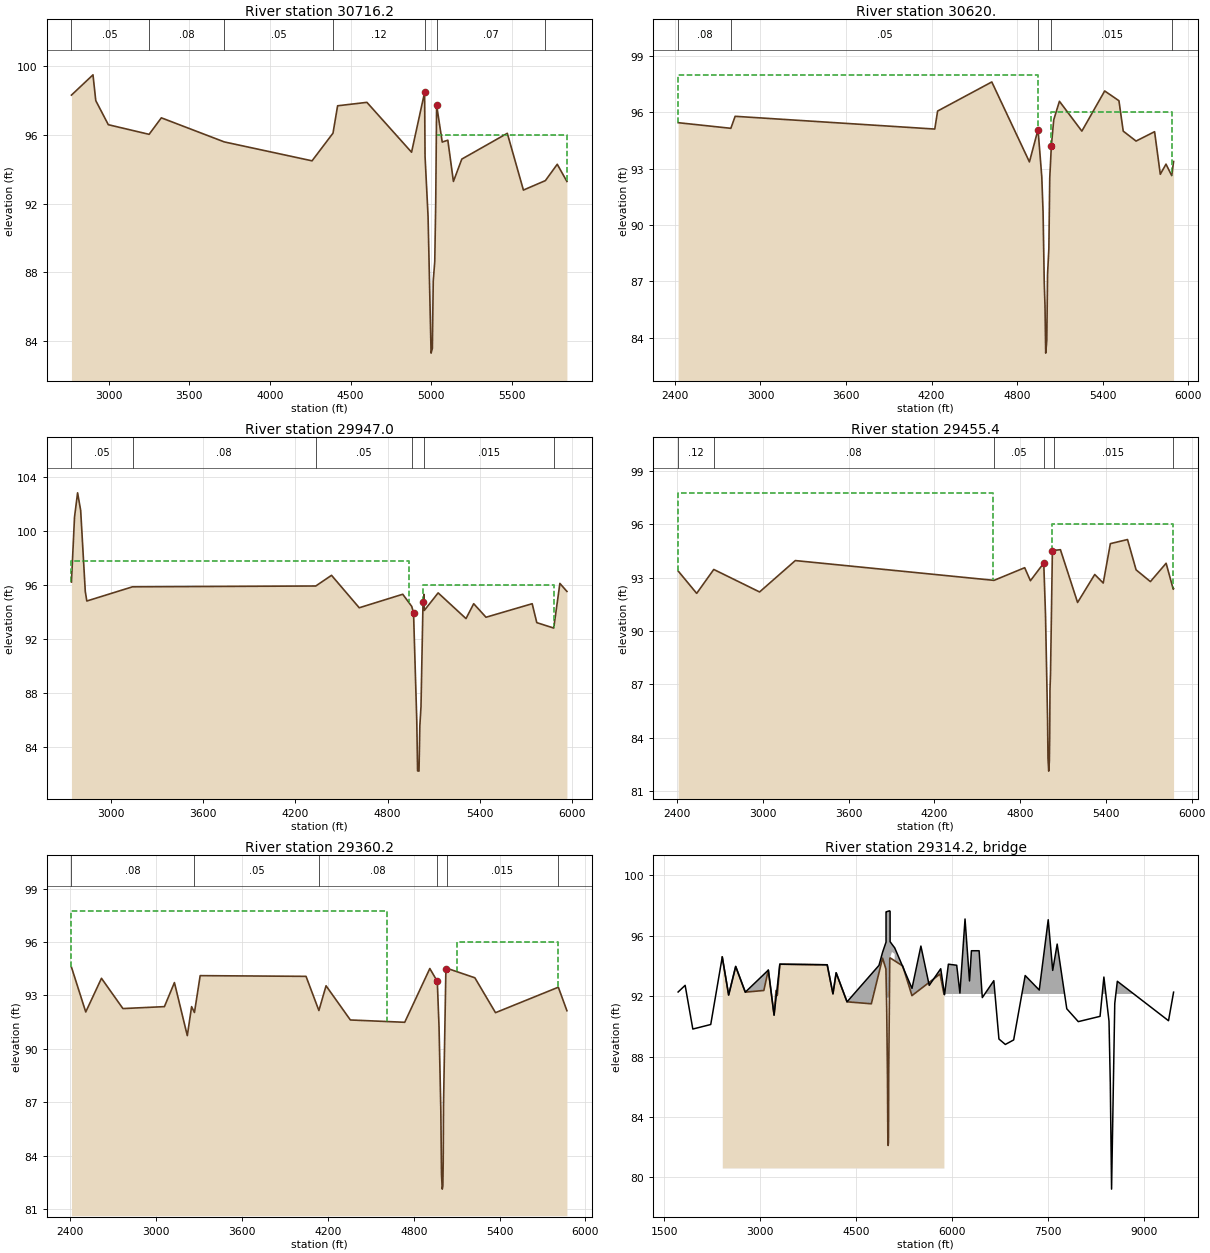
Type RM Length L Ch R = 1 ,30716.2 ,125.2,96.2,71.8
BEGIN DESCRIPTION:
SP RR (2) - XS 2
Levees are not FEMA regulated levees, only RAS levees to prevent spilling into E115-09-00.
END DESCRIPTION:
XS GIS Cut Line= 5
      3065122.67      13869692.4      3064908.02     13867885.12
      3064770.17     13867397.11      3065022.28     13867013.46
      3064997.25     13866327.92
#Sta/Elev= 30
2767.907   98.312901.621   99.492918.942   97.992996.884   96.593249.937   96.03
3325.974   96.993716.464   95.594261.281   94.494391.358    96.1 4419.85   97.69
4601.715   97.894878.844   94.994959.817   98.474962.588   94.754981.295   91.26
    5000   83.315007.881   83.585013.424   87.515022.864   88.645028.839   92.07
5034.295   97.735069.196   95.58 5104.01   95.695138.651   93.295190.613   94.59
 5473.09   96.09 5573.09   92.79 5709.49   93.34 5783.09   94.29 5843.09   93.29
#Mann= 7 ,-1 , 0
2767.907     .05       03249.937     .08       03716.464     .05       0
4391.358     .12       04959.817     .04       05034.295     .07       0
 5709.49    .015       0
#XS Ineff= 3 ,-1
 2767.91 4959.82      98 4959.82 4963.37      94  5034.3 5873.09      96
Permanent Ineff=
       F       F       F
Bank Sta=4959.817,5034.295
XS Rating Curve= 0
Skew Angle= 30
Exp/Cntr=.5,.3

Type RM Length L Ch R = 1 ,30620.  ,673.2,673,670.2
BEGIN DESCRIPTION:
SP RR (2) - XS 1
Interplotated channel, LIDAR overbanks
Levees are not FEMA regulated levees, only RAS levees to prevent spilling into E115-09-00.
END DESCRIPTION:
XS GIS Cut Line= 6
       3065219.9     13869696.76      3065005.24     13867889.46
      3064873.74     13867423.91      3065008.18     13867135.12
      3065118.72     13866996.37      3065094.56     13866333.92
#Sta/Elev= 30
  2422.6   95.45  2792.6   95.15  2822.6   95.79  4222.6   95.11  4242.6   96.07
  4622.6   97.62  4886.4   93.36  4946.8   95.08    4973   92.58 4982.12   90.69
  4990.4   86.92 4995.69   85.69 5000.55   83.17  5008.2   83.84 5013.57   87.38
 5022.73   88.74 5028.95   92.49  5040.2   94.21  5056.8    95.6  5096.8   96.59
  5254.2      95  5414.2   97.14  5514.2   96.62  5544.2      95  5634.2   94.47
  5764.2   94.97  5804.2    92.7  5844.2   93.24  5884.2   92.63 5897.37   93.38
#Mann= 5 ,-1 , 0
  2422.6     .08       0  2792.6     .05       0  4946.8     .04       0
  5040.2    .015       0  5884.2     .05       0
#XS Ineff= 2 ,-1
  2422.6  4946.8      98  5040.2  5884.2      96
Permanent Ineff=
       F       F
Bank Sta=4946.8,5040.2
XS Rating Curve= 0
Exp/Cntr=.3,.1

Type RM Length L Ch R = 1 ,29947.0 ,491.4,491.6,490.9
BEGIN DESCRIPTION:
Cross Section x22
Located At: US WINDFERN
Levees are not FEMA regulated levees, only RAS levees to prevent spilling into E115-09-00.
END DESCRIPTION:
XS GIS Cut Line= 4
      3065707.87      13869475.2      3065673.37     13867412.81
      3065679.93     13866941.88      3065662.25     13866366.04
#Sta/Elev= 30
    2746    96.2    2766     101    2786   102.8    2806   101.5    2836    95.5
    2846    94.8  3142.8   95.85  4333.5   95.91    4436    96.7    4616    94.3
  4898.8    95.3  4957.3    94.4    4969   93.91  4989.9   85.96  4995.2   82.24
  5004.4   82.22  5009.8   85.55  5017.3   86.97  5030.5   94.72  5036.8   95.29
  5038.8    94.1  5128.8    95.4  5309.8    93.5  5359.8    94.6  5439.8    93.6
  5739.8    94.6  5769.8    93.2  5879.8    92.8  5919.8    96.1 5965.56   95.51
#Mann= 6 ,-1 , 0
    2746     .05       0  3142.8     .08       0  4333.5     .05       0
  4957.3     .04       0  5036.8    .015       0  5879.8     .05       0
#XS Ineff= 2 ,-1
    2746  4938.8   97.75  5030.5  5879.5      96
Permanent Ineff=
       F       F
Bank Sta=4969,5030.5
XS Rating Curve= 0
Exp/Cntr=.3,.1

Type RM Length L Ch R = 1 ,29455.4 ,101.5,95.2,102.5
BEGIN DESCRIPTION:
WINFERN RD - XS 4
Interplotated channel, LIDAR overbanks
Levees are not FEMA regulated levees, only RAS levees to prevent spilling into E115-09-00.
Cross-Section would need to be extended across E117-00-00 channel in order to contain all flood events.
END DESCRIPTION:
XS GIS Cut Line= 4
      3066392.86     13869832.71      3066164.96     13867469.12
      3066169.62      13866869.8      3066148.22     13866378.29
#Sta/Elev= 30
  2407.5   93.37  2537.5   92.11    2657  93.452  2977.5   92.19  3227.5   93.95
  4617.5   92.84  4832.1   93.55  4872.1   92.82 4965.48   93.81 4977.73   90.91
 4992.19   85.02 4995.01   82.87 5000.13   82.14 5004.54   82.69 5007.05   84.07
 5009.06   86.72 5012.82   87.63 5025.81    94.5    5035   94.52  5082.1   94.56
  5202.1    91.6  5322.1   93.17  5381.4   92.69  5431.4    94.9  5551.4   95.13
  5611.4   93.43  5711.4   92.77  5821.4    93.8  5871.4   92.34 5873.62   92.38
#Mann= 6 ,-1 , 0
  2407.5     .12       0    2657     .08       0  4617.5     .05       0
 4965.48     .04       0    5035    .015       0  5871.4     .05       0
#XS Ineff= 2 ,-1
  2407.5    4610   97.75 5025.81  5871.4      96
Permanent Ineff=
       F       F
Bank Sta=4965.48,5025.81
XS Rating Curve= 0
Exp/Cntr=.5,.3

Type RM Length L Ch R = 1 ,29360.2 ,90.1,92,91.1
BEGIN DESCRIPTION:
WINFERN RD - XS 3
Levees are not FEMA regulated levees, only RAS levees to prevent spilling into E115-09-00.
END DESCRIPTION:
XS GIS Cut Line= 4
      3066495.29      13869836.1      3066267.39     13867472.59
      3066272.05     13866873.27      3066250.75     13866381.97
#Sta/Elev= 30
  2407.1   94.59  2507.1   92.07  2617.1   93.96  2767.1   92.26  3057.1   92.37
  3127.1   93.72  3217.1   90.74  3247.1   92.37  3267.1   92.04  3307.1   94.11
  4047.1   94.07  4137.1   92.15  4187.1   93.54  4357.1   91.62  4737.1   91.49
  4912.6   94.51  4964.8   93.79    4977   91.23  4989.4   86.59  4994.2   82.98
  4999.3   82.12  5003.7   82.29  5006.2   83.72  5008.2   86.81  5024.9   94.46
 5029.79   94.53  5227.4   93.99  5371.7   92.03    5811   93.46    5871   92.14
#Mann= 6 ,-1 , 0
  2407.1     .08       0  3267.1     .05       0  4137.1     .08       0
  4964.8     .04       0 5029.79    .015       0    5811     .05       0
#XS Ineff= 4 ,-1
  2407.1    4610   97.75  4912.6    4963      93    5030    5100   92.42
    5100    5811      96
Permanent Ineff=
       F       T       F       F
Bank Sta=4964.8,5024.9
XS Rating Curve= 0
Exp/Cntr=.5,.3

Type RM Length L Ch R = 3 ,29314.2 ,,,
BEGIN DESCRIPTION:
WINDFERN ROAD
Structure ID: E115-00-00-22
END DESCRIPTION:
Bridge Culvert--1,0,-1,-1, 0
Deck Dist Width WeirC Skew NumUp NumDn MinLoCord MaxHiCord MaxSubmerge Is_Ogee
10,72,2.6,0, 60, 60, , , .95, 0, ,,,
  1717.1  1827.1  1947.1  2227.1  2407.1  2507.1  2617.1  2767.1  3127.1  3217.1
  3307.1  4047.1  4137.1  4187.1  4357.1  4855.9  4912.6 4966.49  4966.6 4973.91
    5020  5024.9  5029.9 5030.01  5059.2    5102  5102.1  5372.1  5511.4  5641.4
  5821.4    5881    5941    6071    6121    6201    6271    6301    6421    6471
    6651    6731    6831    6961    7141    7361    7501    7571    7641    7791
    7971    8311    8371    8451    8471    8491    8541    8581    9381  9460.1
   92.27   92.71   89.82   90.12   94.59   92.07   93.96   92.26   93.72   90.74
   94.11   94.07   92.15   93.54   91.62   94.03    94.9   95.57   97.57   97.58
   97.64   97.63    97.6    95.6   95.43   95.19   95.19   92.51   95.31   92.71
   93.81   92.09   94.11   94.04    92.2    97.1      93      95      95    91.9
   93.02   89.16    88.8    89.1   93.36    92.4   97.05    93.7   95.44   91.16
   90.31   90.66   93.26   90.34   86.24   79.23   91.52   92.98   90.37   92.26
                                                                                
                                                   94.51   93.44   93.41   91.88
   91.92   94.46   94.53   94.53   94.92   94.79
                                                                                
                                                                                
                                                                                
  1717.1  1827.1  1947.1  2227.1  2407.1  2507.1  2617.1  2767.1  3127.1  3217.1
  3307.1  4047.1  4137.1  4187.1  4357.1  4855.9  4912.6 4966.49  4966.6 4973.91
    5020  5024.9  5029.9 5030.01  5059.2    5102  5102.1  5372.1  5511.4  5641.4
  5821.4    5881    5941    6071    6121    6201    6271    6301    6421    6471
    6651    6731    6831    6961    7141    7361    7501    7571    7641    7791
    7971    8311    8371    8451    8471    8491    8541    8581    9381  9460.1
   92.27   92.71   89.82   90.12   94.59   92.07   93.96   92.26   93.72   90.74
   94.11   94.07   92.15   93.54   91.62   94.03    94.9   95.57   97.57   97.58
   97.64   97.63    97.6    95.6   95.43   95.19   95.19   92.51   95.31   92.71
   93.81   92.09   94.11   94.04    92.2    97.1      93      95      95    91.9
   93.02   89.16    88.8    89.1   93.36    92.4   97.05    93.7   95.44   91.16
   90.31   90.66   93.26   90.34   86.24   79.23   91.52   92.98   90.37   92.26
                                                                                
                                                   94.51   93.44   93.41   91.88
   91.92   94.46   94.53   94.53   94.92   94.79
                                                                                
                                                                                
                                                                                
BR Coef= 1 , 1 , 0 ,1.25, 0 ,,,.8,-1,2,0,
WSPro=,,,, 1 ,,,, 0 ,,,, 0 ,,,,-1 ,-1 ,-1 , 0 , 0 , 0 , 0 , 0
BC Design=,, 0 ,, 0 ,,,,,,
BC HTab HWMax=99

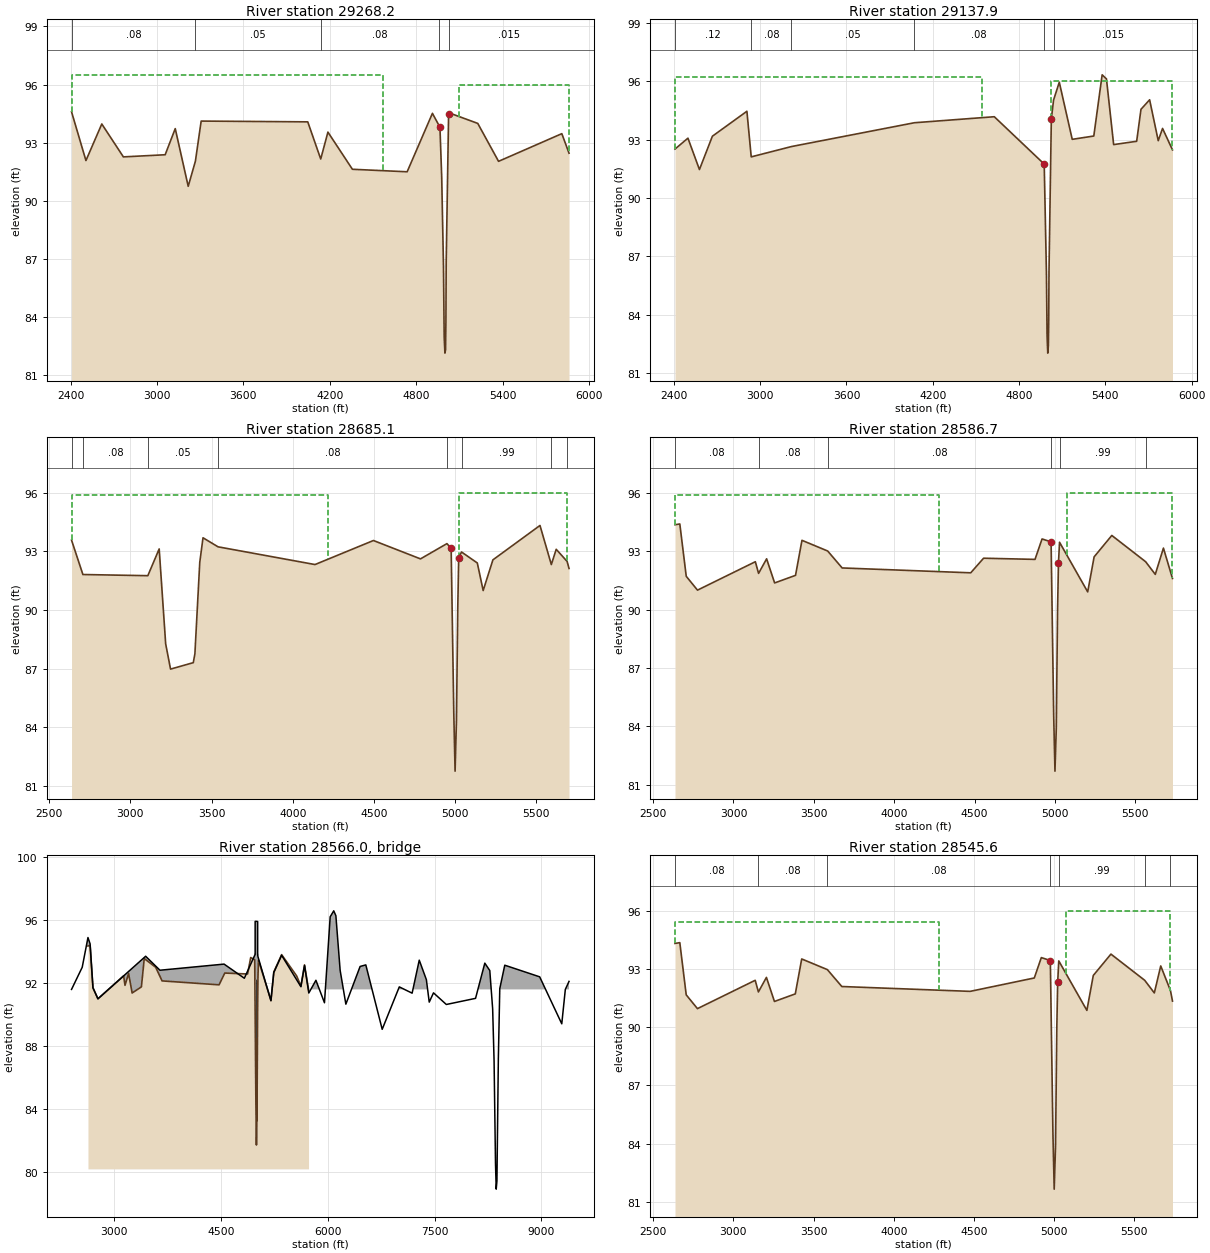
Type RM Length L Ch R = 1 ,29268.2 ,123.5,130.3,123.4
BEGIN DESCRIPTION:
WINFERN RD - XS 2
Levees are not FEMA regulated levees, only RAS levees to prevent spilling into E115-09-00.
END DESCRIPTION:
XS GIS Cut Line= 4
       3066586.1       13869832.      3066358.45     13867471.13
       3066363.1     13866873.13      3066342.07     13866390.31
#Sta/Elev= 30
  2407.1   94.59  2507.1   92.07  2617.1   93.96  2767.1   92.26  3057.1   92.37
  3127.1   93.72  3217.1   90.74  3267.1   92.04  3307.1   94.11  4047.1   94.07
  4137.1   92.15  4187.1   93.54  4357.1   91.62  4737.1   91.49  4912.6   94.51
  4960.6   93.85  4964.8   93.79    4977   91.23  4989.4   86.59  4994.2   82.98
  4999.3   82.12  5003.7   82.29  5006.2   83.72  5008.2   86.81  5024.9   94.46
 5029.79   94.53  5227.4   93.99  5371.7   92.03    5811   93.46    5861   92.45
#Mann= 5 ,-1 , 0
  2407.1     .08       0  3267.1     .05       0  4137.1     .08       0
  4960.6     .04       0 5029.79    .015       0
#XS Ineff= 4 ,-1
  2407.1    4570    96.5  4912.6    4963      93    5030    5100   92.42
    5100    5871      96
Permanent Ineff=
       F       F       F       F
Bank Sta=4964.8,5024.9
XS Rating Curve= 0
Exp/Cntr=.5,.3

Type RM Length L Ch R = 1 ,29137.9 ,448.1,452.8,446.7
BEGIN DESCRIPTION:
WINFERN RD - XS 1
Interplotated channel, LIDAR overbanks
Levees are not FEMA regulated levees, only RAS levees to prevent spilling into E115-09-00.
Cross-Section would need to be extended across E117-00-00 channel in order to contain all flood events.
END DESCRIPTION:
XS GIS Cut Line= 4
      3066709.37     13869843.37      3066481.72     13867482.41
      3066486.36     13866884.41       3066452.8     13866396.14
#Sta/Elev= 30
  2407.8   92.51  2497.8   93.07  2577.8   91.46  2667.8   93.17  2907.8   94.45
  2937.8   92.11  3217.8   92.64    4072  93.861  4627.8   94.17 4974.86   91.74
 4990.49    86.1 4994.72   82.95 4999.53   82.04  5003.8   82.43 5006.23   83.71
 5008.17   86.24 5024.38   94.06    5040  95.029  5079.7   95.94  5169.7   93.01
  5319.7   93.18  5377.7   96.32  5407.7   96.11  5457.7   92.74  5617.7   92.91
  5647.7   94.55  5707.7   95.04  5767.7   92.94  5797.7   93.57 5866.74   92.47
#Mann= 6 ,-1 , 0
  2407.8     .12       0  2937.8     .08       0  3217.8     .05       0
    4072     .08       0 4974.86     .04       0    5040    .015       0
#XS Ineff= 2 ,-1
  2407.8    4540    96.2 5024.38  5877.7      96
Permanent Ineff=
       F       F
Bank Sta=4974.86,5024.38
XS Rating Curve= 0
Exp/Cntr=.3,.1

Type RM Length L Ch R = 1 ,28685.1 ,102.9,98.4,98.6
BEGIN DESCRIPTION:
PALO PINTO - XS 4
Interplotated channel, LIDAR overbanks
Levees are not FEMA regulated levees, only RAS levees to prevent spilling into E115-09-00.
Cross-Section would need to be extended across E117-00-00 channel in order to contain all flood events.
END DESCRIPTION:
XS GIS Cut Line= 4
      3066710.98     13869386.33      3066771.44     13866870.99
      3066517.69      13866455.1      3066512.81      13866393.1
#Sta/Elev= 30
  2637.3   93.58  2707.3   91.82  3107.3   91.76  3177.3   93.13  3217.3   88.27
  3247.3   86.98  3387.3   87.31  3397.3   87.76  3427.3   92.44  3447.3    93.7
    3540  93.237  4137.3   92.33  4497.3   93.56  4787.3   92.62    4950    93.4
 4976.12   93.17 4992.49    84.7 5000.33   81.76 5008.84   84.34 5016.95   90.15
 5022.59   92.67    5040  92.973  5137.3   92.41  5173.4      91  5233.4   92.57
  5523.4   94.33  5593.4   92.33  5623.4   93.11  5690.6   92.49 5702.39   92.13
#Mann= 8 ,-1 , 0
  2637.3     .12       0  2707.3     .08       0  3107.3     .05       0
    3540     .08       0    4950     .04       0    5040     .99       0
  5593.4    .015       0  5690.6     .05       0
#XS Ineff= 2 ,-1
  2637.3    4215    95.9 5022.59  5690.6      96
Permanent Ineff=
       F       F
Bank Sta=4976.12,5022.59
XS Rating Curve= 0
Exp/Cntr=.5,.3

Type RM Length L Ch R = 1 ,28586.7 ,40,41.1,42
BEGIN DESCRIPTION:
PALO PINTO - XS 3
Levees are not FEMA regulated levees, only RAS levees to prevent spilling into E115-09-00.
END DESCRIPTION:
XS GIS Cut Line= 4
      3066783.05      13869389.4      3066871.26     13866872.72
      3066564.35     13866452.09      3066559.56     13866395.44
#Sta/Elev= 30
  2636.4   94.36  2666.4    94.4  2706.4   91.71  2776.4      91  3136.4   92.46
  3156.4   91.86  3206.4   92.61  3256.4   91.37  3386.4   91.76  3426.4   93.56
  3586.4   93.01  3676.4   92.14  4476.4   91.89  4556.4   92.64  4876.4   92.58
  4920.2   93.63  4976.4   93.48  4992.7   84.52  5000.5    81.7  5008.8   83.91
  5016.7   89.99  5022.2   92.37    5029   93.46  5204.2   90.91  5244.2   92.71
  5354.2   93.81  5564.7   92.46  5624.7   91.81  5675.4   93.16 5731.72    91.6
#Mann= 6 ,-1 , 0
  2636.4     .08       0  3156.4     .08       0  3586.4     .08       0
  4976.4     .04       0    5029     .99       0  5564.7    .015       0
#XS Ineff= 4 ,-1
  2636.4    4280    95.9    4952    4962      91    5028    5075   90.79
    5075  5735.4      96
Permanent Ineff=
       F       F       F       F
Bank Sta=4976.4,5022.2
XS Rating Curve= 0
Exp/Cntr=.5,.3

Type RM Length L Ch R = 3 ,28566.0 ,,,
BEGIN DESCRIPTION:
PALO PINTO DRIVE
Structure ID: E115-00-00-21
END DESCRIPTION:
Bridge Culvert--1,0,-1,-1, 0
Deck Dist Width WeirC Skew NumUp NumDn MinLoCord MaxHiCord MaxSubmerge Is_Ogee
10,24,2.6,0, 60, 60, , , .95, 0, ,,,
  2405.9  2555.9  2636.3  2666.3  2706.3  2776.3  3445.9  3646.3  4546.3  4830.8
  4976.4  4982.1 4982.39  4982.5  4982.6    4999  5017.7 5017.81 5017.89    5018
  5018.2  5022.2  5204.2  5244.2  5354.2  5624.7  5675.4  5735.4  5835.4  5955.4
  6035.4  6085.4  6115.4  6175.4  6255.4  6455.4  6535.4  6765.4  7005.4  7185.4
  7285.4  7385.4  7425.4  7485.4  7665.4  8075.4  8205.4  8275.4  8315.4  8335.4
  8355.4  8365.4  8375.4  8395.4  8415.4  8485.4  8975.4  9285.4  9335.4  9387.3
    91.6   93.01    94.9    94.5    91.7      91   93.71   92.82   93.21   92.31
   93.77   93.83   93.83   93.83   95.93   95.93   95.92   93.82   93.82   93.82
   93.82   93.68   90.87   92.67   93.77   91.77   93.12   91.37   92.18   90.75
   96.22    96.6   96.29   92.81   90.66   93.06   93.16   89.06   91.76   91.36
   93.46   92.22   90.79   91.38   90.64   91.03   93.27    92.8   90.37   87.06
   80.52   78.89    79.4   87.19   91.65   93.14    92.4   89.41    91.6   92.11
                                                                                
           90.49   90.34   92.23   92.23   92.23   92.22   92.22   92.22   90.54
   90.63
                                                                                
                                                                                
                                                                                
  2405.9  2555.9  2636.3  2666.3  2706.3  2776.3  3445.9  3646.3  4546.3  4830.8
  4976.4  4982.1 4982.39  4982.5  4982.6    4999  5017.7 5017.81 5017.89    5018
  5018.2  5022.2  5204.2  5244.2  5354.2  5624.7  5675.4  5735.4  5835.4  5955.4
  6035.4  6085.4  6115.4  6175.4  6255.4  6455.4  6535.4  6765.4  7005.4  7185.4
  7285.4  7385.4  7425.4  7485.4  7665.4  8075.4  8205.4  8275.4  8315.4  8335.4
  8355.4  8365.4  8375.4  8395.4  8415.4  8485.4  8975.4  9285.4  9335.4  9387.3
    91.6   93.01    94.9    94.5    91.7      91   93.71   92.82   93.21   92.31
   93.77   93.83   93.83   93.83   95.93   95.93   95.92   93.82   93.82   93.82
   93.82   93.68   90.87   92.67   93.77   91.77   93.12   91.37   92.18   90.75
   96.22    96.6   96.29   92.81   90.66   93.06   93.16   89.06   91.76   91.36
   93.46   92.22   90.79   91.38   90.64   91.03   93.27    92.8   90.37   87.06
   80.52   78.89    79.4   87.19   91.65   93.14    92.4   89.41    91.6   92.11
                                                                                
           90.49   90.34   92.23   92.23   92.23   92.22   92.22   92.22   90.54
   90.63
                                                                                
                                                                                
                                                                                
Pier Skew, UpSta & Num, DnSta & Num=  ,4994.4, 2 ,4994.4, 2 , 0 , 0 , 0 ,,
     1.5     1.5
   82.86   93.23
     1.5     1.5
   82.84   93.21
Pier Skew, UpSta & Num, DnSta & Num=  ,5006.3, 2 ,5006.3, 2 , 0 , 0 , 0 ,,
     1.5     1.5
   82.51   93.22
     1.5     1.5
   82.49    93.2
BR Coef= 1 , 1 , 1 ,1.05, 0 ,,,.8,-1,1.2,0,
WSPro=,,,, 1 ,,,, 0 ,,,, 0 ,,,,-1 ,-1 ,-1 , 0 , 0 , 0 , 0 , 0
BC Design=,, 0 ,, 0 ,,,,,,
BC HTab HWMax=97.61

Type RM Length L Ch R = 1 ,28545.6 ,98.2,98.1,98
BEGIN DESCRIPTION:
PALO PINTO - XS 2
Levees are not FEMA regulated levees, only RAS levees to prevent spilling into E115-09-00.
END DESCRIPTION:
XS GIS Cut Line= 4
      3066824.06      13869391.1      3066912.88     13866857.21
      3066604.06     13866433.96       3066600.5     13866392.03
#Sta/Elev= 30
  2636.4   94.32  2666.4   94.36  2706.4   91.67  2776.4   90.96  3136.4   92.42
  3156.4   91.82  3206.4   92.57  3256.4   91.33  3386.4   91.72  3426.4   93.52
  3586.4   92.97  3676.4    92.1  4476.4   91.85  4876.4   92.54  4920.2   93.59
  4976.4   93.44  4992.7   84.48  5000.5   81.66  5008.8   83.87  5016.7   89.95
  5022.2   92.33    5029   93.42  5204.2   90.87  5244.2   92.67  5354.2   93.77
  5564.7   92.42  5624.7   91.77  5664.7   93.16  5725.4   91.89 5737.91   91.35
#Mann= 7 ,-1 , 0
  2636.4     .08       0  3156.4     .08       0  3586.4     .08       0
  4976.4     .04       0    5029     .99       0  5564.7    .015       0
  5725.4     .05       0
#XS Ineff= 4 ,-1
  2636.4    4280    95.4    4952    4972   90.96    5028    5075   90.79
    5075  5725.4      96
Permanent Ineff=
       F       F       F       F
Bank Sta=4976.4,5022.2
XS Rating Curve= 0
Exp/Cntr=.5,.3

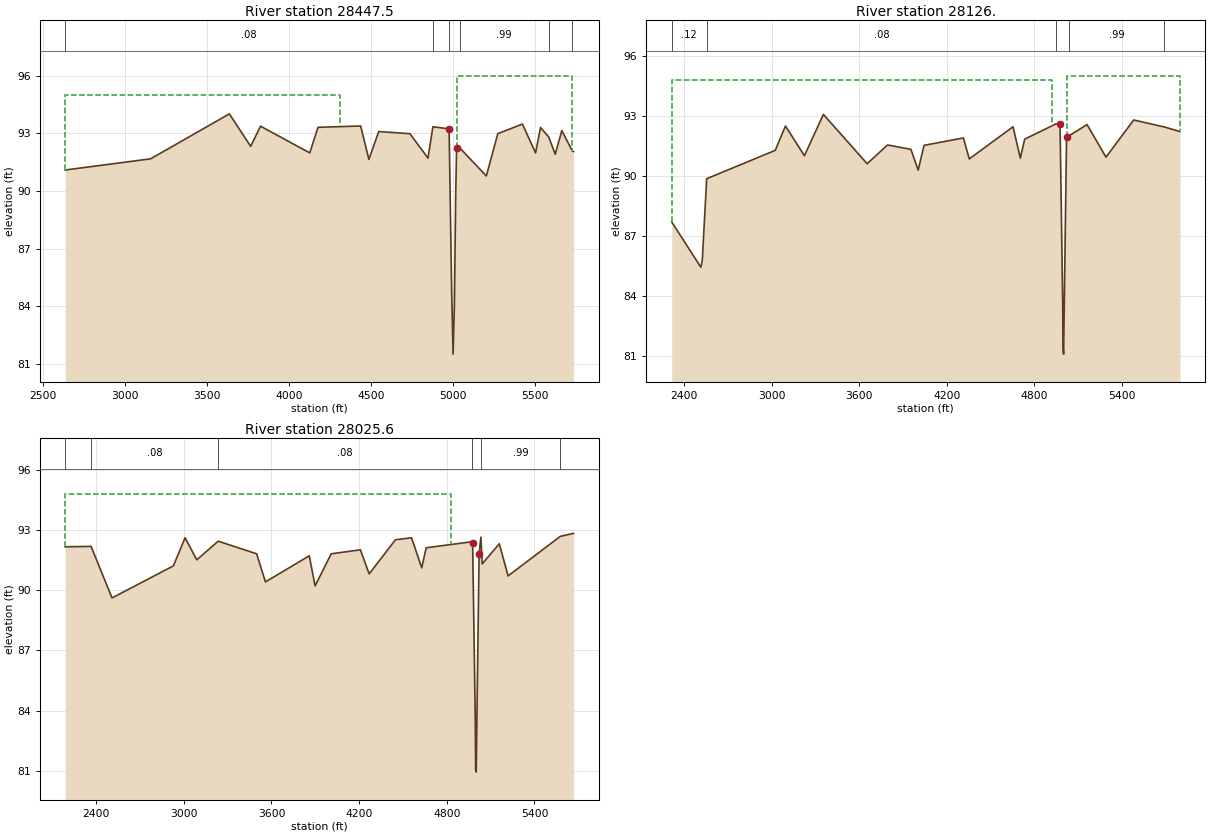
Type RM Length L Ch R = 1 ,28447.5 ,401.2,321.5,245.9
BEGIN DESCRIPTION:
PALO PINTO - XS 1
Interplotated channel, LIDAR overbanks
Levees are not FEMA regulated levees, only RAS levees to prevent spilling into E115-09-00.
Cross-Section would need to be extended across E117-00-00 channel in order to contain all flood events.
END DESCRIPTION:
XS GIS Cut Line= 4
      3066922.16     13869393.75      3067010.97     13866859.81
      3066702.15     13866436.56      3066699.17     13866399.64
#Sta/Elev= 30
  2637.7    91.1  3157.7   91.68  3637.7   94.02  3767.7   92.33  3827.7   93.38
  4127.7   91.99  4177.7   93.32  4437.7   93.39  4487.7   91.65  4547.7    93.1
  4737.7   92.99  4847.7   91.72  4877.7   93.35 4976.46   93.24  4991.8   84.88
 5000.65   81.52 5008.81    84.1 5016.58   89.74 5021.99   92.23    5040  92.262
  5203.2   90.79  5273.2   92.99  5423.2   93.49  5503.2   91.99  5533.2   93.31
  5583.2   92.82  5623.2   91.92  5663.2   93.15  5727.1   92.09 5734.45   92.06
#Mann= 6 ,-1 , 0
  2637.7     .08       0  4877.7     .05       0 4976.46     .04       0
    5040     .99       0  5583.2    .015       0  5727.1     .05       0
#XS Ineff= 2 ,-1
  2637.7    4310      95 5021.99  5727.1      96
Permanent Ineff=
       F       F
Bank Sta=4976.46,5021.99
XS Rating Curve= 0
Exp/Cntr=.3,.1

Type RM Length L Ch R = 1 ,28126.  ,110.7,100.4,100
BEGIN DESCRIPTION:
SPRING BROOK DR - XS 4
Interplotated channel, LIDAR overbanks
Levees are not FEMA regulated levees, only RAS levees to prevent spilling into E115-09-00.
Cross-Section would need to be extended across E117-00-00 channel in order to contain all flood events
END DESCRIPTION:
XS GIS Cut Line= 4
      3067489.74     13869600.85      3067366.32     13866997.54
      3067129.92     13866950.48      3066802.18     13866403.14
#Sta/Elev= 30
  2314.4   87.69  2514.4   85.42  2524.4   85.78  2554.4   89.85  3024.4   91.27
  3094.4   92.49  3224.4      91  3354.4   93.07  3654.4    90.6  3794.4   91.54
  3954.4   91.32  4004.4   90.28  4044.4   91.52  4314.4   91.89  4354.4   90.84
  4654.4   92.45  4704.4   90.88  4734.4   91.83    4950  92.599 4976.64   92.58
 4995.17   83.54 4997.06   81.42 5001.15   81.07 5021.31   91.92    5040  92.005
  5161.7   92.56  5291.7   90.93  5481.7   92.79  5691.7   92.44 5799.01   92.21
#Mann= 5 ,-1 , 0
  2314.4     .12       0  2554.4     .08       0    4950     .04       0
    5040     .99       0  5691.7    .015       0
#XS Ineff= 2 ,-1
  2314.4  4920.6    94.8 5021.31  5801.7      95
Permanent Ineff=
       F       F
Bank Sta=4976.64,5021.31
XS Rating Curve= 0
Exp/Cntr=.5,.3

Type RM Length L Ch R = 1 ,28025.6 ,44.2,44,43.2
BEGIN DESCRIPTION:
SPRING BROOK DR - XS 3
Levees are not FEMA regulated levees, only RAS levees to prevent spilling into E115-09-00.
Cross-Section would need to be extended across E117-00-00 channel in order to contain all flood events
END DESCRIPTION:
XS GIS Cut Line= 4
      3067536.37       13869594.      3067397.11     13866883.85
      3067140.56     13866867.68      3066903.36     13866417.86
#Sta/Elev= 30
  2188.1   92.16  2365.2   92.18  2508.6   89.61  2928.6   91.21  3008.6   92.61
  3088.6   91.51  3235.3   92.44  3498.6   91.81  3558.6   90.41  3858.6   91.71
  3898.6   90.21  4008.6   91.81  4208.6   92.01  4268.6   90.81  4448.6   92.51
  4558.6   92.61  4628.6   91.11  4658.6   92.11  4970.1   92.41  4976.7   92.37
  4995.3   83.39  4997.2   81.04  5001.3   80.93  5021.1   91.82  5033.3   92.64
  5042.4   91.31  5159.4   92.31  5219.4   90.71  5577.1   92.68 5667.43   92.83
#Mann= 6 ,-1 , 0
  2188.1     .12       0  2365.2     .08       0  3235.3     .08       0
  4970.1     .08       0  5033.3     .99       0  5577.1    .015       0
#XS Ineff= 2 ,-1
  2188.1  4828.6    94.8  4828.6    4972    91.5
Permanent Ineff=
       F       F
Bank Sta=4976.7,5021.1
XS Rating Curve= 0
Exp/Cntr=.5,.3