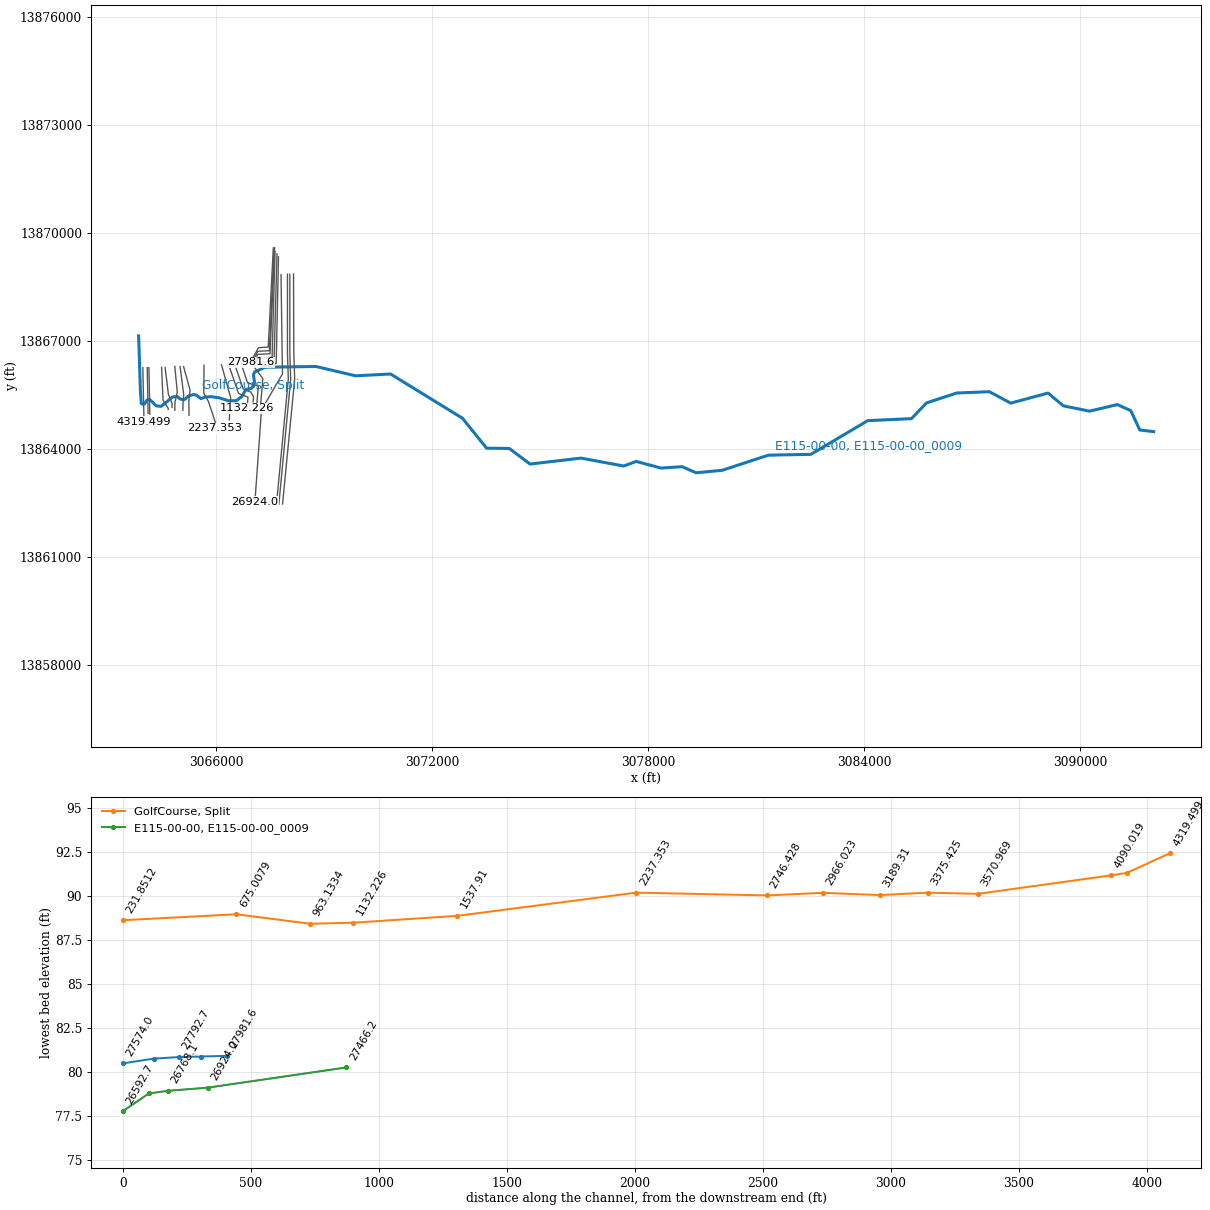
HEC-RAS study E115-00-00.prj: E115-00-00

--- E115-00-00.g01 (geometry) --- (continued)

Type RM Length L Ch R = 3 ,28003.6 ,,,
BEGIN DESCRIPTION:
SPRING BROOK DRIVE
Structure ID: E115-00-00-20
END DESCRIPTION:
Bridge Culvert--1,0,-1,-1, 0
Deck Dist Width WeirC Skew NumUp NumDn MinLoCord MaxHiCord MaxSubmerge Is_Ogee
10,24,2.6,0, 60, 60, , , .95, 0, ,,,
  2099.7  2288.6  2388.6  2449.7  2509.7  2779.7  3008.6  3088.6  3139.7  3179.7
  3248.6  3338.6  3759.7  4399.7  4609.7  4954.4  4970.1  4976.7 4982.49  4982.6
  4982.7  5017.9 5018.01  5018.2  5021.1  5033.3  5042.4  5052.4  5307.1  5547.1
  5609.4  5649.4  5719.4  5757.1  5815.8  5855.8  5885.8  5919.4  5945.8  6005.8
  6065.8  6175.8  6305.8    6399    6429  6525.8    6569  6635.8  6695.8  6735.8
  6845.8    6929    7069    7109    7259    7349  7445.8  7525.8  7875.8    7989
    91.4   92.41   92.11   90.56    91.5   91.19   92.61   91.89    92.6   91.68
   92.71    91.8   91.22    92.5    91.7    92.5   92.54   92.65   92.75   92.75
   94.85   94.88   92.78   92.78   92.75   92.64   91.69   91.91   91.51      93
   92.21   93.21   92.48    93.2    96.1    95.4   92.94   92.51    94.5    94.6
   92.56    91.6   88.48   93.61   93.61    90.5   91.41      89    89.3    90.6
      89   91.71   92.01   93.11   92.41   90.61    91.4    93.4    94.5   92.34
                                                                                
                                                    92.4   92.36   89.44   91.15
   91.15   91.18   91.18   90.07   91.81   92.63    91.3
                                                                                
                                                                                
                                                                                
  2099.7  2288.6  2388.6  2449.7  2509.7  2779.7  3008.6  3088.6  3139.7  3179.7
  3248.6  3338.6  3759.7  4399.7  4609.7  4954.4  4970.1  4976.7 4982.49  4982.6
  4982.7  5017.9 5018.01  5018.2  5021.1  5033.3  5042.4  5052.4  5307.1  5547.1
  5609.4  5649.4  5719.4  5757.1  5815.8  5855.8  5885.8  5919.4  5945.8  6005.8
  6065.8  6175.8  6305.8    6399    6429  6525.8    6569  6635.8  6695.8  6735.8
  6845.8    6929    7069    7109    7259    7349  7445.8  7525.8  7875.8    7989
    91.4   92.41   92.11   90.56    91.5   91.19   92.61   91.89    92.6   91.68
   92.71    91.8   91.22    92.5    91.7    92.5   92.54   92.65   92.75   92.75
   94.85   94.88   92.78   92.78   92.75   92.64   91.69   91.91   91.51      93
   92.21   93.21   92.48    93.2    96.1    95.4   92.94   92.51    94.5    94.6
   92.56    91.6   88.48   93.61   93.61    90.5   91.41      89    89.3    90.6
      89   91.71   92.01   93.11   92.41   90.61    91.4    93.4    94.5   92.34
                                                                                
                                                    92.4   92.36   89.44   91.15
   91.15   91.18   91.18   90.07   91.81   92.63    91.3
                                                                                
                                                                                
                                                                                
Pier Skew, UpSta & Num, DnSta & Num=  ,4994.5, 2 ,4994.5, 2 , 0 , 0 , 0 ,,
     1.5     1.5
   82.41   92.16
     1.5     1.5
   82.48   92.23
Pier Skew, UpSta & Num, DnSta & Num=  ,5006.4, 2 ,5006.4, 2 , 0 , 0 , 0 ,,
     1.5     1.5
   82.16   92.17
     1.5     1.5
   82.23   92.24
BR Coef= 1 , 1 , 1 ,1.05, 0 ,,,.8,-1,1.2,0,
WSPro=,,,, 1 ,,,, 0 ,,,, 0 ,,,,-1 ,-1 ,-1 , 0 , 0 , 0 , 0 , 0
BR D #Sta/Elev= 30
  2188.1   92.16  2365.2   92.18  2508.6   89.61  2928.6   91.21  3008.6   92.61
  3088.6   91.51  3235.3   92.44  3498.6   91.81  3558.6   90.41  3858.6   91.71
  3898.6   90.21  4008.6   91.81  4208.6   92.01  4268.6   90.81  4448.6   92.51
  4558.6   92.61  4628.6   91.11  4658.6   92.11  4970.1   92.41  4976.7   92.37
  4995.3   83.39  4997.2   81.04  5001.3   80.93  5021.1   91.82  5033.3   92.64
  5042.4   91.31  5159.4   92.31  5219.4   90.71  5599.4   92.51 5682.15   92.41
BR D #Mann= 8
  2188.1     .12  2365.2     .08  3235.3     .08  4970.1     .04  4976.7     .04
  5021.1     .04  5033.3     .08  5599.4    .045
BC Design=,, 0 ,, 0 ,,,,,,
BC HTab HWMax=93.71

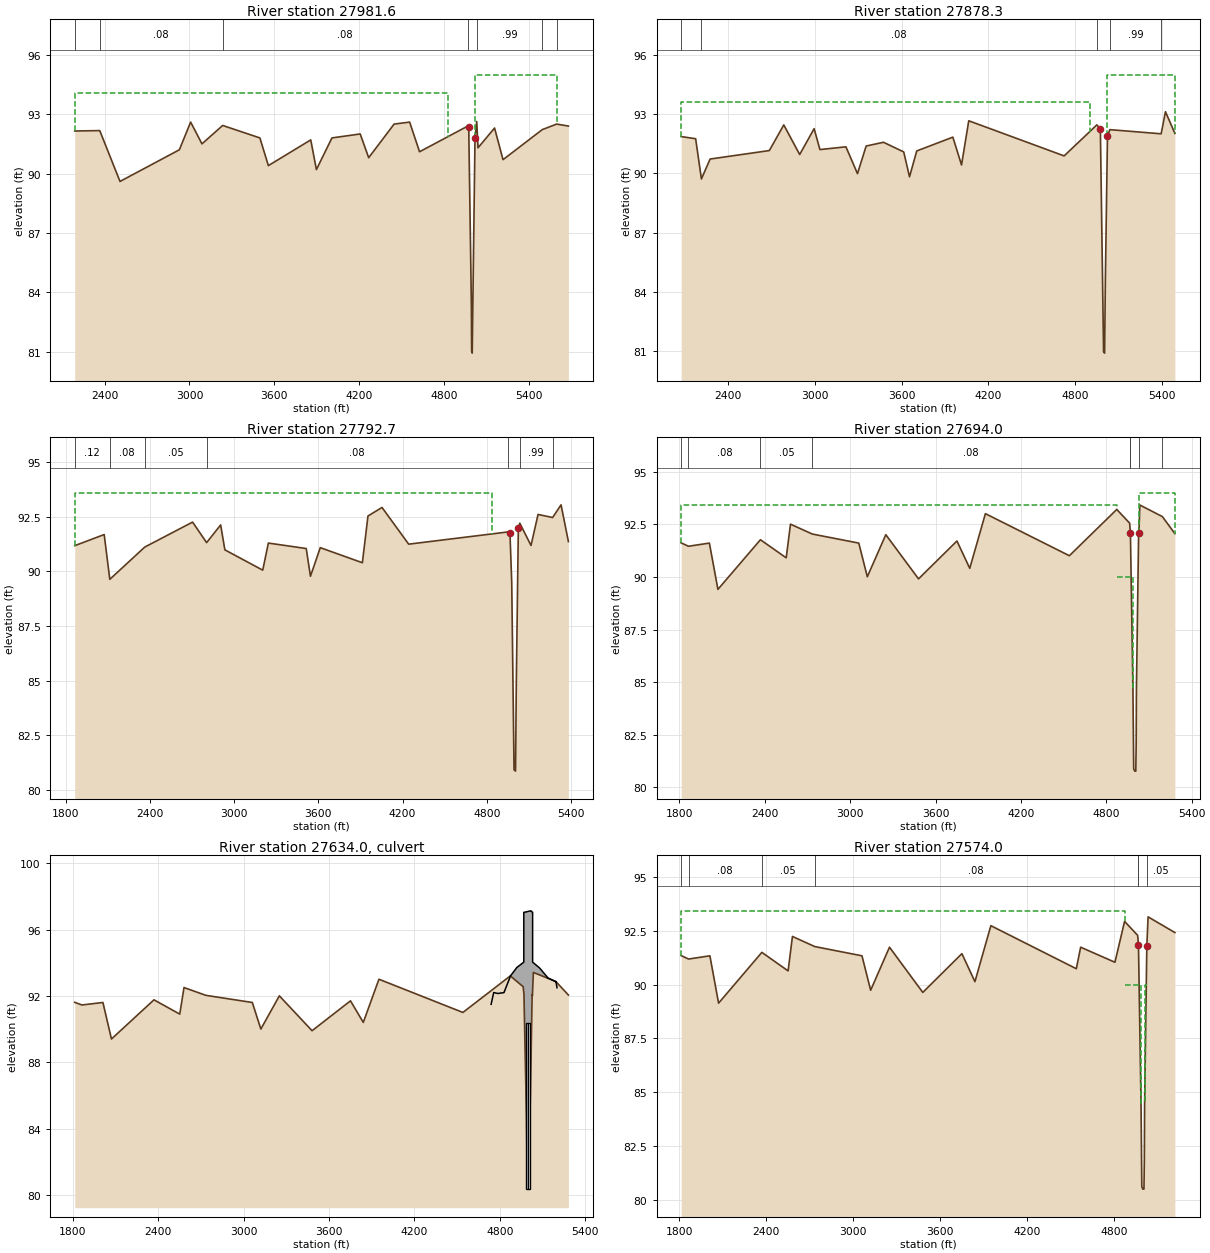
Type RM Length L Ch R = 1 ,27981.6 ,99.9,103.3,98.8
BEGIN DESCRIPTION:
SPRING BROOK DR - XS 2
Levees are not FEMA regulated levees, only RAS levees to prevent spilling into E115-09-00.
Cross-Section would need to be extended across E117-00-00 channel in order to contain all flood events.
END DESCRIPTION:
XS GIS Cut Line= 4
      3067586.31      13869598.3      3067444.75     13866843.59
       3067171.7     13866826.37      3066955.68     13866416.67
#Sta/Elev= 30
  2188.1   92.16  2365.2   92.18  2508.6   89.61  2928.6   91.21  3008.6   92.61
  3088.6   91.51  3235.3   92.44  3498.6   91.81  3558.6   90.41  3858.6   91.71
  3898.6   90.21  4008.6   91.81  4208.6   92.01  4268.6   90.81  4448.6   92.51
  4558.6   92.61  4628.6   91.11  4970.1   92.41  4976.7   92.37  4995.3   83.39
  4997.2   81.04  5001.3   80.93  5021.1   91.82  5033.3   92.64  5042.4   91.31
  5159.4   92.31  5219.4   90.71  5497.1   92.23  5599.4   92.51 5682.15   92.41
#Mann= 7 ,-1 , 0
  2188.1     .12       0  2365.2     .08       0  3235.3     .08       0
  4970.1     .04       0  5033.3     .99       0  5497.1    .015       0
  5599.4     .05       0
#XS Ineff= 3 ,-1
  2188.1  4828.6    94.1  4828.6    4972      91  5021.1  5599.4      95
Permanent Ineff=
       F       F       F
Bank Sta=4976.7,5021.1
XS Rating Curve= 0
Exp/Cntr=.5,.3

Type RM Length L Ch R = 1 ,27878.3 ,85.7,85.6,85.5
BEGIN DESCRIPTION:
SPRING BROOK DR - XS 1
Interplotated channel, LIDAR overbanks
Levees are not FEMA regulated levees, only RAS levees to prevent spilling into E115-09-00.
Cross-Section would need to be extended across E117-00-00 channel in order to contain all flood events.
END DESCRIPTION:
XS GIS Cut Line= 4
      3067601.56     13869497.72      3067475.76     13866743.92
      3067151.54     13866727.32      3067018.43     13866419.79
#Sta/Elev= 30
  2073.5   91.87  2173.5   91.76  2213.5   89.72  2273.5   90.73  2683.5   91.16
  2783.5   92.46  2893.5   90.96  2993.5   92.27  3033.5   91.21  3213.5   91.35
  3293.5   89.99  3353.5   91.39  3473.5   91.58  3613.5   91.09  3653.5   89.83
  3703.5   91.14  3953.5   91.84  4013.5   90.43  4063.5   92.67  4723.5   90.89
    4950  92.462 4974.19   92.27 4996.42   80.96 5003.49   80.89 5008.84   84.58
 5023.36   91.91  5040.2   92.22  5394.8   92.01  5424.8   93.13 5489.86   92.03
#Mann= 5 ,-1 , 0
  2073.5     .12       0  2213.5     .08       0    4950     .04       0
  5040.2     .99       0  5394.8    .015       0
#XS Ineff= 2 ,-1
  2073.5  4900.2    93.6 5023.36  5504.8      95
Permanent Ineff=
       F       F
Bank Sta=4974.19,5023.36
XS Rating Curve= 0
Exp/Cntr=.3,.1

Type RM Length L Ch R = 1 ,27792.7 ,102.3,98.7,102.4
BEGIN DESCRIPTION:
CLAY RD - XS 4
Interplotated channel, LIDAR overbanks
Levees are not FEMA regulated levees, only RAS levees to prevent spilling into E115-09-00.
Cross-Section would need to be extended across E117-00-00 channel in order to contain all flood events.
END DESCRIPTION:
XS GIS Cut Line= 4
       3067621.5     13869608.27      3067494.72     13866658.95
      3067141.22      13866641.3      3067101.53       13866432.
#Sta/Elev= 30
  1863.7   91.18  2073.7   91.69  2113.7   89.64    2363  91.117  2703.7   92.26
  2803.7   91.32  2903.7   92.13  2933.7   90.99  3203.7   90.06  3243.7    91.3
  3513.7   91.05  3543.7   89.78  3613.7   91.09  3913.7    90.4  3953.7   92.54
  4053.7   92.93  4243.7   91.25    4950  91.808  4965.7   91.74 4978.17   89.49
 4994.72   80.92 5005.31   80.86 5010.71   84.84 5025.24   91.99  5035.7   92.21
  5115.7   91.19  5165.7   92.61  5269.7   92.47  5329.7   93.05 5382.13   91.37
#Mann= 7 ,-1 , 0
  1863.7     .12       0  2113.7     .08       0    2363     .05       0
  2803.7     .08       0    4950     .04       0  5035.7     .99       0
  5269.7    .015       0
#XS Ineff= 1 ,-1
  1863.7  4835.7    93.6
Permanent Ineff=
       F
Bank Sta=4965.7,5025.24
XS Rating Curve= 0
Exp/Cntr=.5,.3

Type RM Length L Ch R = 1 ,27694.0 ,121,120,121.1
BEGIN DESCRIPTION:
CLAY RD - XS 3
Levees are not FEMA regulated levees, only RAS levees to prevent spilling into E115-09-00.
END DESCRIPTION:
XS GIS Cut Line= 4
      3067634.13       13869505.       3067552.2     13866559.46
      3067142.96     13866538.87        3067125.      13866427.1
#Sta/Elev= 30
  1812.3   91.62  1863.1   91.46  2010.5   91.61  2070.5   89.41  2369.3   91.77
  2550.5   90.91  2580.5   92.51  2734.2   92.04  3060.5   91.61  3120.5   90.01
  3250.5   92.01  3480.5   89.91  3750.5   91.71  3840.5   90.41  3950.5   93.01
  4540.5   91.01  4873.8   93.21  4964.1   92.56  4969.7    92.1  4987.4   84.67
  4992.7   80.88  5000.1   80.77  5007.5   80.77  5010.3   82.12    5012   84.68
  5027.4   92.08  5029.2   92.02  5036.1   93.42  5194.3   92.87  5282.2   92.06
#Mann= 8 ,-1 , 0
  1812.3     .12       0  1863.1     .08       0  2369.3     .05       0
  2734.2     .08       0  4964.1     .04       0  4969.7    .015       0
  5029.2     .99       0  5194.3    .015       0
#XS Ineff= 3 ,-1
  1812.3  4873.8   93.43  4873.8  4987.4      90  5027.4    5287      94
Permanent Ineff=
       F       F       F
Bank Sta=4969.7,5027.4
XS Rating Curve= 0
Exp/Cntr=.5,.3

Type RM Length L Ch R = 2 ,27634.0 ,,,
BEGIN DESCRIPTION:
CLAY ROAD (LIVELY)
Structure ID: E115-00-00-19
END DESCRIPTION:
Bridge Culvert--1,0,-1,-1, 0
Deck Dist Width WeirC Skew NumUp NumDn MinLoCord MaxHiCord MaxSubmerge Is_Ogee
10,100,3,0, 45, 45, , , .95, 0, ,,,
    4739  4757.2  4787.2  4807.2  4817.2  4827.2    4829    4869  4873.8  4873.9
  4896.2  4919.8  4930.7  4959.5  4964.1 4968.49  4968.6 4968.71  4969.7  4969.8
  4987.4  4990.5  4992.7  4993.3  5000.1  5007.4  5007.5  5010.3    5012  5015.3
  5018.9  5027.4  5029.2 5030.49  5030.6 5030.71  5036.1  5078.1  5095.2  5109.6
  5139.5  5142.7  5194.3  5194.4  5202.2
    91.5   92.21   92.15   92.18   92.19    92.2    92.2   93.07    93.2    93.2
   93.45   93.72   93.79   93.98   94.01   94.04   97.04   97.04   97.04   97.04
   97.07   97.08   97.08   97.08    97.1   97.11   97.11   97.11   97.12   97.12
   97.13   97.06   97.05   97.04   97.04   94.04      94    93.7   93.53   93.38
   93.08   93.07   92.86   92.87    92.5
                                                                                
                                                                                
                                                                                
                                                                                
                                        
    4739  4757.2  4787.2  4807.2  4817.2  4827.2    4829    4869  4873.8  4873.9
  4896.2  4919.8  4930.7  4959.5  4964.1 4968.49  4968.6 4968.71  4969.7  4969.8
  4987.4  4990.5  4992.7  4993.3  5000.1  5007.4  5007.5  5010.3    5012  5015.3
  5018.9  5027.4  5029.2 5030.49  5030.6 5030.71  5036.1  5078.1  5095.2  5109.6
  5139.5  5142.7  5194.3  5194.4  5202.2
    91.5   92.21   92.15   92.18   92.19    92.2    92.2   93.07    93.2    93.2
   93.45   93.72   93.79   93.98   94.01   94.04   97.04   97.04   97.04   97.04
   97.07   97.08   97.08   97.08    97.1   97.11   97.11   97.11   97.12   97.12
   97.13   97.06   97.05   97.04   97.04   94.04      94    93.7   93.53   93.38
   93.08   93.07   92.86   92.87    92.5
                                                                                
                                                                                
                                                                                
                                                                                
                                        
BR Coef= 1 , 0 , 0 ,1.25, 0 ,,,.8,-1,2,0,
WSPro=,,,, 1 ,,,, 0 ,,,, 0 ,,,,-1 ,-1 ,-1 , 0 , 0 , 0 , 0 , 0
Culvert=2,10,12,100,.02,.4,1,8,1,80.37,4993.4,80.47,4993.4,Culvert #1  , 0 ,10
Culvert Bottom n=.02
Culvert=2,10,12,100,.02,.4,1,8,1,80.39,5006.4,80.44,5006.4,Culvert #2  , 0 ,10
Culvert Bottom n=.02
BC Design=,, 0 ,, 0 ,,,,,,
BC HTab HWMax=96.61

Type RM Length L Ch R = 1 ,27574.0 ,0,0,0
BEGIN DESCRIPTION:
CLAY RD - XS 2
Levees are not FEMA regulated levees, only RAS levees to prevent spilling into E115-09-00.
END DESCRIPTION:
XS GIS Cut Line= 3
      3067688.78      13869432.7      3067605.56     13866440.95
      3067190.56     13866420.07
#Sta/Elev= 30
  1812.3   91.35  1863.1   91.19  2010.5   91.34  2070.5   89.14  2369.3    91.5
  2550.5   90.64  2580.5   92.24  2734.2   91.77  3060.5   91.34  3120.5   89.74
  3250.5   91.74  3480.5   89.64  3750.5   91.44  3840.5   90.14  3950.5   92.74
  4540.5   90.74  4570.5   91.74  4807.2   91.04  4873.8   92.94  4964.1   92.29
  4969.7   91.83  4987.4    84.4  4992.7   80.61  5000.1    80.5  5007.5    80.5
  5010.3   81.85    5012   84.41  5027.4   91.81  5036.1   93.15 5221.03   92.42
#Mann= 7 ,-1 , 0
  1812.3     .12       0  1863.1     .08       0  2369.3     .05       0
  2734.2     .08       0  4964.1     .04       0  4969.7    .015       0
  5027.4     .05       0
#XS Ineff= 3 ,-1
  1812.3  4873.8   93.43  4873.8  4987.4      90  5012.4 5030.71      90
Permanent Ineff=
       F       F       F
Bank Sta=4969.7,5027.4
XS Rating Curve= 0
Exp/Cntr=.5,.3

River Reach=GolfCourse      ,Split
Reach XY= 30
 3063844.710307913867156.2320472 3063892.442605613865661.9476516
 3063918.337790813865276.4868846 3063969.537532913865256.8186143
 3064012.808715513865268.6195765 3064075.7471805 13865370.894582
 3064146.552953613865394.4965064 3064335.164489213865211.1168603
 3064472.673400613865197.7162966  3064788.80826713865457.4254228
  3064908.90645213865471.9998687 3065013.6729747 13865396.347461
 3065113.092395313865382.2113344 3065229.031139813865486.9171617
 3065366.573843713865524.7786346 3065448.728863113865509.0536004
 3065576.745995613865412.6364704 3065711.767707113865458.1344109
  3065863.680133 13865466.300077 3066096.007752313865431.2755407
 3066328.767785513865353.9777951 3066557.984846713865354.5309436
 3066711.303109613865468.2472516 3066808.539135613865640.1967108
 3066982.995807713865704.4515036 3067036.767681813865752.2742426
 3067063.676420613865872.4872567 3067034.811977113866072.3244555
 3067065.781075213866149.7334214 3067352.1176145 13866285.040838

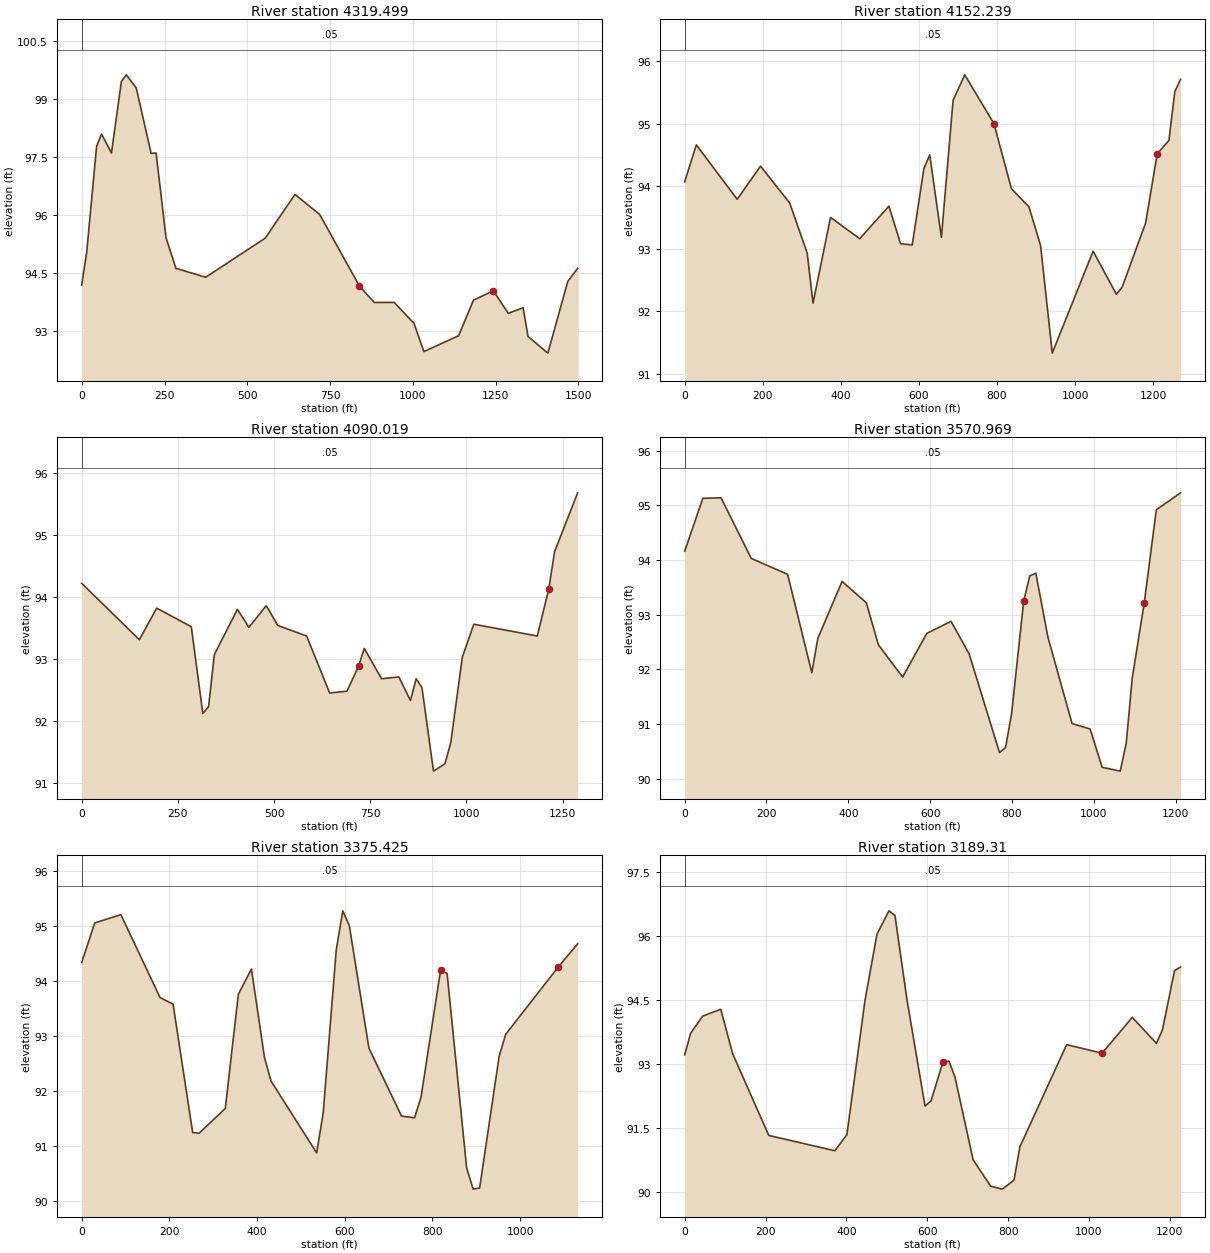
Type RM Length L Ch R = 1 ,4319.499,173.31,167.26,119.49
XS GIS Cut Line= 2
 3063962.109789113866272.9421645 3063993.6925284 13864775.828273
#Sta/Elev= 30
       0    94.2   14.97   95.04   44.92   97.78    59.9    98.1   89.85   97.61
   119.8   99.46  134.77   99.63  164.72   99.29  209.64    97.6  224.62   97.61
  254.57   95.42  284.52   94.63  374.36    94.4  554.06   95.41  643.91   96.54
  718.78   96.02  838.57   94.17   883.5   93.75   943.4   93.75 1003.29   93.21
 1033.24   92.48 1138.07   92.89 1182.99   93.81 1242.89   94.05 1287.81   93.47
 1332.73   93.61 1347.71   92.87 1407.61   92.44 1467.51   94.29 1497.45   94.63
#Mann= 1 ,-1 , 0
       0     .05       0
Bank Sta=838.57,1242.89
XS Rating Curve= 0
Exp/Cntr=.3,.1

Type RM Length L Ch R = 1 ,4152.239,53.57,62.22,48.01
XS GIS Cut Line= 2
  3064083.59707913866273.6101421 3064107.340876413865003.6417563
#Sta/Elev= 30
       0   94.07   29.89   94.66  134.49   93.79  194.26   94.32  268.98   93.73
  313.81   92.93  328.75   92.13  373.58    93.5   448.3   93.16  523.02   93.68
   552.9   93.08  582.79   93.06  612.68   94.28  627.62    94.5  657.51   93.18
   687.4   95.37  717.28   95.78     792      95  836.83   93.96  881.66   93.67
  911.55   93.05  941.43   91.33 1046.04   92.96 1105.81   92.27 1120.75   92.39
 1180.53   93.41 1210.41   94.52  1240.3   94.73 1255.24   95.51 1270.19   95.71
#Mann= 1 ,-1 , 0
       0     .05       0
Bank Sta=792,1210.41
XS Rating Curve= 0
Exp/Cntr=.3,.1

Type RM Length L Ch R = 1 ,4090.019,384.82,519.05,499.31
XS GIS Cut Line= 2
 3064131.121590213866271.4369181 3064155.164058313864982.3519543
#Sta/Elev= 30
       0   94.22  149.92   93.31   194.9   93.82  284.85   93.52  314.83   92.12
  329.83   92.23  344.82   93.07  404.79    93.8  434.77   93.51  479.75   93.86
  509.73   93.54  584.69   93.37  644.66   92.45  689.64   92.48  719.62   92.88
  734.61   93.17  779.59   92.68  824.57   92.71  854.55   92.33  869.54   92.68
  884.53   92.54  914.52   91.19   944.5   91.31  959.49   91.65  989.48   93.03
 1019.46   93.56 1184.38   93.37 1214.36   94.13 1229.35   94.73 1289.32   95.68
#Mann= 1 ,-1 , 0
       0     .05       0
Bank Sta=719.62,1214.36
XS Rating Curve= 0
Exp/Cntr=.3,.1

Type RM Length L Ch R = 1 ,3570.969,136.95,195.54,105.1
XS GIS Cut Line= 4
 3064481.964720613866284.8640566 3064523.043378613865368.1139216
  3064666.50536213865145.5005217 3064665.477831413865115.5554362
#Sta/Elev= 30
       0   94.16    44.4   95.13   88.81   95.14  162.81   94.03  251.62   93.74
  310.82   91.94  325.63   92.57  384.83   93.61  444.03   93.22  473.64   92.45
  532.84   91.86  592.05   92.66  651.25   92.88  695.65   92.28  769.66   90.48
  784.46   90.57  799.26   91.19  828.86   93.25  843.66   93.71  858.47   93.76
  888.07   92.59   947.1   91.01  991.24   90.91 1020.66   90.21  1064.8   90.14
 1079.51   90.65 1094.23   91.84 1123.65   93.22 1153.08   94.92 1212.48   95.23
#Mann= 1 ,-1 , 0
       0     .05       0
Bank Sta=828.86,1123.65
XS Rating Curve= 0
Exp/Cntr=.3,.1

Type RM Length L Ch R = 1 ,3375.425,264.26,186.11,87.01
XS GIS Cut Line= 4
 3064580.153828613866275.1875668 3064671.452202513865536.3104356
 3064775.338477613865274.1216556 3064771.708862113865169.3293664
#Sta/Elev= 30
       0   94.34   29.78   95.06   89.34   95.21  178.68    93.7  208.46   93.58
  253.13   91.24  268.02   91.23  327.58   91.68  357.36   93.76  387.14   94.22
  416.92   92.61  431.81   92.18  536.04   90.87  550.93    91.6  580.71   94.57
   595.6   95.28  610.49   95.01  655.16   92.78  729.61   91.54  759.34   91.51
  774.18   91.89  818.71    94.2  833.56   94.14  878.08    90.6  892.93   90.21
  907.77   90.23   952.3   92.63  967.14   93.03 1086.44   94.25 1131.38   94.68
#Mann= 1 ,-1 , 0
       0     .05       0
Bank Sta=818.71,1086.44
XS Rating Curve= 0
Exp/Cntr=.3,.1

Type RM Length L Ch R = 1 ,3189.31 ,158.28,223.29,225.84
XS GIS Cut Line= 4
  3064849.32389413866305.6855373  3064918.800133 13865595.673834
 3064854.489894113865313.6973638  3064850.48611713865089.6152407
#Sta/Elev= 30
       0   93.22   14.86   93.73   44.59   94.13   89.18   94.29   118.9   93.24
  208.08   91.33  371.56   90.97  401.29   91.35  445.88   94.49   475.6   96.05
  505.33    96.6  520.19   96.49  549.91   94.51   594.5   92.02  609.36   92.14
  639.09   93.06  653.95   93.07  668.81   92.69   713.4   90.76  756.79   90.14
  785.71   90.07  814.63   90.28  829.09   91.06  944.78   93.46  1032.5   93.26
 1107.21    94.1 1166.97   93.49 1181.91   93.81  1211.8    95.2 1226.74   95.28
#Mann= 1 ,-1 , 0
       0     .05       0
Bank Sta=639.09,1032.5
XS Rating Curve= 0
Exp/Cntr=.3,.1

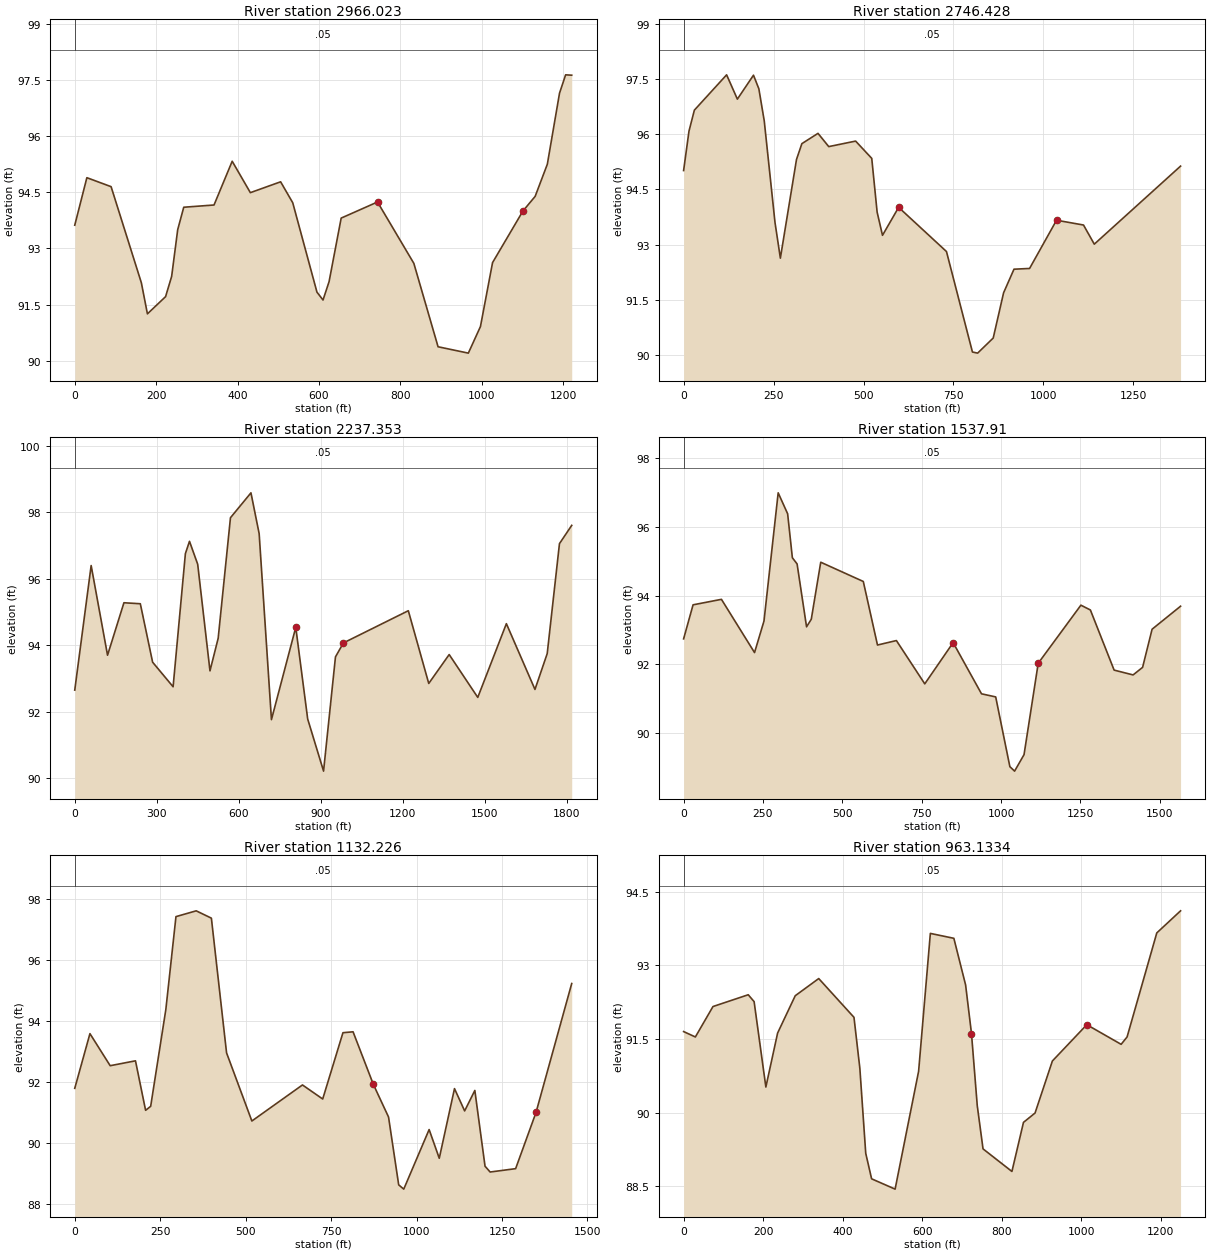
Type RM Length L Ch R = 1 ,2966.023,146.71,219.59,177.61
XS GIS Cut Line= 4
 3064996.367563113866303.7580477 3065096.890656113865521.4695861
  3065077.10296613865254.3336374  3065074.20963913865089.5812307
#Sta/Elev= 30
       0   93.62   29.76   94.89   89.29   94.65   163.7   92.08  178.58   91.25
  223.22   91.71   238.1   92.25  252.99    93.5  267.87    94.1  342.27   94.16
  386.92   95.33  431.56   94.49  505.97   94.78  535.73   94.22  595.26   91.83
  610.14   91.62  625.02   92.11  654.79   93.81  744.08   94.24  833.36    92.6
  892.89   90.37   967.3    90.2  997.06   90.91 1026.82   92.62 1101.53      94
 1131.49   94.39 1161.45   95.25 1191.41   97.15 1206.39   97.64 1221.37   97.63
#Mann= 1 ,-1 , 0
       0     .05       0
Bank Sta=744.08,1101.53
XS Rating Curve= 0
Exp/Cntr=.3,.1

Type RM Length L Ch R = 1 ,2746.428,469.74,509.08,673.91
XS GIS Cut Line= 4
 3065093.438235113866302.9601491 3065274.981507213865640.1967108
 3065240.352639513865368.1139216 3065244.367833713864948.5572204
#Sta/Elev= 30
       0   95.01   14.94   96.08   29.88   96.65  119.51   97.61  149.39   96.95
   194.2    97.6  209.14   97.23  224.08   96.36  253.96    93.6   268.9   92.63
  313.71   95.31  328.65   95.74  373.47   96.02  403.34   95.66  478.04   95.81
  522.85   95.34  537.79   93.88  552.73   93.25  597.55   94.01  730.48   92.81
  802.66   90.08   817.1   90.05  860.41   90.46  889.28   91.69  918.15   92.33
  961.46   92.35 1036.38   93.66 1111.31   93.53 1141.28   93.01 1381.04   95.13
#Mann= 1 ,-1 , 0
       0     .05       0
Bank Sta=597.55,1036.38
XS Rating Curve= 0
Exp/Cntr=.3,.1

Type RM Length L Ch R = 1 ,2237.353,583.09,699.44,460.27
XS GIS Cut Line= 5
 3065661.4669547 13866340.503053 3065655.897412113865561.0452943
 3065784.518217813865333.4850539 3065972.221910613864765.8273966
 3065959.281786213864587.0728944
#Sta/Elev= 30
       0   92.65   59.96    96.4  119.92    93.7  179.88   95.28  239.84   95.25
  284.81   93.49  359.76   92.75  404.73   96.76  419.72   97.13   449.7   96.44
  494.67   93.23  524.65   94.21  569.62   97.84  644.57   98.59  674.55   97.36
  719.52   91.76  808.52   94.54  852.09   91.78  910.17   90.21  953.74   93.65
  982.78   94.07 1220.24   95.04 1294.97   92.85 1369.71   93.72 1474.34   92.43
 1578.97   94.65 1683.57   92.67 1728.38   93.75 1773.18   97.06 1817.99   97.61
#Mann= 1 ,-1 , 0
       0     .05       0
Bank Sta=808.52,982.78
XS Rating Curve= 0
Exp/Cntr=.3,.1

Type RM Length L Ch R = 1 ,1537.91 ,210.56,405.68,483.24
XS GIS Cut Line= 4
 3066147.021429813866350.6175341 3066402.888372113865432.4241605
 3066388.047522513865239.4927878 3066363.388912513864821.6529616
#Sta/Elev= 30
       0   92.74   29.79   93.73  119.15   93.89   223.4   92.34  253.19   93.26
  297.87   96.99  327.65   96.38  342.55    95.1  357.44   94.92  387.23   93.09
  402.12   93.31  431.91   94.97  565.95   94.41  610.63   92.56   670.2   92.69
  759.56   91.43  848.92   92.63  938.28   91.14  982.95   91.05  1027.6   89.02
 1042.49   88.89 1072.26   89.37 1116.91   92.03 1251.32   93.72 1281.21   93.58
 1355.96   91.83 1415.75   91.69 1445.65   91.91 1475.54   93.02 1565.24   93.69
#Mann= 1 ,-1 , 0
       0     .05       0
Bank Sta=848.92,1116.91
XS Rating Curve= 0
Exp/Cntr=.3,.1

Type RM Length L Ch R = 1 ,1132.226,162.9,169.09,213.79
XS GIS Cut Line= 4
 3066341.111592813866368.0571317 3066620.554603513865556.0984538
 3066882.743383613865452.2121786 3066857.009006913865139.9735256
#Sta/Elev= 30
       0    91.8   44.42   93.59  103.64   92.54  177.66    92.7  207.27   91.08
  222.08   91.21  266.49   94.38   296.1   97.42  355.32   97.61  399.74   97.37
  444.15   92.96  518.18   90.73  666.23   91.91  725.45   91.45  784.67   93.62
  814.28   93.65  873.54   91.93  918.07   90.86  947.76   88.64   962.6    88.5
 1036.82   90.45  1066.5   89.51 1111.03   91.79 1140.72   91.06 1170.56   91.73
 1200.39   89.25 1215.31   89.06 1289.91   89.17 1349.58   91.01 1454.01   95.23
#Mann= 1 ,-1 , 0
       0     .05       0
Bank Sta=873.54,1349.58
XS Rating Curve= 0
Exp/Cntr=.3,.1

Type RM Length L Ch R = 1 ,963.1334,178.38,288.13,212.38
XS GIS Cut Line= 5
 3066510.856660113866368.5915795 3066749.175737313865684.7192596
 3066961.894800113865590.7269935 3067037.542286613865468.2780914
 3067025.388083313865319.2743306
#Sta/Elev= 30
       0   91.65   29.56   91.54    73.9   92.16  162.58    92.4  177.36   92.26
  206.92   90.52  236.48   91.62  280.82   92.38  339.93   92.73  428.61   91.94
  443.39    90.9  458.17   89.17  472.95   88.65  532.07   88.44  591.19   90.84
  620.75   93.65  679.87   93.55  709.43    92.6  724.21   91.61  738.74   90.14
  753.28   89.26  825.95    88.8  855.02    89.8  884.09   89.99   927.7   91.05
 1014.34   91.79  1100.7   91.39 1115.65   91.54  1190.4   93.66  1250.2   94.11
#Mann= 1 ,-1 , 0
       0     .05       0
Bank Sta=724.21,1014.34
XS Rating Curve= 0
Exp/Cntr=.3,.1

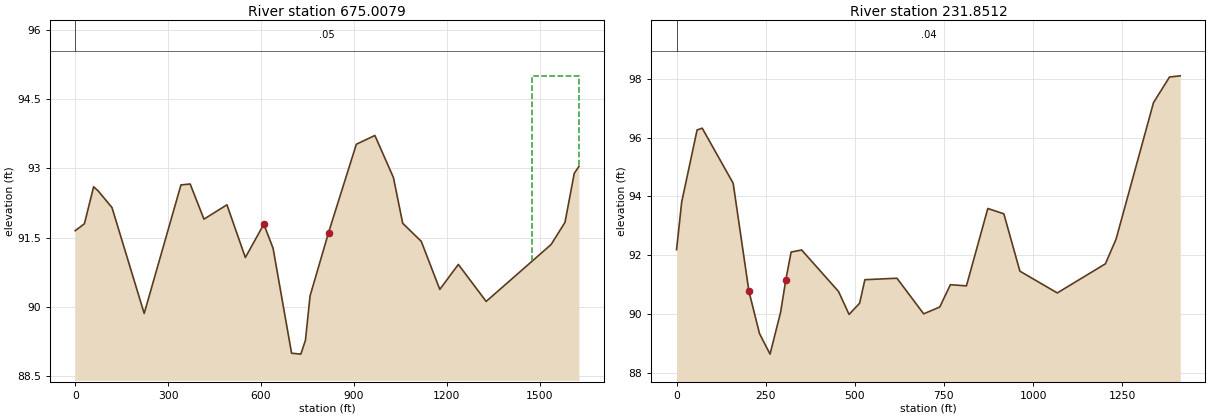
Type RM Length L Ch R = 1 ,675.0079,325.82,443.16,298.54
XS GIS Cut Line= 4
 3066696.928466513866372.6460333  3066870.04426213865851.3035721
 3067169.667350413865758.9238356 3067107.129594113864997.9515511
#Sta/Elev= 30
       0   91.65   29.69    91.8   59.39    92.6   74.23   92.51  118.77   92.15
   222.7   89.86  341.48   92.64  371.17   92.66  415.71    91.9  489.95   92.21
  549.33   91.07  609.06   91.79  638.92   91.27  698.64      89   728.5   88.98
  743.43   89.28  758.36   90.24  818.08   91.61  907.79   93.52  967.67   93.71
 1027.56    92.8  1057.5   91.81 1117.39   91.42 1177.27   90.38 1237.16   90.92
 1326.99   90.12 1536.59   91.35  1581.5   91.83 1611.44   92.89 1626.41   93.04
#Mann= 1 ,-1 , 0
       0     .05       0
#XS Ineff= 1 ,-1
 1476.39 1626.41      95
Permanent Ineff=
       F
Bank Sta=609.06,818.08
XS Rating Curve= 0
Exp/Cntr=.3,.1

Type RM Length L Ch R = 1 ,231.8512,0,0,0
XS GIS Cut Line= 4
 3067015.617133613866413.3027761 3067065.781075213866278.3545552
 3067295.256666113865970.0533346 3067222.113512813865088.4312072
#Sta/Elev= 30
       0   92.19    14.4   93.81   57.59   96.26   71.98   96.32  158.75   94.45
   203.1   90.77  232.66   89.34  262.23   88.64  291.79   90.06  306.57   91.17
  321.35   92.11  350.92   92.18  454.39   90.77  483.95   89.99  513.52   90.37
   528.3   91.17  618.26   91.22  693.23   90.01  738.22   90.24   768.2      91
  813.19   90.96  873.16   93.59  918.14   93.41  963.13   91.46 1068.08   90.72
 1203.03   91.71 1233.02   92.55 1337.98   97.19 1382.96   98.06 1412.95    98.1
#Mann= 1 ,-1 , 0
       0     .04       0
Bank Sta=203.1,306.57
XS Rating Curve= 0
Exp/Cntr=.3,.1

River Reach=E115-00-00      ,E115-00-00_0009
Reach XY= 30
 3067352.1176145 13866285.040838      3068770.85     13866305.09
      3069872.41     13866045.54      3070842.03     13866096.76
      3072842.03     13864866.72      3073510.43     13864035.99
      3074141.51     13864028.18      3074718.76     13863594.15
      3076132.82     13863759.95      3077320.32     13863539.47
      3077664.94     13863667.94      3078360.26     13863482.17
      3078943.59     13863522.11      3079330.74     13863351.97
      3080056.44     13863421.41      3081340.29     13863841.55
      3082519.11     13863864.12       3084098.1     13864799.88
      3085315.98     13864856.31      3085732.25       13865293.
       3086573.8     13865568.11      3087478.31     13865604.57
      3088072.06     13865286.86      3089109.39     13865567.25
      3089530.39     13865213.08      3090260.43     13865063.77
        3091033.     13865246.93        3091408.     13865078.53
      3091656.26      13864541.2      3092044.28     13864494.33

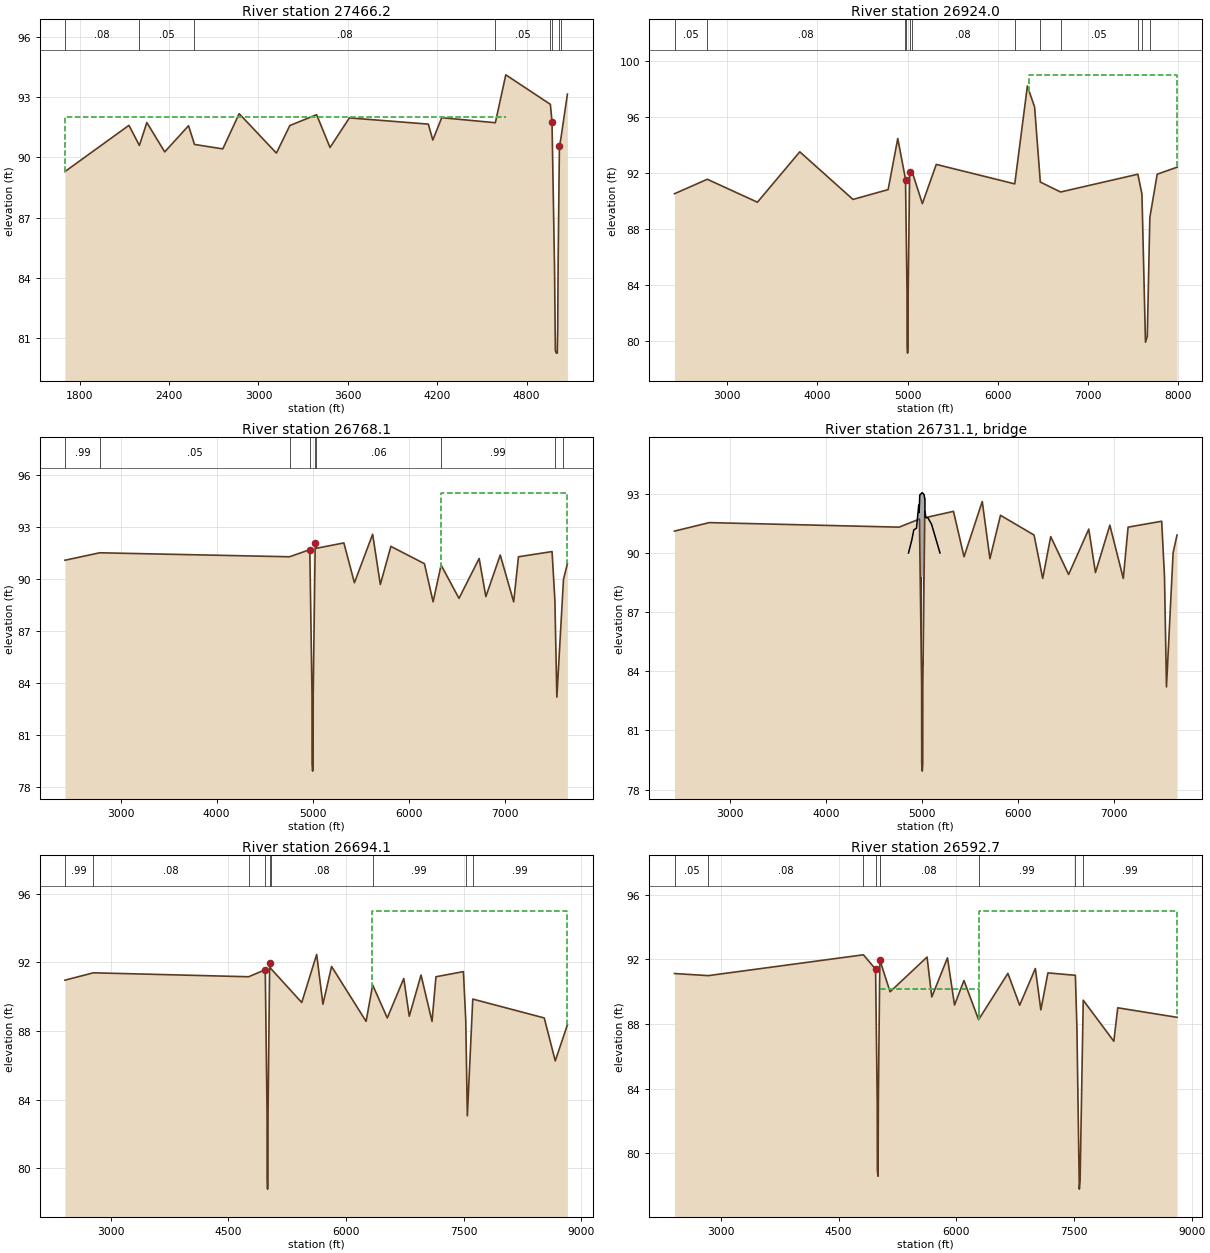
Type RM Length L Ch R = 1 ,27466.2 ,479.6,542.2,618.7
BEGIN DESCRIPTION:
CLAY RD - XS 1
Interplotated channel, LIDAR overbanks
Levees are not FEMA regulated levees, only RAS levees to prevent spilling into E115-09-00.
Cross-Section would need to be extended across E117-00-00 channel in order to contain all flood events.
END DESCRIPTION:
XS GIS Cut Line= 3
      3067730.19     13869352.31      3067666.27     13866392.99
      3067260.68     13866309.54
#Sta/Elev= 30
  1700.6   89.29  2130.6   91.59  2200.6   90.59  2250.6   91.73  2370.6   90.27
  2530.6   91.57  2570.6   90.64  2760.6   90.42  2870.6   92.17  3120.6   90.21
  3210.6   91.58  3390.6   92.12  3480.6   90.49  3610.6   91.96  4140.6   91.65
  4170.6   90.86  4230.6   91.97  4590.6   91.72  4660.6    94.1    4960  92.633
 4970.93   91.77 4987.88   84.53 4993.51    80.4 5000.05   80.27 5006.22   80.27
  5009.1    81.4 5012.11    84.8  5020.6   90.54  5030.6   90.94 5074.33   93.14
#Mann= 8 ,-1 , 0
  1700.6     .08       0  2200.6     .05       0  2570.6     .08       0
  4590.6     .05       0    4960     .04       0 4970.93    .025       0
  5020.6     .04       0  5030.6    .045       0
#XS Ineff= 1 ,-1
  1700.6  4660.6      92
Permanent Ineff=
       F
Bank Sta=4970.93,5020.6
XS Rating Curve= 0
Exp/Cntr=.3,.1

Type RM Length L Ch R = 1 ,26924.0 ,153.8,155.9,155.2
BEGIN DESCRIPTION:
SPRING VALLEY - XS 4
Cross Section x21
Located At: US FITZE LANE
Levees are not FEMA regulated levees, only RAS levees to prevent spilling into E115-09-00.
END DESCRIPTION:
XS GIS Cut Line= 5
      3067800.67       13868854.      3067833.56     13866524.83
      3067841.32     13866100.65      3067257.46      13865097.6
      3067075.75     13862549.38
#Sta/Elev= 30
  2414.6   90.51  2778.3   91.54  3334.2    89.9  3804.2    93.5  4394.2    90.1
  4784.1    90.8  4891.1   94.45  4973.3   91.67  4977.1   91.49  4993.8   83.51
  4994.7   79.51  4999.8   79.12  5005.6    79.5  5006.5   83.52  5023.1   92.05
  5044.1    92.2  5164.1    89.8  5318.3    92.6  6189.1   91.21    6329    98.2
    6409    96.7  6472.5   91.34  6697.3   90.63  7554.6    91.9  7599.9   90.48
    7639    79.9    7659    80.3  7687.4    88.8    7769    91.9    7989    92.4
#Mann= 12 ,-1 , 0
  2414.6     .05       0  2778.3     .08       0  4973.3     .04       0
  4977.1    .025       0  5023.1     .04       0  5044.1     .08       0
  6189.1    .045       0  6472.5     .08       0  6697.3     .05       0
  7554.6     .99       0  7599.9     .99       0  7687.4     .99       0
#XS Ineff= 1 ,-1
    6350    7989      99
Permanent Ineff=
       F
Bank Sta=4977.1,5023.1
XS Rating Curve= 0
Exp/Cntr=.5,.3

Type RM Length L Ch R = 1 ,26768.1 ,74.2,74,74.4
BEGIN DESCRIPTION:
SPRING VALLEY - XS 3
Levees are not FEMA regulated levees, only RAS levees to prevent spilling into E115-09-00.
END DESCRIPTION:
XS GIS Cut Line= 5
      3067979.73      13868870.2      3067978.79     13866700.01
      3068002.88     13865951.39      3067677.27       13862505.
      3067675.24      13862483.5
#Sta/Elev= 30
  2418.1   91.11  2780.9   91.54  4759.1   91.31  4970.8   91.72  4993.8   83.34
  4994.5   79.35  5000.1   78.94  5005.3    79.3    5006   83.31  5026.9   92.11
  5039.5    91.8  5325.7   92.11  5435.7   89.81  5625.7   92.61  5705.7   89.71
  5815.7   91.91  6165.7   90.91  6255.7   88.71  6339.2   90.83  6525.7   88.91
  6735.7   91.21  6805.7   89.01  6955.7   91.41  7095.7   88.71  7145.7   91.31
  7495.7   91.61  7525.2    88.8  7545.7   83.21  7614.9   90.01  7655.7   90.91
#Mann= 9 ,-1 , 0
  2418.1     .99       0  2780.9     .05       0  4759.1    .035       0
  4970.8    .015       0  5026.9    .035       0  5039.5     .06       0
  6339.2     .99       0  7525.2     .04       0  7614.9     .99       0
#XS Ineff= 3 ,-1
  2418.1  4960.8    90.5  5036.9    6333    90.5    6333  7655.7      95
Permanent Ineff=
       F       F       F
Bank Sta=4970.8,5026.9
XS Rating Curve= 0
Exp/Cntr=.5,.3

Type RM Length L Ch R = 3 ,26731.1 ,,,
BEGIN DESCRIPTION:
SPRING VALLEY ROAD
Structure ID: E115-00-00-18
END DESCRIPTION:
Bridge Culvert--1,0,-1,-1, 0
Deck Dist Width WeirC Skew NumUp NumDn MinLoCord MaxHiCord MaxSubmerge Is_Ogee
10,54,2.6,0, 44, 44, , , .95, 0, ,,,
  4856.8  4891.3  4905.1  4911.8  4940.1  4963.3 4967.09  4967.2 4967.31  4970.8
  4973.9 4974.01 4974.12 4982.21  4982.3  4993.3  4993.8  4994.5  4995.2  4996.1
  4996.6  5000.1  5001.5  5003.8  5004.7  5005.3    5006  5006.6 5015.19  5015.3
  5021.6  5021.7 5021.81  5026.9 5028.19  5028.3 5028.41  5030.9  5039.5  5054.4
  5060.8  5097.5  5097.6    5185
      90   90.66      91   91.17   91.26   92.43   92.07   92.06   92.05   92.45
   92.92   92.94   92.94   92.98   92.98   93.03   93.03   93.03   93.04   93.04
   93.04   93.05   93.05   93.04   93.03   93.03   93.03   93.02   92.98   92.97
   92.94   92.88   92.87   92.76   92.73   92.73      92   91.81    91.8   91.78
   91.77   91.45   91.45      90
                                                                                
                                   88.78   88.83   88.83   88.83   88.84   88.84
   88.84   88.85   88.85   88.84   88.83   88.83   88.83   88.82   88.78
                                                                                
                                
  4856.8  4891.3  4905.1  4911.8  4940.1  4963.3 4967.09  4967.2 4967.31  4970.8
  4973.9 4974.01 4974.12 4982.21  4982.3  4993.3  4993.8  4994.5  4995.2  4996.1
  4996.6  5000.1  5001.5  5003.8  5004.7  5005.3    5006  5006.6 5015.19  5015.3
  5021.6  5021.7 5021.81  5026.9 5028.19  5028.3 5028.41  5030.9  5039.5  5054.4
  5060.8  5097.5  5097.6    5185
      90   90.66      91   91.17   91.26   92.43   92.07   92.06   92.05   92.45
   92.92   92.94   92.94   92.98   92.98   93.03   93.03   93.03   93.04   93.04
   93.04   93.05   93.05   93.04   93.03   93.03   93.03   93.02   92.98   92.97
   92.94   92.88   92.87   92.76   92.73   92.73      92   91.81    91.8   91.78
   91.77   91.45   91.45      90
                                                                                
                                   88.78   88.83   88.83   88.83   88.84   88.84
   88.84   88.85   88.85   88.84   88.83   88.83   88.83   88.82   88.78
                                                                                
                                
Pier Skew, UpSta & Num, DnSta & Num=  ,4988.7, 2 ,4988.7, 2 , 0 , 0 , 0 ,,
     1.5     1.5
   83.78   89.81
     1.5     1.5
   83.66   89.69
Pier Skew, UpSta & Num, DnSta & Num=  ,5008.4, 2 ,5008.4, 2 , 0 , 0 , 0 ,,
     1.5     1.5
   82.81   89.82
     1.5     1.5
   82.69    89.7
BR Coef= 1 , 1 , 1 ,1.05, 0 ,,,.8,0,1.2,0,
WSPro=,,,, 1 ,,,, 0 ,,,, 0 ,,,,-1 ,-1 ,-1 , 0 , 0 , 0 , 0 , 0
BC Design=,, 0 ,, 0 ,,,,,,
BC HTab HWMax=92.61

Type RM Length L Ch R = 1 ,26694.1 ,102.3,101.4,102.5
BEGIN DESCRIPTION:
SPRING VALLEY - XS 2
Levees are not FEMA regulated levees, only RAS levees to prevent spilling into E115-09-00.
END DESCRIPTION:
XS GIS Cut Line= 5
       3068045.4      13868867.8      3068044.46      13866700.8
      3068068.62     13865949.84      3067742.72     13862500.31
      3067740.91      13862481.1
#Sta/Elev= 30
  2418.1   90.96  2780.9   91.39  4759.1   91.16  4970.8   91.57  4993.8   83.19
  4994.5    79.2  5000.1   78.79  5005.3   79.15    5006   83.16  5026.9   91.96
  5039.5   91.65  5435.7   89.66  5625.7   92.46  5705.7   89.56  5815.7   91.76
  6255.7   88.56  6339.2   90.68  6525.7   88.76  6735.7   91.06  6805.7   88.86
  6955.7   91.26  7095.7   88.56  7145.7   91.16  7495.7   91.46  7525.2   88.65
  7545.7   83.06  7614.9   89.86  8525.7   88.76  8665.7   86.26  8820.6   88.36
#Mann= 9 ,-1 , 0
  2418.1     .99       0  2780.9     .08       0  4759.1     .04       0
  4970.8    .015       0  5026.9     .04       0  5039.5     .08       0
  6339.2     .99       0  7525.2     .04       0  7614.9     .99       0
#XS Ineff= 3 ,-1
  2418.1 4964.13      90 5033.57    6333      90    6333  8820.6      95
Permanent Ineff=
       F       F       F
Bank Sta=4970.8,5026.9
XS Rating Curve= 0
Exp/Cntr=.5,.3

Type RM Length L Ch R = 1 ,26592.7 ,385.1,386.3,390
BEGIN DESCRIPTION:
SPRING VALLEY - XS 1
Interplotated channel, LIDAR overbanks
Levees are not FEMA regulated levees, only RAS levees to prevent spilling into E115-09-00.
END DESCRIPTION:
XS GIS Cut Line= 4
      3068147.84      13868872.2      3068155.62     13866705.42
      3068179.78     13865954.46      3067843.34     13862485.53
#Sta/Elev= 30
  2409.9   91.12  2839.9   90.99  4816.7   92.28 4971.92   91.39 4993.04   83.11
 4994.63   78.94 5003.61   78.58 5007.23   83.27 5026.19   91.98 5026.49   91.96
  5156.7   89.99    5628   92.14    5688   89.67    5888   92.09    5978   89.17
    6098   90.696284.556  88.265    6658   91.13    6808   89.16    7008   91.43
    7078   88.87    7168   91.16    7518   91.01    7538   87.67    7568   77.78
    7578   78.32    7618   89.47    8008   86.93    8058      89  8813.2   88.41
#Mann= 9 ,-1 , 0
  2409.9     .05       0  2839.9     .08       0  4816.7     .04       0
 4971.92    .015       0 5026.19     .04       0 5026.49     .08       0
6284.556     .99       0    7518     .04       0    7618     .99       0
#XS Ineff= 3 ,-1
  2409.9 4966.64 90.14975031.4766284.556 90.14976284.556  8813.2      95
Permanent Ineff=
       F       F       F
Bank Sta=4971.92,5026.19
XS Rating Curve= 0
Exp/Cntr=.3,.1