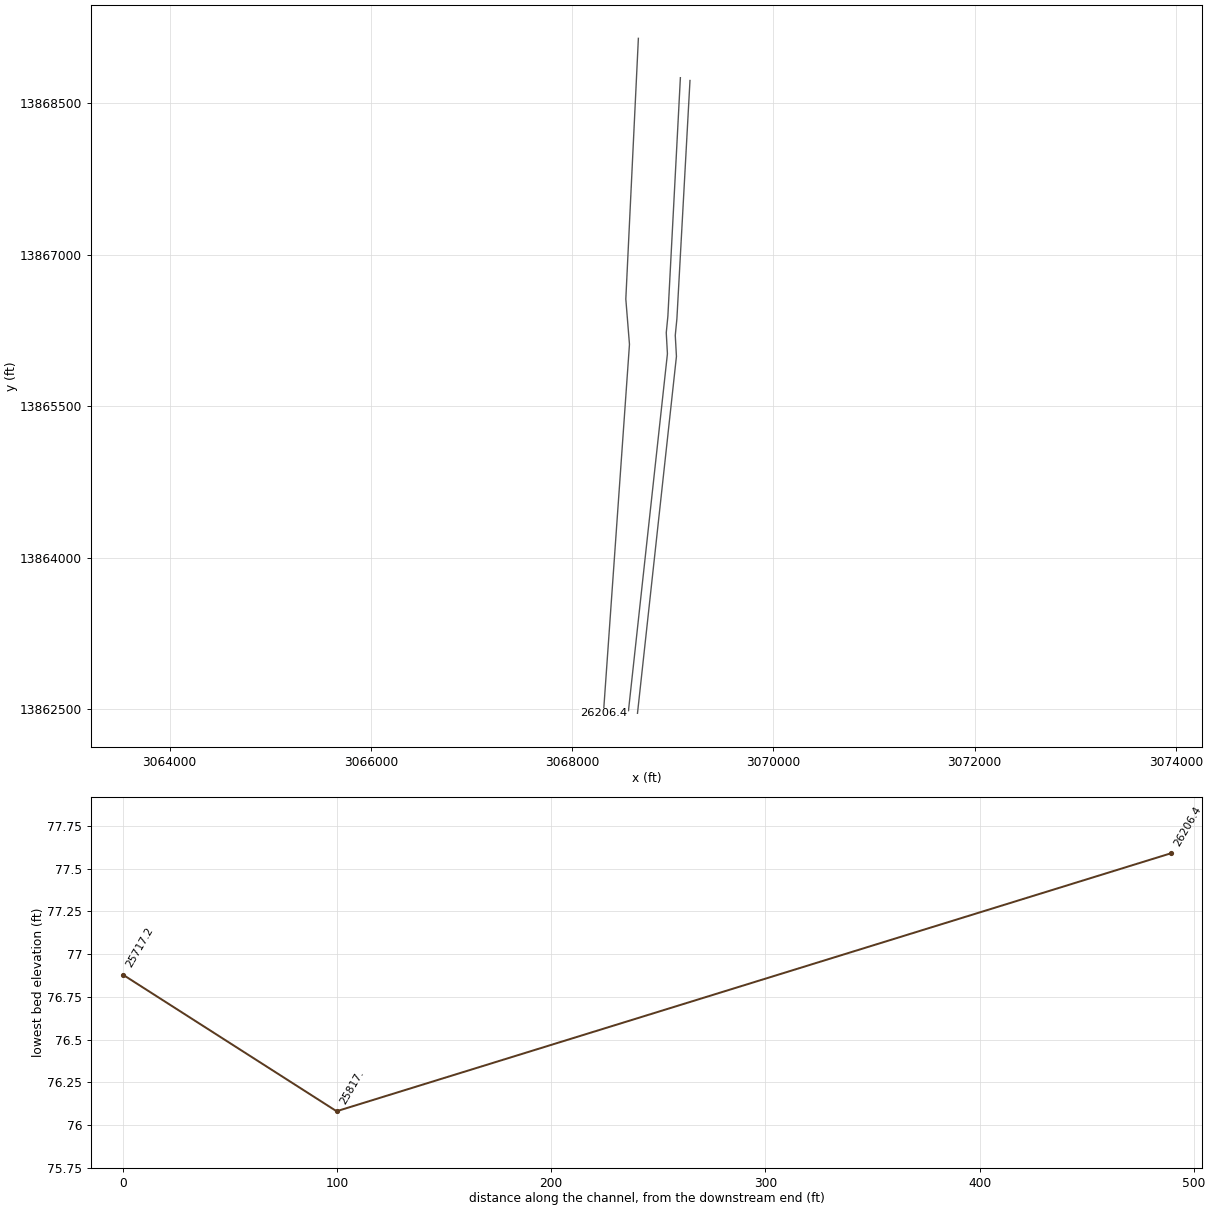
HEC-RAS study E115-00-00.prj: E115-00-00

--- E115-00-00.g01 (geometry) --- (continued)

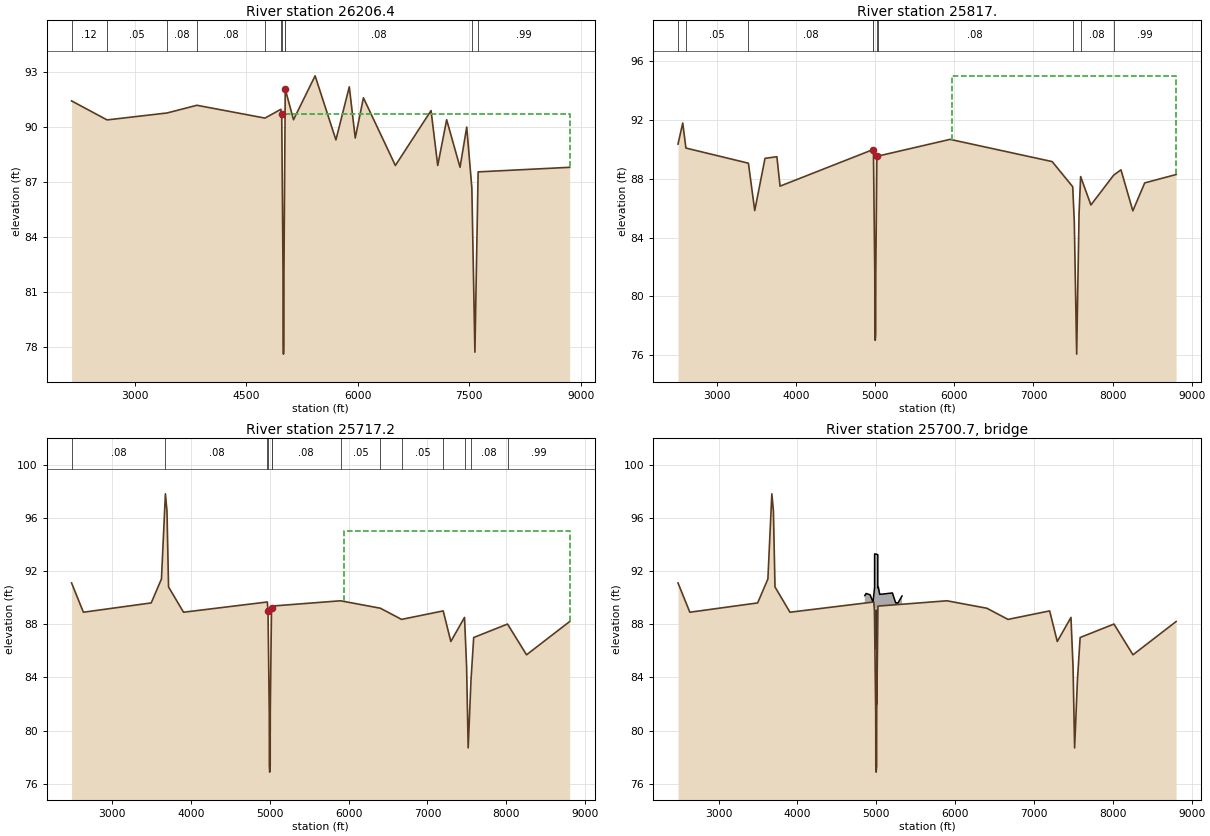
Type RM Length L Ch R = 1 ,26206.4 ,394.2,389.4,380.7
BEGIN DESCRIPTION:
Cross Section x20
Located At: U/S CLARBLAK LANE
Levees are not FEMA regulated levees, only RAS levees to prevent spilling into E115-09-00.
END DESCRIPTION:
XS GIS Cut Line= 4
       3068658.7     13869145.47      3068533.84     13866562.23
      3068570.13     13866113.14      3068311.39     13862457.29
#Sta/Elev= 30
  2148.6   91.43  2626.5   90.39  3433.6   90.77  3835.1   91.19  4751.3   90.49
  4964.2   90.97  4976.2   90.72  4993.8   82.05  4994.5   78.03  4999.6   77.59
  5005.5   77.99  5006.2   81.98  5023.5   92.08  5023.8   92.07  5134.9    90.4
  5425.4    92.8  5705.4    89.3  5885.4    92.2  5965.4    89.4  6075.4    91.6
  6505.4    87.9  6985.4    90.9  7075.4    87.9  7195.4    90.4  7375.4    87.8
  7465.4      90  7534.3   86.68  7575.4    77.7  7618.9   87.55  8850.4    87.8
#Mann= 11 ,-1 , 0
  2148.6     .12       0  2626.5     .05       0  3433.6     .08       0
  3835.1     .08       0  4751.3     .05       0  4964.2     .04       0
  4976.2    .015       0  5023.5     .04       0  5023.8     .08       0
  7534.3     .04       0  7618.9     .99       0
#XS Ineff= 2 , 0
       0  4976.2   90.72  5023.5       0   90.72
Permanent Ineff=
       F       F
Bank Sta=4976.2,5023.5
XS Rating Curve= 0
Exp/Cntr=.3,.1

Type RM Length L Ch R = 1 ,25817.  ,98.3,99.8,97.4
BEGIN DESCRIPTION:
CLARBLAK - XS 4
Interplotated channel, LIDAR overbanks
Levees are not FEMA regulated levees, only RAS levees to prevent spilling into E115-09-00.
END DESCRIPTION:
XS GIS Cut Line= 5
      3069076.18     13868755.58      3068951.88     13866392.79
      3068935.76     13866228.37      3068947.37     13866020.17
      3068560.24     13862484.34
#Sta/Elev= 30
  2506.2   90.36  2566.2   91.79  2606.2   90.09  3396.2   89.06  3476.2   85.84
  3606.2   89.39  3756.2    89.5  3796.2    87.5    4965  89.973 4976.79   89.93
  4993.8   81.48  4994.5   77.46  4999.6   77.02  5005.5   77.42  5006.2   81.41
 5020.24   89.52    5030  89.539    5946   90.68    7236   89.17    7496   87.46
    7516   85.07    7546   76.08    7576   85.62    7596   88.15    7726   86.22
    8014  88.249    8106   88.61    8256   85.82    8406   87.72  8802.9   88.29
#Mann= 10 ,-1 , 0
  2506.2     .12       0  2606.2     .05       0  3396.2     .08       0
    4965     .04       0 4976.79    .015       0 5020.24     .04       0
    5030     .08       0    7496     .04       0    7596     .08       0
    8014     .99       0
#XS Ineff= 3 ,-1
  2506.24969.35489.032495030.1065969.45788.152165969.457  8802.9      95
Permanent Ineff=
       F       F       F
Bank Sta=4976.79,5020.24
XS Rating Curve= 0
Exp/Cntr=.5,.3

Type RM Length L Ch R = 1 ,25717.2 ,43.4,41,45.7
BEGIN DESCRIPTION:
CLARBLAK - XS 3
Levees are not FEMA regulated levees, only RAS levees to prevent spilling into E115-09-00.
END DESCRIPTION:
XS GIS Cut Line= 5
      3069171.66      13868727.7      3069041.48     13866366.62
      3069025.36      13866202.2      3069036.97       13865994.
      3068649.84     13862458.17
#Sta/Elev= 30
  2486.2    91.1  2636.2    88.9  3496.2    89.6  3626.2    91.4  3676.2    97.8
  3696.2    96.5  3716.2    90.8  3906.2    88.9  4968.9   89.67  4977.6   88.98
  4993.7   81.27  4994.8   77.31  4999.1   76.88  5005.4   77.34  5006.1   81.38
  5021.8   89.19  5022.7   89.36    5897   89.76  6402.7    89.2  6671.2   88.36
  7199.3      89    7296    86.7  7469.7   88.51    7496    84.8    7516    78.7
  7551.7    83.8    7586      87  8014.9   88.01    8256    85.7    8803    88.2
#Mann= 13 ,-1 , 0
  2486.2     .08       0  3676.2     .08       0  4968.9     .04       0
  4977.6    .015       0  5021.8     .04       0  5022.7     .08       0
    5897     .05       0  6402.7     .08       0  6671.2     .05       0
  7199.3     .08       0  7469.7     .04       0  7551.7     .08       0
  8014.9     .99       0
#XS Ineff= 3 ,-1
  2486.2  4967.6    88.6  5031.8    5936    88.7    5936    8803      95
Permanent Ineff=
       F       F       F
Bank Sta=4977.6,5021.8
XS Rating Curve= 0
Exp/Cntr=.5,.3

Type RM Length L Ch R = 3 ,25700.7 ,,,
BEGIN DESCRIPTION:
CLARBLAK LANE and Pipeline upstream
Structure ID: E115-00-00-17 includes pipeline piers.
END DESCRIPTION:
Bridge Culvert--1,0,-1,-1, 0
Deck Dist Width WeirC Skew NumUp NumDn MinLoCord MaxHiCord MaxSubmerge Is_Ogee
10,29,2.6,0, 60, 60, , , .95, 0, ,,,
  4854.9  4872.3    4883  4922.3    4943    4953  4960.8  4962.7  4962.8  4968.9
  4970.4 4974.71  4974.8  4977.6 4979.09  4979.2 4979.31  4983.5  4985.7 4985.81
  4993.3 4993.41  4993.7  4994.8  4995.8  4996.6  4999.1  5002.7  5004.1  5005.4
  5006.1  5006.7  5007.4  5012.8 5020.09  5020.2 5020.31  5021.8  5022.7  5024.9
  5027.4 5027.51  5028.1 5032.69  5032.8  5036.3    5044  5044.1  5060.6  5205.2
  5205.3  5207.5  5237.5    5246  5247.3    5266  5277.3    5296  5297.3  5327.3
   90.15   90.31   90.29   90.21    89.9   89.75   89.74   89.85   89.86    90.2
   90.28   90.52   90.53   90.69   90.77   93.27   93.27   93.27   93.27   93.28
   93.27   93.27   93.27   93.27   93.27   93.26   93.26   93.26   93.25   93.25
   93.25   93.25   93.25   93.24   93.23   93.23   90.73   90.74   90.74   90.76
   90.77   90.77   90.75    90.6    90.6   90.49   90.24   90.24   90.25   90.35
   90.35   90.31   89.77   89.62    89.6    89.6    89.6   89.81   89.82   90.12
                                                                                
                                           89.17   89.17   89.17   89.17   89.18
   89.17   89.17   89.17   89.17   89.17   89.16   89.16   89.16   89.15   89.15
   89.15   89.15   89.15   89.14   89.13   89.13
                                                                                
                                                                                
  4854.9  4872.3    4883  4922.3    4943    4953  4960.8  4962.7  4962.8  4968.9
  4970.4 4974.71  4974.8  4977.6 4979.09  4979.2 4979.31  4983.5  4985.7 4985.81
  4993.3 4993.41  4993.7  4994.8  4995.8  4996.6  4999.1  5002.7  5004.1  5005.4
  5006.1  5006.7  5007.4  5012.8 5020.09  5020.2 5020.31  5021.8  5022.7  5024.9
  5027.4 5027.51  5028.1 5032.69  5032.8  5036.3    5044  5044.1  5060.6  5205.2
  5205.3  5207.5  5237.5    5246  5247.3    5266  5277.3    5296  5297.3  5327.3
   90.15   90.31   90.29   90.21    89.9   89.75   89.74   89.85   89.86    90.2
   90.28   90.52   90.53   90.69   90.77   93.27   93.27   93.27   93.27   93.28
   93.27   93.27   93.27   93.27   93.27   93.26   93.26   93.26   93.25   93.25
   93.25   93.25   93.25   93.24   93.23   93.23   90.73   90.74   90.74   90.76
   90.77   90.77   90.75    90.6    90.6   90.49   90.24   90.24   90.25   90.35
   90.35   90.31   89.77   89.62    89.6    89.6    89.6   89.81   89.82   90.12
                                                                                
                                           89.17   89.17   89.17   89.17   89.18
   89.17   89.17   89.17   89.17   89.17   89.16   89.16   89.16   89.15   89.15
   89.15   89.15   89.15   89.14   89.13   89.13
                                                                                
                                                                                
Pier Skew, UpSta & Num, DnSta & Num=  ,4983.5, 2 ,4983.5, 2 , 0 , 0 , 0 ,,
       1       1
   84.05   91.06
       1       1
   84.05   91.06
Pier Skew, UpSta & Num, DnSta & Num=  ,4993.4, 2 ,4993.4, 2 , 0 , 0 , 0 ,,
     1.5     1.5
   80.38   90.15
     1.5     1.5
   80.32   90.09
Pier Skew, UpSta & Num, DnSta & Num=  ,5007.4, 2 ,5007.4, 2 , 0 , 0 , 0 ,,
     1.5     1.5
   78.65   90.17
     1.5     1.5
   78.59   90.11
Pier Skew, UpSta & Num, DnSta & Num=  ,5012.8, 2 ,5012.8, 2 , 0 , 0 , 0 ,,
       1       1
   84.39   91.13
       1       1
   84.39   91.13
BR Coef= 1 , 1 , 1 ,1.05, 0 ,,,.8,0,1.2,0,
WSPro=,,,, 1 ,,,, 0 ,,,, 0 ,,,,-1 ,-1 ,-1 , 0 , 0 , 0 , 0 , 0
BC Design=,, 0 ,, 0 ,,,,,,
BC HTab HWMax=98.2