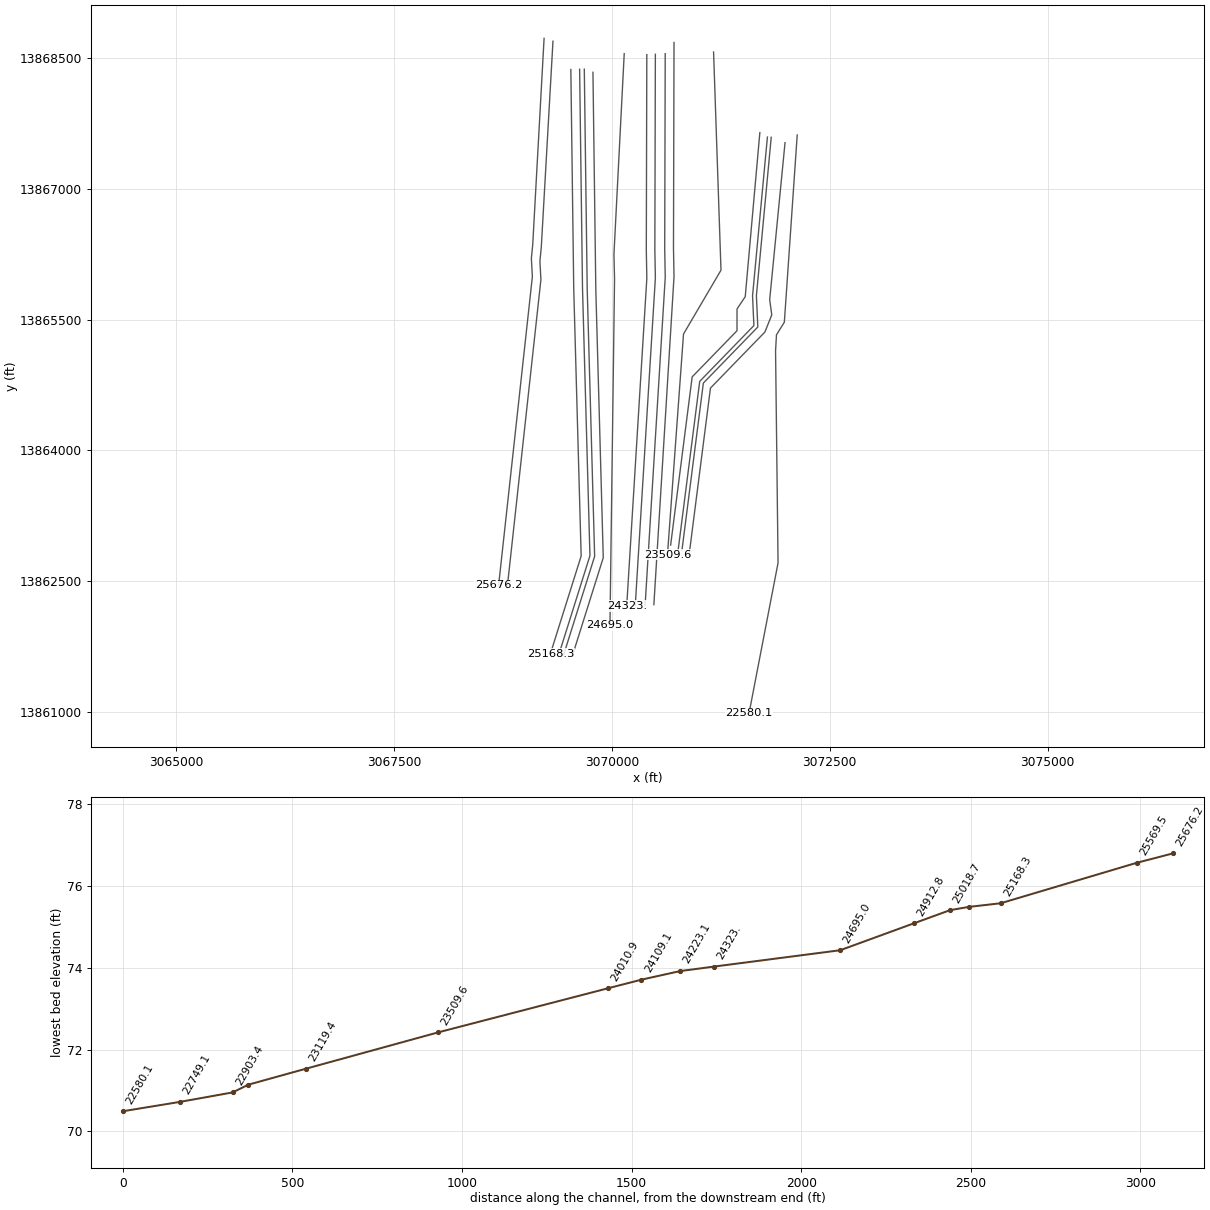
HEC-RAS study E115-00-00.prj: E115-00-00

--- E115-00-00.g01 (geometry) --- (continued)

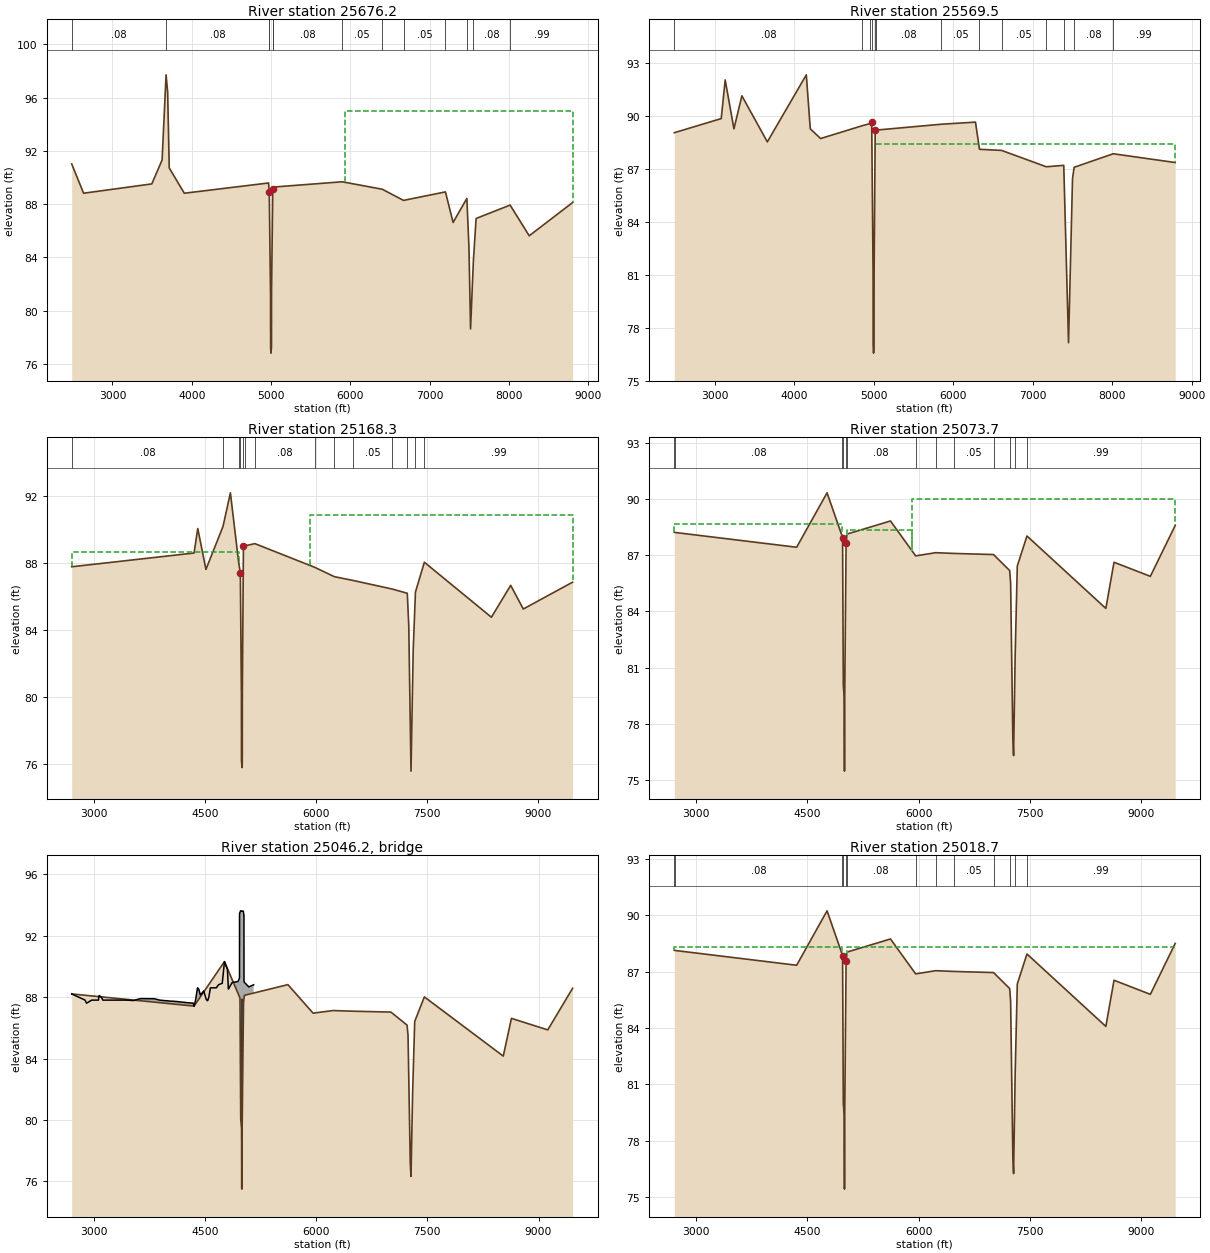
Type RM Length L Ch R = 1 ,25676.2 ,101.5,106.7,101.2
BEGIN DESCRIPTION:
CLARBLAK - XS 2
Levees are not FEMA regulated levees, only RAS levees to prevent spilling into E115-09-00.
END DESCRIPTION:
XS GIS Cut Line= 5
      3069220.75      13868725.6      3069090.52     13866363.43
      3069074.67     13866201.78       3069086.3     13865993.29
      3068698.71     13862453.36
#Sta/Elev= 30
  2486.2   91.02  2636.2   88.82  3496.2   89.52  3626.2   91.32  3676.2   97.72
  3696.2   96.42  3716.2   90.72  3906.2   88.82  4968.9   89.59  4977.6    88.9
  4993.7   81.19  4994.8   77.23  4999.1    76.8  5005.4   77.26  5006.1    81.3
  5021.8   89.11  5022.7   89.28    5897   89.68  6402.7   89.12  6671.2   88.28
  7199.3   88.92    7296   86.62  7469.7   88.43    7496   84.72    7516   78.62
  7551.7   83.72    7586   86.92  8014.9   87.93    8256   85.62    8803   88.12
#Mann= 13 ,-1 , 0
  2486.2     .08       0  3676.2     .08       0  4968.9     .04       0
  4977.6    .015       0  5021.8     .04       0  5022.7     .08       0
    5897     .05       0  6402.7     .08       0  6671.2     .05       0
  7199.3     .08       0  7469.7     .04       0  7551.7     .08       0
  8014.9     .99       0
#XS Ineff= 3 ,-1
  2486.2 4970.93    88.6 5028.47    5936    88.7    5936    8803      95
Permanent Ineff=
       F       F       F
Bank Sta=4977.6,5021.8
XS Rating Curve= 0
Exp/Cntr=.5,.3

Type RM Length L Ch R = 1 ,25569.5 ,383.4,401.2,397.5
BEGIN DESCRIPTION:
CLARBLAK - XS 1
Interplotated channel, LIDAR overbanks
Levees are not FEMA regulated levees, only RAS levees to prevent spilling into E115-09-00.
END DESCRIPTION:
XS GIS Cut Line= 5
      3069322.77     13868692.69      3069188.61     13866330.45
      3069172.76     13866168.79      3069184.39      13865960.3
       3068796.8     13862420.38
#Sta/Elev= 30
    2494   89.06    3084   89.86    3134   92.05    3244   89.28    3344   91.15
    3664   88.54    4154   92.34    4204   89.28    4334   88.73  4860.1   89.46
    4960  89.579 4976.33   89.66  4993.8   81.03  4994.5   77.01  4999.6   76.57
  5005.5   76.97  5006.2   80.96 5020.43   89.23    5030  89.207  5851.3   89.54
  6281.3   89.66  6331.3   88.12    6610  88.057  7171.3   87.13  7391.3   87.21
  7451.3   77.16  7501.3   86.45  7521.3    87.1    8014  87.867  8792.4   87.37
#Mann= 13 ,-1 , 0
    2494     .08       0  4860.1     .05       0    4960     .04       0
 4976.33    .015       0 5020.43     .04       0    5030     .08       0
  5851.3     .05       0  6331.3     .08       0    6610     .05       0
  7171.3     .08       0  7391.3     .04       0  7521.3     .08       0
    8014     .99       0
#XS Ineff= 2 , 0
       04969.70388.610635029.024       088.40366
Permanent Ineff=
       F       F
Bank Sta=4976.33,5020.43
XS Rating Curve= 0
Exp/Cntr=.3,.1

Type RM Length L Ch R = 1 ,25168.3 ,103.3,94.6,103.9
BEGIN DESCRIPTION:
CAMPBELL RD - XS 4
Interplotated channel, LIDAR overbanks
Levees are not FEMA regulated levees, only RAS levees to prevent spilling into E115-09-00.
END DESCRIPTION:
XS GIS Cut Line= 4
      3069527.84     13868367.94      3069561.07      13865852.8
      3069646.29     13862789.61      3069293.25     13861669.09
#Sta/Elev= 30
  2705.4   87.77  4355.4   88.59  4405.4   90.05  4515.4   87.61  4745.4   90.17
  4845.4   92.18  4955.4   88.08  4979.3    87.4  4993.8   80.21  4994.5   76.19
  5003.4   75.79  5005.5   76.15  5006.2   80.14 5021.06      89  5045.4   89.02
  5175.4   89.15  5980.8   87.74    6245  87.182    6505  86.948    7026  86.442
  7230.8   86.19  7250.8   84.24  7280.8   75.58  7310.8   82.85  7340.8   86.26
  7460.8   88.04  8365.1   84.76  8625.1   86.66  8795.1   85.25    9460   86.85
#Mann= 14 ,-1 , 0
  2705.4     .08       0  4745.4     .05       0  4955.4     .04       0
  4979.3    .015       0 5021.06     .04       0  5045.4     .05       0
  5175.4     .08       0  5980.8     .05       0    6245     .08       0
    6505     .05       0    7026     .08       0  7230.8     .04       0
  7340.8     .08       0  7460.8     .99       0
#XS Ineff= 3 ,-1
  2705.44965.15788.649995031.0775918.50686.713745918.506    946090.83485
Permanent Ineff=
       F       F       F
Bank Sta=4979.3,5021.06
XS Rating Curve= 0
Exp/Cntr=.5,.3

Type RM Length L Ch R = 1 ,25073.7 ,55.1,55,53.8
BEGIN DESCRIPTION:
CAMPBELL RD - XS 3
Levees are not FEMA regulated levees, only RAS levees to prevent spilling into E115-09-00.
END DESCRIPTION:
XS GIS Cut Line= 4
      3069628.54      13868371.4      3069661.76     13865856.27
      3069746.99     13862793.08      3069393.95     13861672.56
#Sta/Elev= 30
  2704.8   88.22  2710.5   88.21  4354.8   87.42  4764.8   90.32  4968.2   88.01
    4974   87.93  4984.1   80.05  4995.6   79.45  4996.8   75.52  5000.4   75.49
    5003   75.54 5003.11   79.48  5021.6   87.65    5033   88.12  5620.2   88.82
  5959.7   86.96  6229.8   87.13  6477.1   87.09  7009.5   87.03  7227.3   86.18
  7240.2   85.52  7270.2   77.22  7280.2   76.32  7301.4   81.64  7330.2   86.42
  7460.5   88.02  8524.5   84.16  8634.5   86.62  9124.5   85.87  9459.4   88.58
#Mann= 13 ,-1 , 0
  2704.8     .08       0  2710.5     .08       0  4968.2     .04       0
    4974    .015       0  5021.6     .04       0    5033     .08       0
  5959.7     .05       0  6229.8     .08       0  6477.1     .05       0
  7009.5     .08       0  7227.3     .04       0  7301.4     .08       0
  7460.5     .99       0
#XS Ineff= 3 ,-1
    2704    4964   88.66  5031.6    5915   88.33    5915  9459.4      90
Permanent Ineff=
       F       F       F
Bank Sta=4974,5021.6
XS Rating Curve= 0
Exp/Cntr=.5,.3

Type RM Length L Ch R = 3 ,25046.2 ,,,
BEGIN DESCRIPTION:
CAMPBELL ROAD
Structure ID: E115-00-00-16
END DESCRIPTION:
Bridge Culvert--1,0,-1,-1, 0
Deck Dist Width WeirC Skew NumUp NumDn MinLoCord MaxHiCord MaxSubmerge Is_Ogee
10,35,2.6,0, 93, 93, 87.6, , .95, 0, ,,,
  2704.8  2710.5  2884.8  2890.5  2904.8  2974.8  3064.8  3074.8  3104.8  3124.8
  3444.8  3534.8  3634.8  3820.5  3890.5  3920.5  3950.5  3990.5  4000.5  4050.5
  4070.5  4090.5  4120.5  4134.8  4190.5  4250.5  4320.5  4344.8  4354.8  4370.5
  4374.8  4400.5  4404.8  4420.5  4434.8  4440.5  4484.8  4490.5  4520.5  4534.8
  4540.5  4554.8  4574.8  4630.5  4654.8  4684.8  4734.8  4750.5  4760.5  4764.8
  4780.5  4804.8  4817.5  4817.6  4868.7  4869.7  4918.7    4947 4967.79  4967.9
 4968.01  4968.2    4974  4980.3  4980.5  4980.6 4980.71  4980.8  4984.1  4993.3
  4995.6  4996.6  4996.8  5000.4    5003 5003.11  5003.7  5006.1  5018.4 5018.49
  5018.6  5018.7  5021.6  5025.7 5027.69  5027.8 5027.91  5031.3    5033  5071.1
  5093.9  5120.9  5158.3
    88.2    88.2   87.81   87.75   87.61   87.81   87.81   88.11   88.01   87.81
   87.81   87.78   87.91    87.9   87.81    87.8   87.78   87.77   87.76   87.74
   87.74   87.73   87.72   87.71   87.68   87.65   87.62   87.61   87.41   87.72
   87.81    88.6   88.61    88.5   88.21   88.14   88.41   88.32   87.84   87.77
    87.8   88.01   88.61   88.61   88.61   88.81   88.91   89.64   90.11   90.31
   90.11   89.81   88.53   88.53   88.96   88.96      89   89.02   89.26   93.46
   93.46   93.46   93.53    93.6   93.63   93.63   93.63   93.63   93.63   93.62
   93.62   93.62   93.62   93.62   93.62   93.62   93.62   93.62   93.61   93.61
   93.61   93.61   93.51   93.37    93.3    93.3    89.1   88.98   88.97   88.78
   88.67   88.73   88.81
                                                                                
                                                                                
                                                                                
                                                                                
                                                                                
                                                                                
                                           82.76   82.67   87.93   87.93   87.92
   87.92   87.92   87.92   87.92   87.92   87.92   87.92   87.92   87.91   87.91
   86.26
                        
  2704.8  2710.5  2884.8  2890.5  2904.8  2974.8  3064.8  3074.8  3104.8  3124.8
  3444.8  3534.8  3634.8  3820.5  3890.5  3920.5  3950.5  3990.5  4000.5  4050.5
  4070.5  4090.5  4120.5  4134.8  4190.5  4250.5  4320.5  4344.8  4354.8  4370.5
  4374.8  4400.5  4404.8  4420.5  4434.8  4440.5  4484.8  4490.5  4520.5  4534.8
  4540.5  4554.8  4574.8  4630.5  4654.8  4684.8  4734.8  4750.5  4760.5  4764.8
  4780.5  4804.8  4817.5  4817.6  4868.7  4869.7  4918.7    4947 4967.79  4967.9
 4968.01  4968.2    4974  4980.3  4980.5  4980.6 4980.71  4980.8  4984.1  4993.3
  4995.6  4996.6  4996.8  5000.4    5003 5003.11  5003.7  5006.1  5018.4 5018.49
  5018.6  5018.7  5021.6  5025.7 5027.69  5027.8 5027.91  5031.3    5033  5071.1
  5093.9  5120.9  5158.3
    88.2    88.2   87.81   87.75   87.61   87.81   87.81   88.11   88.01   87.81
   87.81   87.78   87.91    87.9   87.81    87.8   87.78   87.77   87.76   87.74
   87.74   87.73   87.72   87.71   87.68   87.65   87.62   87.61   87.41   87.72
   87.81    88.6   88.61    88.5   88.21   88.14   88.41   88.32   87.84   87.77
    87.8   88.01   88.61   88.61   88.61   88.81   88.91   89.64   90.11   90.31
   90.11   89.81   88.53   88.53   88.96   88.96      89   89.02   89.26   93.46
   93.46   93.46   93.53    93.6   93.63   93.63   93.63   93.63   93.63   93.62
   93.62   93.62   93.62   93.62   93.62   93.62   93.62   93.62   93.61   93.61
   93.61   93.61   93.51   93.37    93.3    93.3    89.1   88.98   88.97   88.78
   88.67   88.73   88.81
                                                                                
                                                                                
                                                                                
                                                                                
                                                                                
                                                                                
                                           82.76   82.67   87.93   87.93   87.92
   87.92   87.92   87.92   87.92   87.92   87.92   87.92   87.92   87.91   87.91
   86.26
                        
Pier Skew, UpSta & Num, DnSta & Num=  ,4993.3, 2 ,4993.3, 2 , 0 , 0 , 0 ,,
     1.5     1.5
   78.48   88.92
     1.5     1.5
   78.45   88.89
Pier Skew, UpSta & Num, DnSta & Num=  ,5006.1, 2 ,5006.1, 2 , 0 , 0 , 0 ,,
     1.5     1.5
   79.21   88.92
     1.5     1.5
   79.18   88.89
BR Coef= 1 , 1 , 1 ,1.05, 0 ,,,.8,0,1.2,0,
WSPro=,,,, 1 ,,,, 0 ,,,, 0 ,,,,-1 ,-1 ,-1 , 0 , 0 , 0 , 0 , 0
BR U #Sta/Elev= 30
  2704.8   88.22  2710.5   88.21  4354.8   87.42  4764.8   90.32  4968.2   88.01
    4974   87.93  4984.1   80.05  4995.6   79.45  4996.8   75.52  5000.4   75.49
    5003   75.54 5003.11   79.48  5021.6   87.65    5033   88.12  5620.2   88.82
  5959.7   86.96  6229.8   87.13  6477.1   87.09  7009.5   87.03  7227.3   86.18
  7240.2   85.52  7270.2   77.22  7280.2   76.32  7301.4   81.64  7330.2   86.42
  7460.5   88.02  8524.5   84.16  8634.5   86.62  9124.5   85.87  9459.4   88.58
BR U #Mann= 13
  2704.8     .08  2710.5     .08  4968.2     .04    4974    .015  5021.6     .04
    5033     .08  5959.7     .05  6229.8     .08  6477.1     .05  7009.5     .08
  7227.3     .04  7301.4     .08  7460.5     .99
BR D #Sta/Elev= 30
  2704.8   88.14  2710.5   88.13  4354.8   87.34  4764.8   90.24  4968.2   87.93
    4974   87.85  4984.1   79.97  4995.6   79.37  4996.8   75.44  5000.4   75.41
    5003   75.46 5003.11    79.4  5021.6   87.57    5033   88.04  5620.2   88.74
  5959.7   86.88  6229.8   87.05  6477.1   87.01  7009.5   86.95  7227.3    86.1
  7240.2   85.44  7270.2   77.14  7280.2   76.24  7301.4   81.56  7330.2   86.34
  7460.5   87.94  8524.5   84.08  8634.5   86.54  9124.5   85.79  9459.4    88.5
BR D #Mann= 13
  2704.8     .08  2710.5     .08  4968.2     .04    4974    .015  5021.6     .04
    5033     .08  5959.7     .05  6229.8     .08  6477.1     .05  7009.5     .08
  7227.3     .04  7301.4     .08  7460.5     .99
BC Design=,, 0 ,, 0 ,,,,,,
BC HTab HWMax=90.32

Type RM Length L Ch R = 1 ,25018.7 ,101.2,105.9,98.8
BEGIN DESCRIPTION:
CAMPBELL RD - XS 2
Levees are not FEMA regulated levees, only RAS levees to prevent spilling into E115-09-00.
END DESCRIPTION:
XS GIS Cut Line= 4
      3069682.33       13868372.      3069715.55      13865857.3
        3069801.     13862786.07      3069445.43     13861657.54
#Sta/Elev= 30
  2704.8   88.14  2710.5   88.13  4354.8   87.34  4764.8   90.24  4968.2   87.93
    4974   87.85  4984.1   79.97  4995.6   79.37  4996.8   75.44  5000.4   75.41
    5003   75.46 5003.11    79.4  5021.6   87.57    5033   88.04  5620.2   88.74
  5959.7   86.88  6229.8   87.05  6477.1   87.01  7009.5   86.95  7227.3    86.1
  7240.2   85.44  7270.2   77.14  7280.2   76.24  7301.4   81.56  7330.2   86.34
  7460.5   87.94  8524.5   84.08  8634.5   86.54  9124.5   85.79  9459.4    88.5
#Mann= 13 ,-1 , 0
  2704.8     .08       0  2710.5     .08       0  4968.2     .04       0
    4974    .015       0  5021.6     .04       0    5033     .08       0
  5959.7     .05       0  6229.8     .08       0  6477.1     .05       0
  7009.5     .08       0  7227.3     .04       0  7301.4     .08       0
  7460.5     .99       0
#XS Ineff= 2 , 0
       0 4967.33   88.33 5028.27       0   88.33
Permanent Ineff=
       F       F
Bank Sta=4974,5021.6
XS Rating Curve= 0
Exp/Cntr=.5,.3

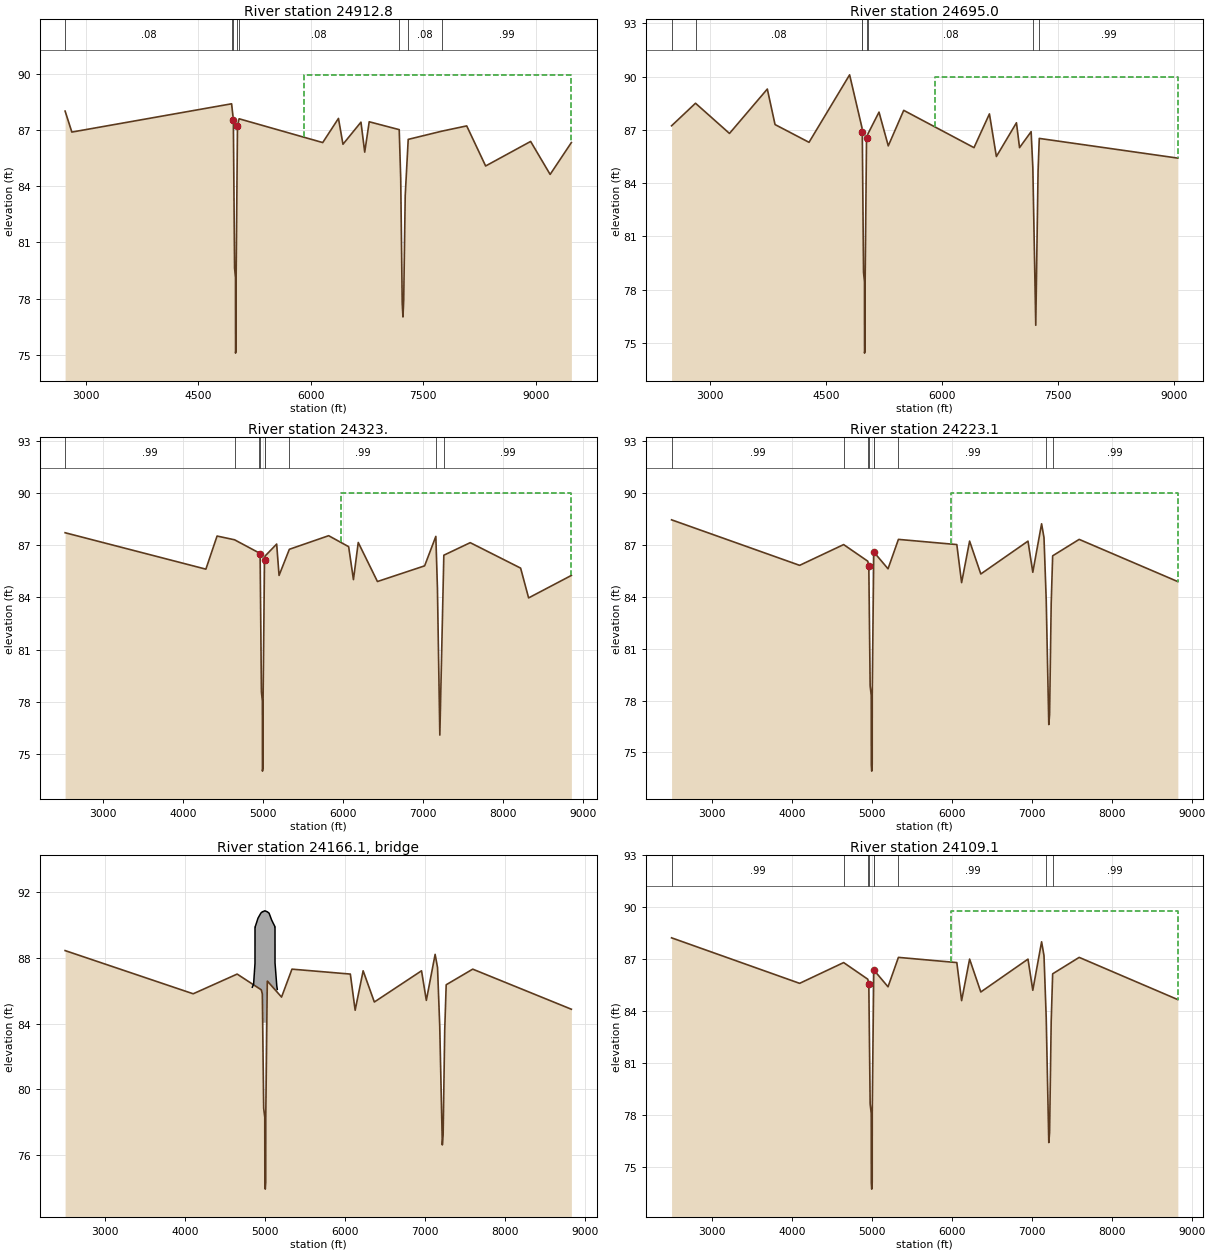
Type RM Length L Ch R = 1 ,24912.8 ,220.5,217.8,216.1
BEGIN DESCRIPTION:
CAMPBELL RD - XS 1
Interplotated channel, LIDAR overbanks
Levees are not FEMA regulated levees, only RAS levees to prevent spilling into E115-09-00.
END DESCRIPTION:
XS GIS Cut Line= 4
 3069781.554096613868336.4517437       3069814.5     13865841.68
      3069899.96     13862770.44      3069544.39     13861641.91
#Sta/Elev= 30
  2723.8   88.01  2813.8   86.89  4943.8    88.4  4967.2   87.56  4983.6   79.63
  4995.6   79.13  4996.6   75.09  5003.7    75.3  5004.3   79.15  5022.2   87.21
  5043.8    87.6  6158.8   86.33  6368.8   87.62  6428.8   86.24  6668.8   87.42
  6718.8   85.82  6778.8   87.44  7178.8   87.02  7198.8   84.42  7218.8   77.77
  7228.8   77.02  7238.8   77.93  7258.8   83.49  7298.8    86.5  7748.8   86.94
  8078.8   87.22  8331.2   85.08  8931.2   86.39  9191.2   84.63  9474.4   86.33
#Mann= 8 ,-1 , 0
  2723.8     .08       0  4943.8     .04       0  4967.2    .015       0
  5022.2     .04       0  5043.8     .08       0  7178.8     .04       0
  7298.8     .08       0  7748.8     .99       0
#XS Ineff= 2 , 0
       0                5913.691       089.94617
Permanent Ineff=
       F       F
Bank Sta=4967.2,5022.2
XS Rating Curve= 0
Exp/Cntr=.3,.1

Type RM Length L Ch R = 1 ,24695.0 ,373.5,372,370.9
BEGIN DESCRIPTION:
Cross Section x19
Located At: US BLALOCK
Levees are not FEMA regulated levees, only RAS levees to prevent spilling into E115-09-00.
END DESCRIPTION:
XS GIS Cut Line= 4
      3070140.52      13868549.7      3070022.45     13866247.09
       3070029.5     13865966.52      3069976.82      13861996.8
#Sta/Elev= 30
  2497.5   87.23  2807.5    88.5  3247.5    86.8  3737.5    89.3  3837.5    87.3
  4277.5    86.3  4803.2    90.1  4963.1   87.13  4967.2    86.9  4983.6   78.97
  4995.6   78.47  4996.6   74.43  5003.7   74.64  5004.3   78.49  5022.2   86.55
  5043.2    86.8  5183.9      88  5303.9    86.1  5503.9    88.1  6413.9      86
  6613.9    87.9  6703.9    85.5  6963.9    87.4  7003.9      86  7153.9    86.9
  7176.1   84.88  7213.9      76  7243.9    84.7  7259.4   86.52  9053.9   85.41
#Mann= 8 ,-1 , 0
  2497.5     .08       0  2807.5     .08       0  4963.1     .04       0
  4967.2    .015       0  5022.2     .04       0  5043.2     .08       0
  7176.1     .04       0  7259.4     .99       0
#XS Ineff= 2 , 0
       0                    5911       0      90
Permanent Ineff=
       F       F
Bank Sta=4967.2,5022.2
XS Rating Curve= 0
Exp/Cntr=.3,.1

Type RM Length L Ch R = 1 ,24323.  ,98.7,99.9,98.2
BEGIN DESCRIPTION:
BLALOCK - XS 4
Interplotated channel, LIDAR overbanks
Levees are not FEMA regulated levees, only RAS levees to prevent spilling into E115-09-00.
END DESCRIPTION:
XS GIS Cut Line= 4
      3070399.82     13868538.56      3070393.93     13866299.38
      3070400.01     13865973.61      3070168.99     13862216.17
#Sta/Elev= 30
  2529.2   87.71  4289.2   85.62  4429.2   87.52    4648  87.305    4950  86.564
  4967.2    86.5  4983.6   78.57  4995.6   78.07  4996.6   74.03  5003.7   74.24
  5004.3   78.09  5022.2   86.15    5030  86.376  5174.2   87.06  5204.2   85.26
    5333   86.76  5824.2   87.54  6074.2   86.91  6134.2   85.02  6194.2   87.15
  6434.2   84.91  7024.2   85.81  7164.2    87.5  7184.2   84.53  7214.2    76.1
  7264.2   86.42  7594.2   87.14  8224.2   85.68  8324.2   83.97  8858.8   85.26
#Mann= 9 ,-1 , 0
  2529.2     .99       0    4648     .08       0    4950     .04       0
  4967.2    .015       0  5022.2     .04       0    5030     .08       0
    5333     .99       0  7164.2     .04       0  7264.2     .99       0
#XS Ineff= 2 , 0
       0                5975.641       0      90
Permanent Ineff=
       F       F
Bank Sta=4967.2,5022.2
XS Rating Curve= 0
Exp/Cntr=.5,.3

Type RM Length L Ch R = 1 ,24223.1 ,113.9,114,113.3
BEGIN DESCRIPTION:
BLALOCK - XS 3
Levees are not FEMA regulated levees, only RAS levees to prevent spilling into E115-09-00.
END DESCRIPTION:
XS GIS Cut Line= 4
      3070497.91      13868542.9      3070492.02     13866303.72
       3070498.1     13865977.95      3070267.08     13862220.51
#Sta/Elev= 30
  2497.5   88.44  4098.7   85.81  4648.7   87.01  4950.3   86.05  4963.4    85.8
  4980.3   78.84  4993.8    78.3  4994.9   74.28    5000   73.92  5005.9   74.32
  5006.5   78.36  5025.3   86.56  5026.7   86.58  5203.7   85.61  5333.7   87.31
  6063.7   87.01  6123.7   84.81  6223.7   87.21  6363.7   85.31  6953.7   87.21
  7013.7   85.41  7123.7   88.21  7153.7   87.41  7181.4   83.83  7213.7   76.61
  7223.7   77.21  7243.7   83.61    7262   86.36  7593.7   87.31  8827.1   84.87
#Mann= 9 ,-1 , 0
  2497.5     .99       0  4648.7     .08       0  4950.3     .04       0
  4963.4    .015       0  5025.3     .04       0  5026.7     .08       0
  5333.7     .99       0  7181.4     .04       0    7262     .99       0
#XS Ineff= 2 , 0
       0  4953.4    85.9    5993       0      90
Permanent Ineff=
       F       F
Bank Sta=4963.4,5025.3
XS Rating Curve= 0
Exp/Cntr=.5,.3

Type RM Length L Ch R = 3 ,24166.1 ,,,
BEGIN DESCRIPTION:
BLALOCK
Structure ID: E115-00-00-15
END DESCRIPTION:
Bridge Culvert--1,0,-1,-1, 0
Deck Dist Width WeirC Skew NumUp NumDn MinLoCord MaxHiCord MaxSubmerge Is_Ogee
10,94,2.6,0, 49, 49, 85.7, , .95, 0, ,,,
  4837.9  4854.2  4857.9    4863 4871.49  4871.6 4871.71  4872.1  4893.1  4908.8
  4938.9  4942.3  4950.3  4956.5 4956.61  4963.4 4968.91    4969  4980.2  4980.3
  4993.8  4994.9  4995.1  4996.2  4996.5    5000  5003.8    5005  5005.9  5006.5
  5006.7  5006.8 5019.89    5020  5025.3  5026.3 5026.41  5026.7  5033.4  5047.4
  5063.1  5079.6  5092.1  5093.7 5121.79  5121.9 5122.01  5143.7  5150.2
   86.21    86.4   86.67   87.04   87.66   89.86   89.86   89.86   90.17   90.41
   90.67    90.7   90.75   90.78   90.78   90.79    90.8   90.81   90.83   90.83
   90.86   90.86   90.86   90.86   90.86   90.85   90.84   90.84   90.84   90.84
   90.84   90.84   90.81   90.81    90.8    90.8    90.8    90.8   90.77   90.72
   90.52    90.3   90.18   90.16   89.89   89.89   87.69   86.31   86.08
                                                                                
                                                           84.01   84.03   84.03
   84.06   84.06   84.06   84.06   84.06   84.05   84.04   84.04   84.04   84.04
   84.04   84.04   84.15
                                                                        
  4837.9  4854.2  4857.9    4863 4871.49  4871.6 4871.71  4872.1  4893.1  4908.8
  4938.9  4942.3  4950.3  4956.5 4956.61  4963.4 4968.91    4969  4980.2  4980.3
  4993.8  4994.9  4995.1  4996.2  4996.5    5000  5003.8    5005  5005.9  5006.5
  5006.7  5006.8 5019.89    5020  5025.3  5026.3 5026.41  5026.7  5033.4  5047.4
  5063.1  5079.6  5092.1  5093.7 5121.79  5121.9 5122.01  5143.7  5150.2
   86.21    86.4   86.67   87.04   87.66   89.86   89.86   89.86   90.17   90.41
   90.67    90.7   90.75   90.78   90.78   90.79    90.8   90.81   90.83   90.83
   90.86   90.86   90.86   90.86   90.86   90.85   90.84   90.84   90.84   90.84
   90.84   90.84   90.81   90.81    90.8    90.8    90.8    90.8   90.77   90.72
   90.52    90.3   90.18   90.16   89.89   89.89   87.69   86.31   86.08
                                                                                
                                                           84.01   84.03   84.03
   84.06   84.06   84.06   84.06   84.06   84.05   84.04   84.04   84.04   84.04
   84.04   84.04   84.15
                                                                        
BR Coef= 1 , 1 , 0 ,1.25, 0 ,,,.8,0,2,0,
WSPro=,,,, 1 ,,,, 0 ,,,, 0 ,,,,-1 ,-1 ,-1 , 0 , 0 , 0 , 0 , 0
BR U #Sta/Elev= 30
  2497.5   88.44  4098.7   85.81  4648.7   87.01  4950.3   86.05  4963.4    85.8
  4980.3   78.84  4993.8    78.3  4994.9   74.28    5000   73.92  5005.9   74.32
  5006.5   78.36  5025.3   86.56  5026.7   86.58  5203.7   85.61  5333.7   87.31
  6063.7   87.01  6123.7   84.81  6223.7   87.21  6363.7   85.31  6953.7   87.21
  7013.7   85.41  7123.7   88.21  7153.7   87.41  7181.4   83.83  7213.7   76.61
  7223.7   77.21  7243.7   83.61    7262   86.36  7593.7   87.31  8827.1   84.87
BR U #Mann= 9
  2497.5     .99  4648.7     .08  4950.3     .04  4963.4    .015  5025.3     .04
  5026.7     .08  5333.7     .99  7181.4     .04    7262     .99
BR D #Sta/Elev= 30
  2497.5   88.23  4098.7    85.6  4648.7    86.8  4950.3   85.84  4963.4   85.59
  4980.3   78.63  4993.8   78.09  4994.9   74.07    5000   73.71  5005.9   74.11
  5006.5   78.15  5025.3   86.35  5026.7   86.37  5203.7    85.4  5333.7    87.1
  6063.7    86.8  6123.7    84.6  6223.7      87  6363.7    85.1  6953.7      87
  7013.7    85.2  7123.7      88  7153.7    87.2  7181.4   83.62  7213.7    76.4
  7223.7      77  7243.7    83.4    7262   86.15  7593.7    87.1  8827.1   84.66
BR D #Mann= 9
  2497.5     .99  4648.7     .08  4950.3     .04  4963.4    .015  5025.3     .04
  5026.7     .08  5333.7     .99  7181.4     .04    7262     .99
BC Design=,, 0 ,, 0 ,,,,,,
BC HTab HWMax=88.71

Type RM Length L Ch R = 1 ,24109.1 ,101.4,98.2,100.8
BEGIN DESCRIPTION:
BLALOCK - XS 2
Levees are not FEMA regulated levees, only RAS levees to prevent spilling into E115-09-00.
END DESCRIPTION:
XS GIS Cut Line= 4
      3070611.08      13868549.6       3070605.2     13866310.95
       3070611.3     13865983.71      3070380.16     13862224.27
#Sta/Elev= 30
  2497.5   88.23  4098.7    85.6  4648.7    86.8  4950.3   85.84  4963.4   85.59
  4980.3   78.63  4993.8   78.09  4994.9   74.07    5000   73.71  5005.9   74.11
  5006.5   78.15  5025.3   86.35  5026.7   86.37  5203.7    85.4  5333.7    87.1
  6063.7    86.8  6123.7    84.6  6223.7      87  6363.7    85.1  6953.7      87
  7013.7    85.2  7123.7      88  7153.7    87.2  7181.4   83.62  7213.7    76.4
  7223.7      77  7243.7    83.4    7262   86.15  7593.7    87.1  8827.1   84.66
#Mann= 9 ,-1 , 0
  2497.5     .99       0  4648.7     .08       0  4950.3     .04       0
  4963.4    .015       0  5025.3     .04       0  5026.7     .08       0
  5333.7     .99       0  7181.4     .04       0    7262     .99       0
#XS Ineff= 3 ,-1
  2497.5 4956.73   85.69 5031.97    5993   85.69    5993  8827.1   89.79
Permanent Ineff=
       F       F       F
Bank Sta=4963.4,5025.3
XS Rating Curve= 0
Exp/Cntr=.5,.3

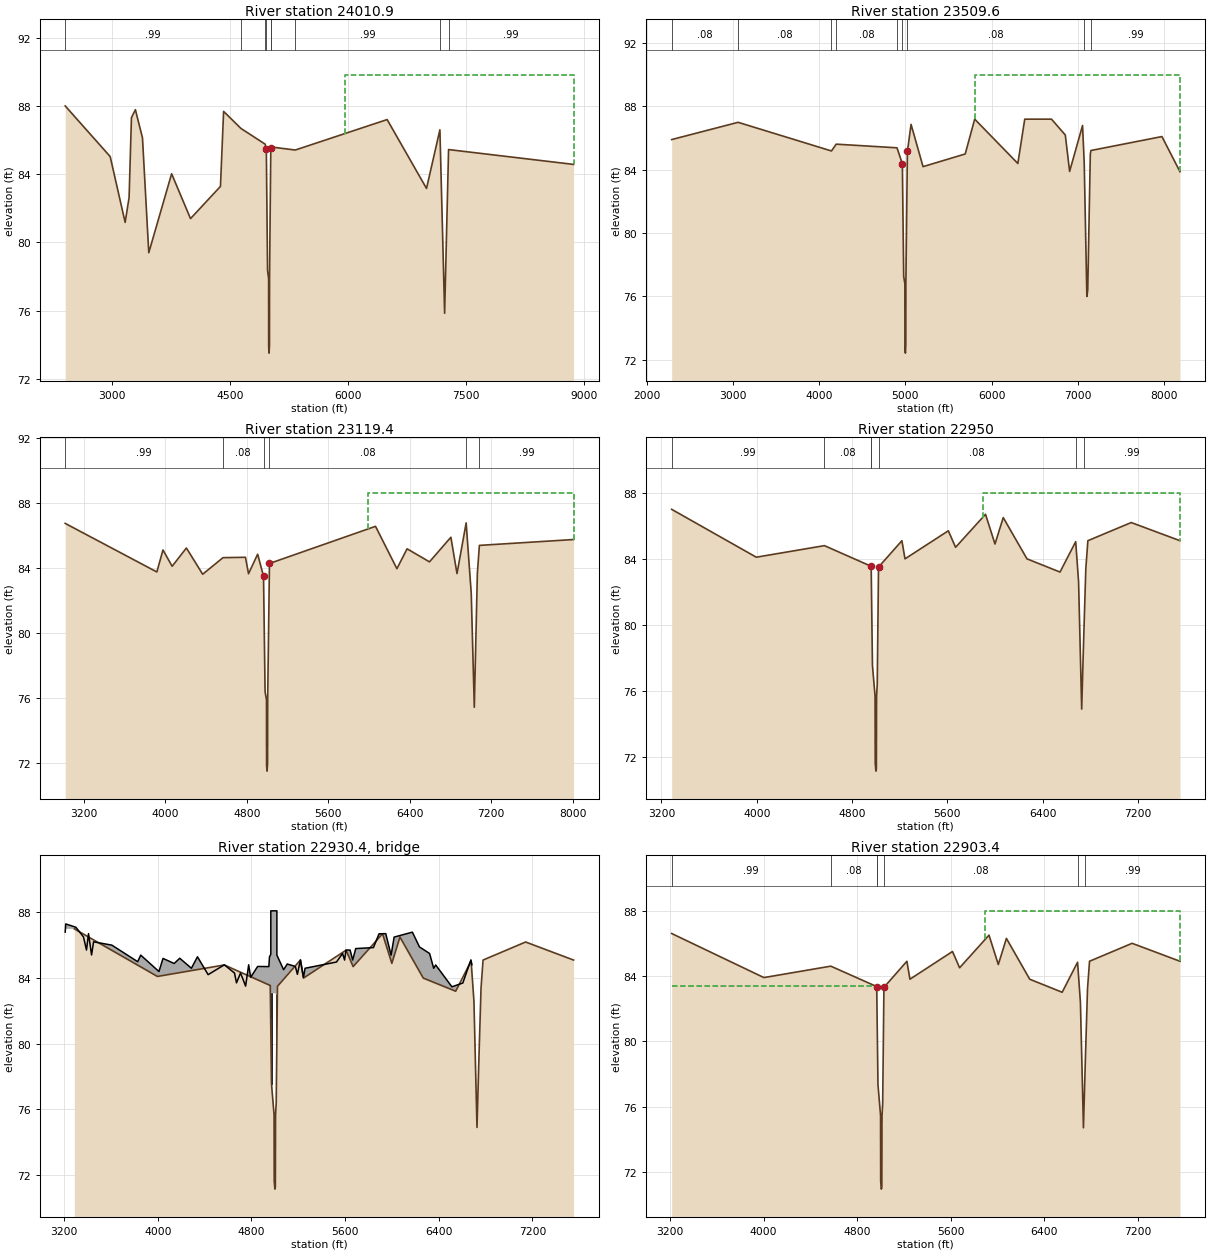
Type RM Length L Ch R = 1 ,24010.9 ,552.4,501.3,463.5
BEGIN DESCRIPTION:
BLALOCK - XS 1
Interplotated channel, LIDAR overbanks
Levees are not FEMA regulated levees, only RAS levees to prevent spilling into E115-09-00.
END DESCRIPTION:
XS GIS Cut Line= 5
 3070712.098357413868678.4095812      3070711.78     13868557.41
      3070705.89     13866318.77        3070712.     13865991.52
      3070480.86     13862232.08
#Sta/Elev= 30
  2411.6      88  2982.6   85.03  3172.6   81.17  3222.6   82.63  3252.6   87.31
  3302.6   87.78  3392.6   86.13  3472.6   79.39  3762.6   84.02  4002.6   81.39
  4382.6   83.28  4422.6   87.68  4642.6   86.68    4950  85.758    4965   85.46
  4980.4   78.36  4994.1   77.87  4994.9   73.86  5000.1    73.5    5005   74.02
  5005.8   77.91 5021.87   85.55    5030  85.589    5333  85.414  6498.6    87.2
  6998.6   83.16  7168.6    86.6  7228.6   75.84  7278.6   85.44  8865.1   84.57
#Mann= 9 ,-1 , 0
  2411.6     .99       0  4642.6     .08       0    4950     .04       0
    4965    .015       0 5021.87     .04       0    5030     .08       0
    5333     .99       0  7168.6     .04       0  7278.6     .99       0
#XS Ineff= 2 , 0
       0                5961.877       0 89.8244
Permanent Ineff=
       F       F
Bank Sta=4965,5021.87
XS Rating Curve= 0
Exp/Cntr=.3,.1

Type RM Length L Ch R = 1 ,23509.6 ,391.8,390.2,385.1
BEGIN DESCRIPTION:
Cross Section x18
Located At: DS BLALOCK
Levees are not FEMA regulated levees, only RAS levees to prevent spilling into E115-09-00.
END DESCRIPTION:
XS GIS Cut Line= 4
      3071166.14      13868568.7      3071251.19     13866067.07
      3070821.04     13865335.33      3070636.85     13862802.65
#Sta/Elev= 30
  2291.4   85.91  3061.4      87  4143.4   85.19  4197.9   85.62  4903.1   85.39
    4965   84.38  4980.4   77.28  4994.1   76.79  4994.9   72.78  5000.1   72.42
    5005   72.94  5005.8   76.83  5023.4   85.16    5066   86.87  5204.6    84.2
  5693.4      85  5803.4    87.2  6303.4    84.4  6383.4    87.2  6693.4    87.2
  6853.4    86.2  6903.4    83.9  7053.4    86.8  7072.6   84.44  7103.4      76
  7113.4    76.4  7143.4      85  7150.8   85.22  7973.4    86.1  8182.7   83.88
#Mann= 9 ,-1 , 0
  2291.4     .08       0  3061.4     .08       0  4143.4     .08       0
  4197.9     .08       0  4903.1     .08       0    4965    .015       0
  5023.4     .08       0  7072.6     .04       0  7150.8     .99       0
#XS Ineff= 2 , 0
       0                    5803       0      90
Permanent Ineff=
       F       F
Bank Sta=4965,5023.4
XS Rating Curve= 0
Exp/Cntr=.3,.1

Type RM Length L Ch R = 1 ,23119.4 ,125.5,169.4,219.7
BEGIN DESCRIPTION:
MORNINGVIEW - XS 4
Interplotated channel, LIDAR overbanks
Levees are not FEMA regulated levees, only RAS levees to prevent spilling into E115-09-00.
END DESCRIPTION:
XS GIS Cut Line= 6
       3071697.2     13867644.81      3071529.43     13865763.12
      3071435.21     13865622.41      3071435.01     13865372.86
      3070920.29     13864843.52      3070673.27     13862914.89
#Sta/Elev= 30
  3017.7   86.73  3917.7   83.75  3977.7    85.1  4067.7    84.1  4207.7   85.22
  4367.7   83.61    4567  84.628  4787.7   84.65  4817.7   83.64  4907.4   84.84
    4965   83.49  4980.4   76.39  4994.1    75.9  4994.9   71.89  5000.1   71.53
    5005   72.05  5005.8   75.94  5023.4   84.27  6064.7   86.55  6274.7   83.95
  6374.7   85.17  6594.7   84.37  6804.7   85.88  6864.7   83.65  6954.7   86.76
  7004.7   82.43  7034.7   75.45  7064.7   83.67  7084.7   85.38    8009   85.74
#Mann= 6 ,-1 , 0
  3017.7     .99       0    4567     .08       0    4965    .015       0
  5023.4     .08       0  6954.7     .04       0  7084.7     .99       0
#XS Ineff= 2 , 0
       0                    5990       088.60543
Permanent Ineff=
       F       F
Bank Sta=4965,5023.4
XS Rating Curve= 0
Exp/Cntr=.5,.3

Type RM Length L Ch R = 1 ,22950   ,52.2,46.6,54.6
BEGIN DESCRIPTION:
MORNINGVIEW - XS 3
Levees are not FEMA regulated levees, only RAS levees to prevent spilling into E115-09-00.
END DESCRIPTION:
XS GIS Cut Line= 5
        3071784.      13867593.5      3071613.46      13865773.5
      3071628.83      13865431.7      3071007.09      13864792.3
      3070760.07      13862863.6
#Sta/Elev= 30
 3286.22      87 3996.36    84.1 4567.94    84.8 4960.07   83.55 4960.42    83.5
 4970.99   77.55 4992.99   75.67  4994.2   71.62    5000   71.14  5003.9   71.29
 5005.46   75.64 5011.17   76.38 5021.91    83.5 5218.15    85.1 5244.13      84
 5607.86    85.7 5668.49    84.7 5919.63    86.7 5999.22    84.9  6068.5    86.5
 6267.69      84 6544.82    83.2 6676.45   85.04  6700.7    82.6 6726.68    74.9
 6743.14   79.08 6761.32    83.4 6778.64    85.1 7142.37    86.2 7551.66    85.1
#Mann= 7 ,-1 , 0
 3286.22     .99       0 4567.94     .08       0 4960.07     .08       0
 4960.42    .015       0 5021.91     .08       0 6676.45     .04       0
 6743.14     .99       0
#XS Ineff= 2 , 0
       0 4958.09    83.5    5895       0      88
Permanent Ineff=
       F       F
Bank Sta=4960.07,5021.91
XS Rating Curve= 0
Skew Angle= 30
Exp/Cntr=.5,.3

Type RM Length L Ch R = 3 ,22930.4 ,,,
BEGIN DESCRIPTION:
MORNINGVIEW DRIVE and Pipeline upstream
Structure ID: E115-00-00-14  includes pipeline piers.
END DESCRIPTION:
Bridge Culvert--1,0,-1,-1, 0
Deck Dist Width WeirC Skew NumUp NumDn MinLoCord MaxHiCord MaxSubmerge Is_Ogee
10,34,2.6,30, 60, 60, 84.5, , .95, 0, ,,,
 3208.28 3212.61 3299.22 3364.17 3390.15 3407.47 3433.45 3450.77 3606.66 3827.49
 3853.47 4009.36    4044 4139.26 4186.89 4286.49 4338.45 4429.38 4567.94 4654.55
 4671.87 4706.51 4749.81 4775.79 4793.11 4852.52 4948.22 4953.76 4965.02 4965.02
 5016.98 5016.98 5074.48 5105.57 5174.85 5192.17 5218.16 5244.14 5257.65 5526.11
 5578.08  5595.4 5607.87 5642.51 5664.68 5690.66 5841.69 5889.84 5947.26 5992.82
  6018.8 6174.68  6235.3 6321.91 6356.55 6373.87 6512.43 6605.44 6674.72 6683.38
    86.8    87.3    87.1   86.51   85.71   86.71   85.41   86.21   86.01      85
    85.4    84.4    85.2   84.89   85.21    84.6    85.3   84.21   84.81   84.31
   83.71   84.31   83.51   84.81   84.05   84.71    84.7    85.3   85.45    88.1
    88.1    85.4   84.51   84.86   84.71   84.23   85.11   84.05    84.6   84.98
    85.5    85.1   85.71   85.71    85.1    85.8   85.86    86.7   86.71    85.4
    86.5    86.8    85.9    85.5    84.6    84.8   83.47    83.7   85.11   84.81
                                                                                
                                                                                
                                                                           83.12
   83.04
                                                                                
                                                                                
 3215.29 3219.62 3306.23 3371.18 3397.16 3414.48 3440.46 3457.78 3613.67  3834.5
 3860.48 4016.37 4051.01 4146.27  4193.9  4293.5 4345.46 4436.39 4574.95 4661.56
 4678.88 4713.52 4756.82  4782.8 4800.12 4859.53 4955.23 4960.77 4972.03 4972.03
 5023.99 5023.99 5081.49 5112.58 5181.86 5199.18 5225.17 5251.15 5264.66 5533.12
 5585.09 5602.41 5614.88 5649.52 5671.69 5697.67  5848.7 5896.85 5954.27 5999.83
 6025.81 6181.69 6242.31 6328.92 6363.56 6380.88 6519.44 6612.45 6681.73 6690.39
    86.8    87.3    87.1   86.51   85.71   86.71   85.41   86.21   86.01      85
    85.4    84.4    85.2   84.89   85.21    84.6    85.3   84.21   84.81   84.31
   83.71   84.31   83.51   84.81   84.05   84.71    84.7    85.3   85.45    88.1
    88.1    85.4   84.51   84.86   84.71   84.23   85.11   84.05    84.6   84.98
    85.5    85.1   85.71   85.71    85.1    85.8   85.86    86.7   86.71    85.4
    86.5    86.8    85.9    85.5    84.6    84.8   83.47    83.7   85.11   84.81
                                                                                
                                                                                
                                                                           83.12
   83.04
                                                                                
                                                                                
Pier Skew, UpSta & Num, DnSta & Num=  ,4970.99, 2 ,4978, 2 , 0 , 0 , 0 ,,
       1       1
   76.48   84.85
       1       1
   76.48   84.85
Pier Skew, UpSta & Num, DnSta & Num=  ,5011.17, 2 ,5018.19, 2 , 0 , 0 , 0 ,,
       1       1
   75.32   84.85
       1       1
   75.32   84.85
BR Coef= 1 , 1 , 1 ,1.25, 0 ,,,.8,-1,2,0,
WSPro=,,,, 1 ,,,, 0 ,,,, 0 ,,,,-1 ,-1 ,-1 , 0 , 0 , 0 , 0 , 0
BC Design=,, 0 ,, 0 ,,,,,,
BC HTab HWMax=87

Type RM Length L Ch R = 1 ,22903.4 ,192.6,154.3,98.7
BEGIN DESCRIPTION:
MORNINGVIEW - XS 2
Levees are not FEMA regulated levees, only RAS levees to prevent spilling into E115-09-00.
END DESCRIPTION:
XS GIS Cut Line= 5
      3071827.78      13867590.8       3071657.7     13865775.58
      3071673.88     13865415.62       3071048.7     13864772.67
      3070802.86      13862853.3
#Sta/Elev= 30
  3215.3   86.61 4003.38   83.91 4574.96   84.61 4967.08   83.36 4967.44   83.31
    4978   77.36    5000   75.48 5001.21   71.43 5007.02   70.95 5010.91    71.1
 5012.47   75.45 5018.19   76.19 5028.93   83.31 5225.17   84.91 5251.15   83.81
 5614.88   85.51  5675.5   84.51 5926.65   86.51 6006.24   84.71 6075.52   86.31
  6274.7   83.81 6551.83   83.01 6683.47   84.85 6707.72   82.41  6733.7   74.71
 6750.15   78.89 6768.34   83.21 6785.66   84.91 7149.39   86.01 7558.67   84.91
#Mann= 7 ,-1 , 0
  3215.3     .99       0 4574.96     .08       0 4967.08     .08       0
 4967.44    .015       0 5028.93     .08       0 6683.47     .04       0
 6750.15     .99       0
#XS Ineff= 2 , 0
       04965.075    83.4    5895       0      88
Permanent Ineff=
       F       F
Bank Sta=4967.08,5028.93
XS Rating Curve= 0
Skew Angle= 30
Exp/Cntr=.5,.3

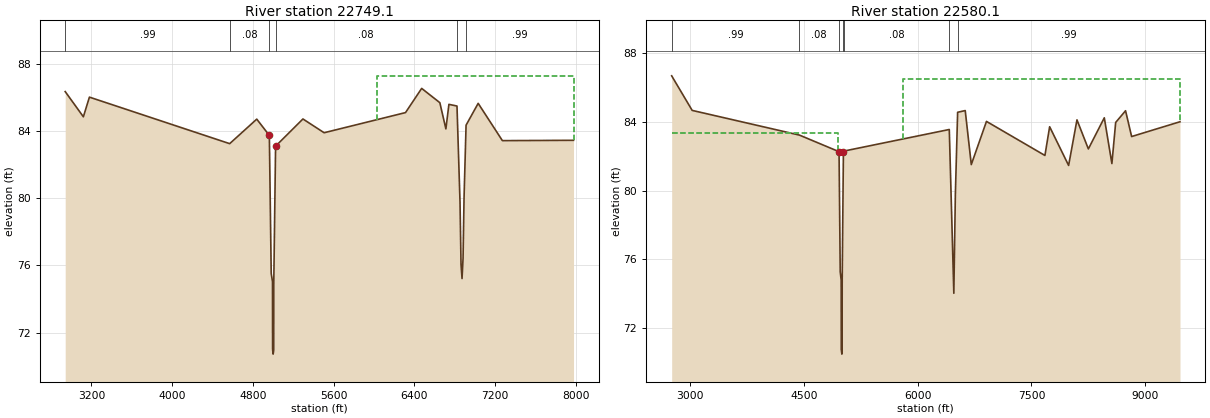
Type RM Length L Ch R = 1 ,22749.1 ,167.1,169,168.1
BEGIN DESCRIPTION:
MORNINGVIEW - XS 1
Interplotated channel, LIDAR overbanks
Levees are not FEMA regulated levees, only RAS levees to prevent spilling into E115-09-00.
END DESCRIPTION:
XS GIS Cut Line= 6
      3071986.29     13867529.49      3071810.15     13865729.65
      3071833.93     13865554.54      3071755.48     13865358.32
      3071130.29     13864715.38      3070884.46     13862796.06
#Sta/Elev= 30
  2939.5   86.35  3119.5   84.85  3179.5   86.02  4569.5   83.25  4837.9   84.71
 4962.59   83.74 4981.21   75.52 4993.85   75.04 4994.98   71.01    5000   70.72
 5005.98   70.95 5006.58   74.95 5024.51    83.1  5295.5   84.72  5505.5    83.9
  6312.3    85.1  6472.3   86.54  6652.3   85.69  6712.3   84.13  6742.3   85.59
  6822.3   85.49  6852.3   79.77  6862.3   76.06  6872.3   75.22  6882.3   76.41
  6892.3   80.04  6912.3   84.35  7032.3   85.65  7272.3   83.43  7977.3   83.45
#Mann= 6 ,-1 , 0
  2939.5     .99       0  4569.5     .08       0 4962.59    .015       0
 5024.51     .08       0  6822.3     .04       0  6912.3     .99       0
#XS Ineff= 2 , 0
       04961.11183.36443  6025.5       087.28861
Permanent Ineff=
       F       F
Bank Sta=4962.59,5024.51
XS Rating Curve= 0
Exp/Cntr=.3,.1

Type RM Length L Ch R = 1 ,22580.1 ,63.5,110.5,172.6
BEGIN DESCRIPTION:
GALWAY LANE - XS 4
Interplotated channel, LIDAR overbanks
Levees are not FEMA regulated levees, only RAS levees to prevent spilling into E115-09-00.
END DESCRIPTION:
XS GIS Cut Line= 6
      3072126.09     13867617.51      3071978.42     13865471.06
      3071888.09      13865325.7      3071877.56     13865142.52
      3071906.18     13862710.61      3071572.99     13860985.31
#Sta/Elev= 30
  2760.8   86.67  3030.8   84.66    4444  83.224 4965.67   82.26 4981.21   75.27
 4993.85   74.79 4994.98   70.76 5002.96   70.49 5005.68   70.67 5007.16   74.81
 5023.28   82.27    5030  82.295  6417.8   83.55  6477.8   74.03  6497.8   79.75
  6527.8   84.55  6627.8   84.65  6707.8   81.51  6907.8   84.02  7677.8   82.04
  7739.9   83.71  7989.9   81.46  8099.9   84.11  8249.9   82.42  8459.9   84.23
  8559.9   81.57  8609.9   83.96  8739.9   84.64  8819.9   83.14  9457.1      84
#Mann= 7 ,-1 , 0
  2760.8     .99       0    4444     .08       0 4965.67    .015       0
 5023.28     .04       0    5030     .08       0  6417.8     .04       0
  6527.8     .99       0
#XS Ineff= 2 , 0
       04956.76983.325485806.312       086.50945
Permanent Ineff=
       F       F
Bank Sta=4965.67,5023.28
XS Rating Curve= 0
Exp/Cntr=.5,.3