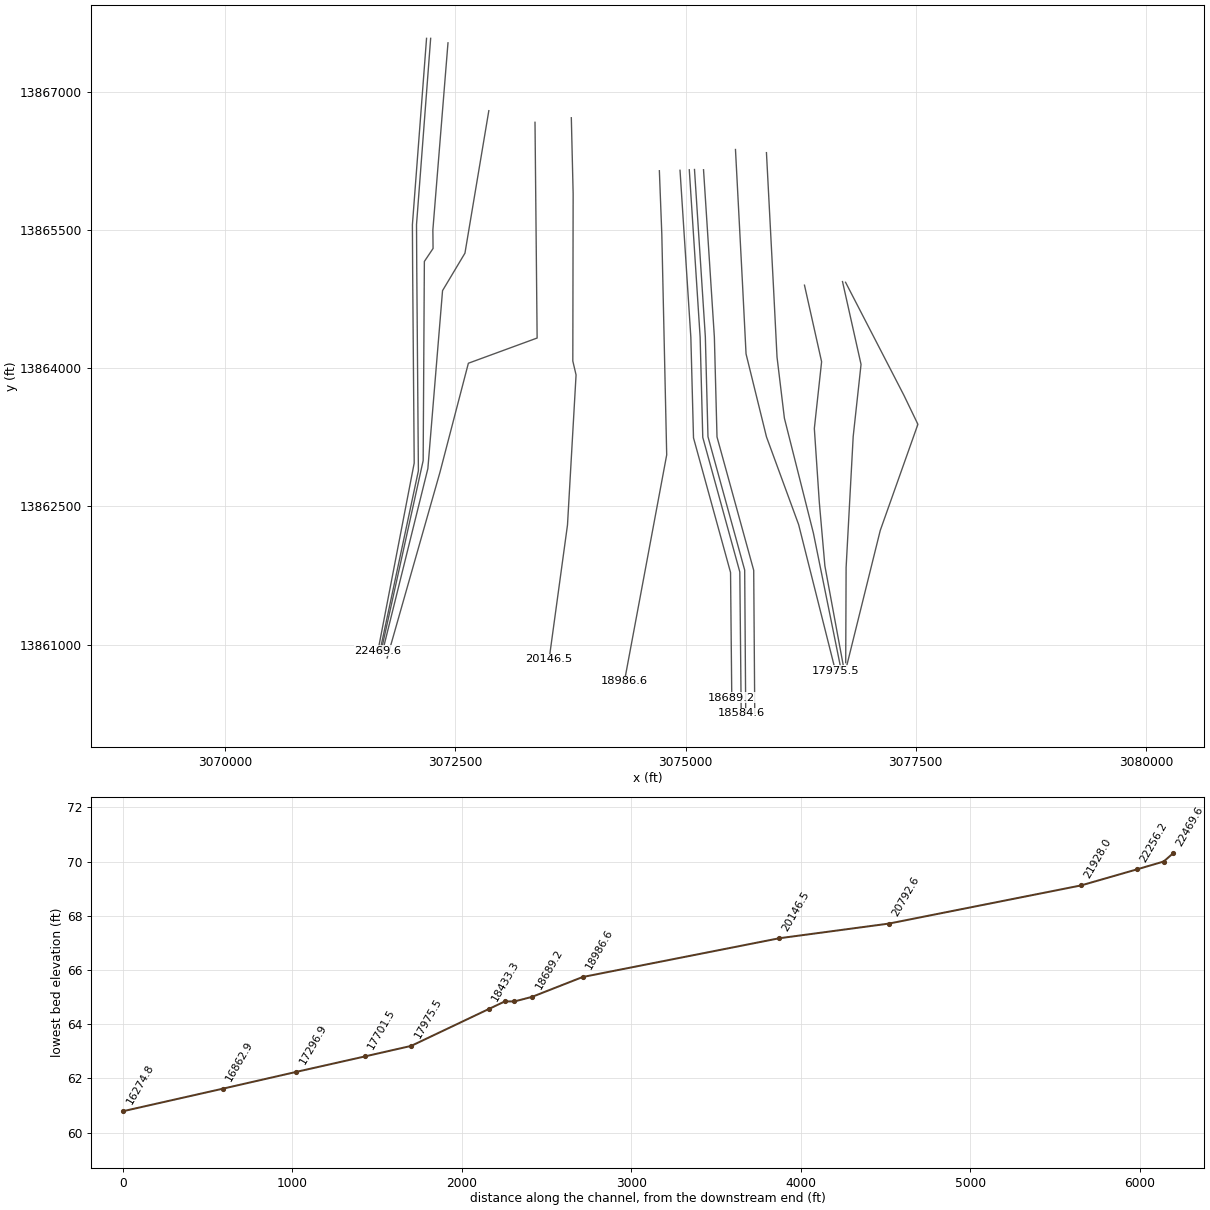
HEC-RAS study E115-00-00.prj: E115-00-00

--- E115-00-00.g01 (geometry) --- (continued)

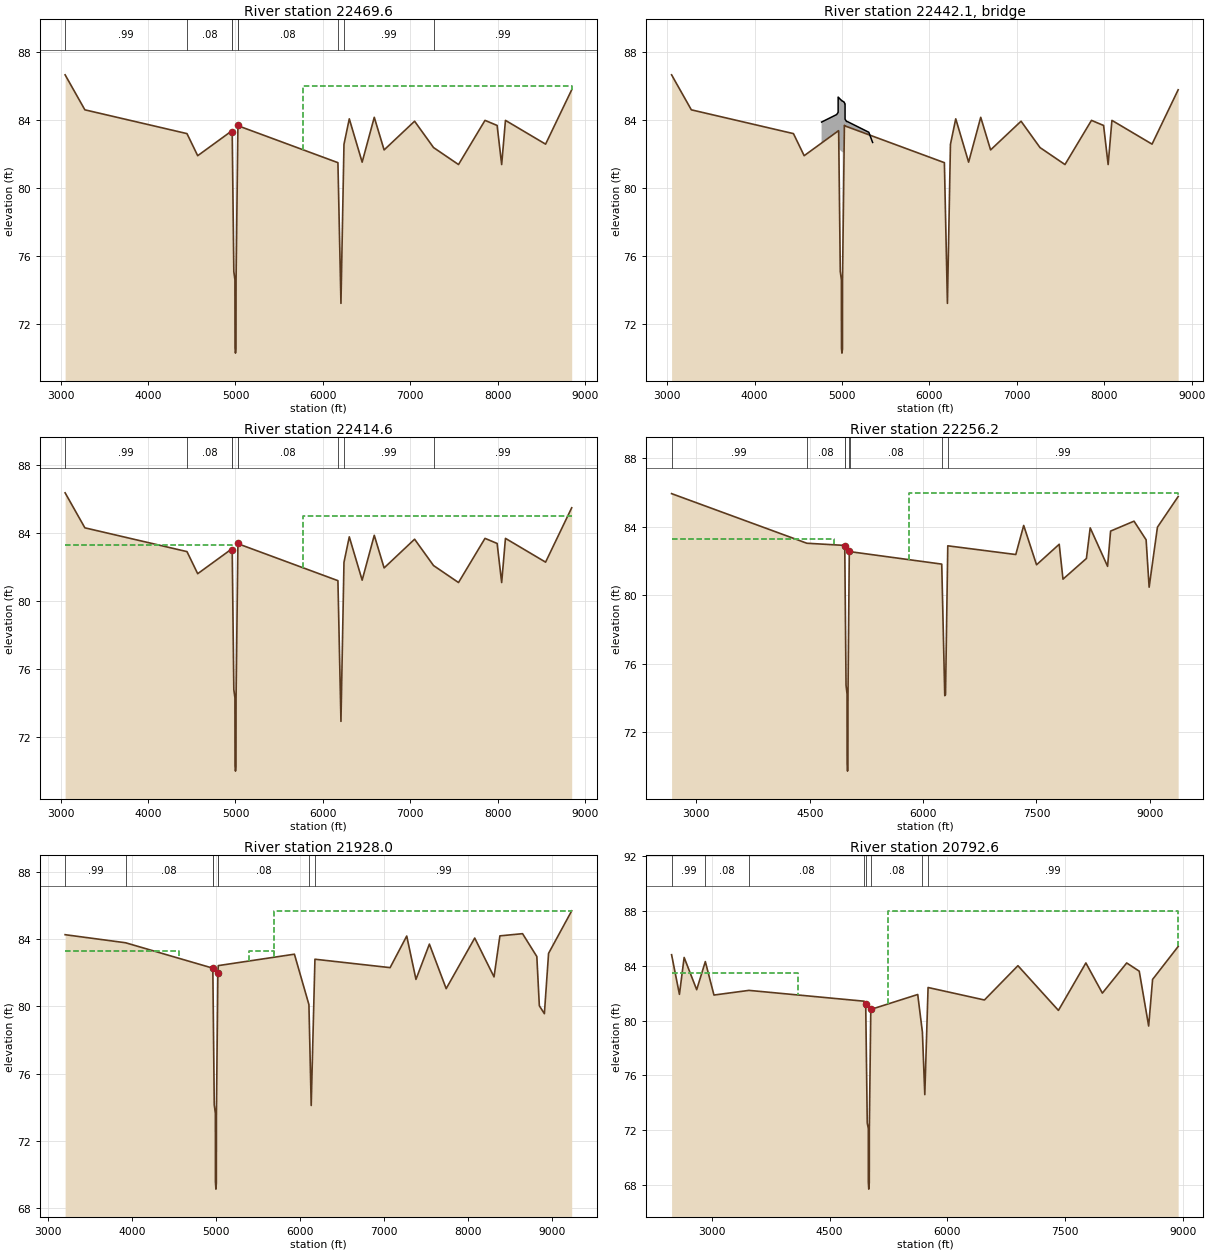
Type RM Length L Ch R = 1 ,22469.6 ,51.5,55,54.5
BEGIN DESCRIPTION:
GALWAY LANE - XS 3
Left overbank blocked with a normal ineffective flow area because of an obstruction upstream.
END DESCRIPTION:
XS GIS Cut Line= 5
      3072185.61     13867579.97      3072031.83      13865556.8
      3072034.44     13865082.93       3072051.5    13862970.529
      3071658.05    13860933.229
#Sta/Elev= 30
 3051.62   86.68 3277.56   84.62 4445.48   83.22 4567.94   81.92 4960.77   83.39
 4962.59   83.32 4981.21    75.1 4993.85   74.62 4994.98   70.59    5000    70.3
 5005.98   70.53 5006.58   74.53 5028.06   83.71 5030.74   83.68 6171.82   81.51
 6206.46   73.23  6241.1   82.59 6301.72   84.09 6448.95   81.54 6587.51   84.18
  6700.1   82.26 7048.67   83.95 7265.18    82.4 7550.96    81.4 7854.07      84
 7992.64    83.7  8044.6    81.4  8087.9      84 8546.89    82.6 8845.59    85.8
#Mann= 9 ,-1 , 0
 3051.62     .99       0 4445.48     .08       0 4960.77     .04       0
 4962.59    .015       0 5028.06     .04       0 5030.74     .08       0
 6171.82     .04       0  6241.1     .99       0 7265.18     .99       0
#XS Ineff= 2 , 0
       0 4953.93    83.3    5776       0      86
Permanent Ineff=
       F       F
Bank Sta=4962.59,5028.06
XS Rating Curve= 0
Skew Angle= 30
Exp/Cntr=.5,.3

Type RM Length L Ch R = 3 ,22442.1 ,,,
BEGIN DESCRIPTION:
GALWAY LANE
Structure ID: E115-00-00-13
END DESCRIPTION:
Bridge Culvert--1,0,-1,-1, 0
Deck Dist Width WeirC Skew NumUp NumDn MinLoCord MaxHiCord MaxSubmerge Is_Ogee
10,35,2.6,30, 37, 37, 82.7, , .95, 0, ,,,
 4767.12 4938.86 4952.63 4956.51  4956.7 4956.79 4960.77 4962.58 4967.87 4967.95
 4970.73 4970.81  4981.2 4993.85 4994.97 4995.41 4996.19 4999.13    5000 5003.12
 5004.59 5005.97 5006.58 5007.19 5022.51  5022.6 5022.69 5024.51 5028.06 5030.74
 5035.58 5035.68 5035.77 5052.83 5062.18 5307.35 5350.74
    83.9   84.34   84.44   84.47   85.37   85.37   85.35   85.34    85.3    85.3
    85.3    85.3   85.24   85.18   85.17   85.17   85.17   85.15   85.15   85.14
   85.14   85.13   85.13   85.13   85.09   85.09   85.09   85.07   85.04   85.01
   84.97   84.97   84.07   83.93   83.93    83.3    82.7
                                                                            82.3
    82.3    82.3   82.24   82.18   82.17   82.17   82.17   82.15   82.15   82.14
   82.14   82.13   82.13   82.13   82.09
                                                        
 4767.12 4938.86 4952.63 4956.51  4956.7 4956.79 4960.77 4962.58 4967.87 4967.95
 4970.73 4970.81  4981.2 4993.85 4994.97 4995.41 4996.19 4999.13    5000 5003.12
 5004.59 5005.97 5006.58 5007.19 5022.51  5022.6 5022.69 5024.51 5028.06 5030.74
 5035.58 5035.68 5035.77 5052.83 5062.18 5307.35 5350.74
    83.9   84.34   84.44   84.47   85.37   85.37   85.35   85.34    85.3    85.3
    85.3    85.3   85.24   85.18   85.17   85.17   85.17   85.15   85.15   85.14
   85.14   85.13   85.13   85.13   85.09   85.09   85.09   85.07   85.04   85.01
   84.97   84.97   84.07   83.93   83.93    83.3    82.7
                                                                            82.3
    82.3    82.3   82.24   82.18   82.17   82.17   82.17   82.15   82.15   82.14
   82.14   82.13   82.13   82.13   82.09
                                                        
BR Coef= 1 , 1 , 0 ,.9, 0 ,,,.8,0,1.2,0,
WSPro=,,,, 1 ,,,, 0 ,,,, 0 ,,,,-1 ,-1 ,-1 , 0 , 0 , 0 , 0 , 0
BC Design=,, 0 ,, 0 ,,,,,,
BC HTab HWMax=86.72

Type RM Length L Ch R = 1 ,22414.6 ,205.2,158.4,101
BEGIN DESCRIPTION:
GALWAY LANE - XS 2
Left overbank blocked with a normal ineffective flow area because of an obstruction upstream.
END DESCRIPTION:
XS GIS Cut Line= 5
      3072230.24     13867579.91      3072076.61     13865558.77
      3072079.21     13865087.01      3072096.99     13862886.62
      3071680.38    13860933.229
#Sta/Elev= 30
 3051.62   86.38 3277.56   84.32 4445.48   82.92 4567.94   81.62 4960.77   83.09
 4962.59   83.02 4981.21    74.8 4993.85   74.32 4994.98   70.29    5000      70
 5005.98   70.23 5006.58   74.23 5028.06   83.41 5030.74   83.38 6171.82   81.21
 6206.46   72.93  6241.1   82.29 6301.72   83.79 6448.95   81.24 6587.51   83.88
  6700.1   81.96 7048.67   83.65 7265.18    82.1 7550.96    81.1 7854.07    83.7
 7992.64    83.4  8044.6    81.1  8087.9    83.7 8546.89    82.3 8845.59    85.5
#Mann= 9 ,-1 , 0
 3051.62     .99       0 4445.48     .08       0 4960.77     .04       0
 4962.59    .015       0 5028.06     .04       0 5030.74     .08       0
 6171.82     .04       0  6241.1     .99       0 7265.18     .99       0
#XS Ineff= 2 , 0
       0 4956.81    83.3    5776       0      85
Permanent Ineff=
       F       F
Bank Sta=4962.59,5028.06
XS Rating Curve= 0
Skew Angle= 30
Exp/Cntr=.5,.3

Type RM Length L Ch R = 1 ,22256.2 ,330.1,328.2,326
BEGIN DESCRIPTION:
GALWAY LANE - XS 1
Interplotated channel, LIDAR overbanks
END DESCRIPTION:
XS GIS Cut Line= 6
      3072418.54     13867531.17      3072254.16     13865500.35
      3072256.41     13865299.48      3072161.85     13865158.32
      3072148.78     13862996.95      3071688.57     13860912.93
#Sta/Elev= 30
  2671.7   85.93  4461.7   83.03    4960  82.903  4963.4   82.87  4980.4   74.73
  4993.7   74.22  4994.6   70.13  5000.3   69.71 5005.31   70.08  5006.1   74.11
  5023.6    82.6    5030   82.54  6246.8   81.81  6286.8   74.12  6296.8   74.17
  6326.8   82.88  7226.8   82.37  7331.4   84.07  7501.4   81.77  7801.4   82.97
  7851.4   80.93  8161.4   82.14  8211.4   83.93  8441.4   81.68  8481.4   83.74
  8791.4   84.32  8951.4   83.23  8991.4   80.46  9101.4   83.97  9375.6   85.76
#Mann= 8 ,-1 , 0
  2671.7     .99       0  4461.7     .08       0    4960     .04       0
  4963.4    .015       0  5023.6     .04       0    5030     .08       0
  6246.8     .04       0  6326.8     .99       0
#XS Ineff= 2 , 0
       04827.313    83.3    5820       085.97657
Permanent Ineff=
       F       F
Bank Sta=4963.4,5023.6
XS Rating Curve= 0
Exp/Cntr=.3,.1

Type RM Length L Ch R = 1 ,21928.0 ,991.5,1135.4,955.5
BEGIN DESCRIPTION:
Cross Section x17
Located At: DS TILSON
END DESCRIPTION:
XS GIS Cut Line= 5
      3072862.15      13866794.8      3072602.75     13865248.45
      3072359.39      13864841.8       3072199.9      13862910.2
      3071705.26      13860915.1
#Sta/Elev= 30
  3203.5   84.26  3923.5   83.78  4961.6   82.27  4963.4   82.28  4980.4   74.14
  4993.7   73.63  4994.6   69.54  5000.3   69.12 5005.31   69.49  5006.1   73.52
  5023.6   82.01  5028.5   82.42  5935.5    83.1  6108.3    80.1  6135.5    74.1
    6180    82.8  7075.5    82.3  7273.7   84.18  7383.7    81.6  7543.7    83.7
  7743.7   81.05  8083.7   84.06  8313.7   81.75  8383.7   84.19  8653.7   84.32
  8823.7   82.96  8853.7   80.03  8913.7   79.56  8963.7   83.15  9239.2   85.68
#Mann= 8 ,-1 , 0
  3203.5     .99       0  3923.5     .08       0  4961.6     .04       0
  4963.4    .015       0  5023.6     .04       0  5028.5     .08       0
  6108.3     .04       0    6180     .99       0
#XS Ineff= 3 ,-1
  3203.5    4559    83.3  5396.2    5689    83.3    5689  9239.2   85.68
Permanent Ineff=
       F       F       F
Bank Sta=4963.4,5023.6
XS Rating Curve= 0
Exp/Cntr=.3,.1

Type RM Length L Ch R = 1 ,20792.6 ,486.6,646.1,1099.7
BEGIN DESCRIPTION:
Cross Section x16
Located At: US COLLEEN ROAD
END DESCRIPTION:
XS GIS Cut Line= 5
      3073363.78      13866668.6      3073386.84     13864327.32
      3072639.97     13864053.64      3072331.25      13862870.2
      3071757.34      13860854.3
#Sta/Elev= 30
  2486.4    84.8  2586.4   81.91  2646.4    84.6  2806.4   82.25  2916.4    84.3
  3026.4   81.86  3472.8    82.2  4941.7   81.41  4960.3   81.22 4980.01   72.53
  4993.9   72.12    4994   68.19  4999.5   67.71    5006   68.19  5006.5   72.09
  5025.2   80.81  5623.3    81.9  5682.8   79.16  5713.3    74.6  5755.1   82.41
  6473.3    81.5  6900.3      84  7416.3   80.74  7766.3    84.2  7976.3      82
  8286.3    84.2  8446.3    83.6  8566.3    79.6  8616.3      83  8942.3    85.4
#Mann= 8 ,-1 , 0
  2486.4     .99       0  2916.4     .08       0  3472.8     .08       0
  4941.7     .04       0  4960.3    .015       0  5025.2     .08       0
  5682.8     .04       0  5755.1     .99       0
#XS Ineff= 2 , 0
       0    4100    83.5  5247.8       0      88
Permanent Ineff=
       F       F
Bank Sta=4960.3,5025.2
XS Rating Curve= 0
Exp/Cntr=.3,.1

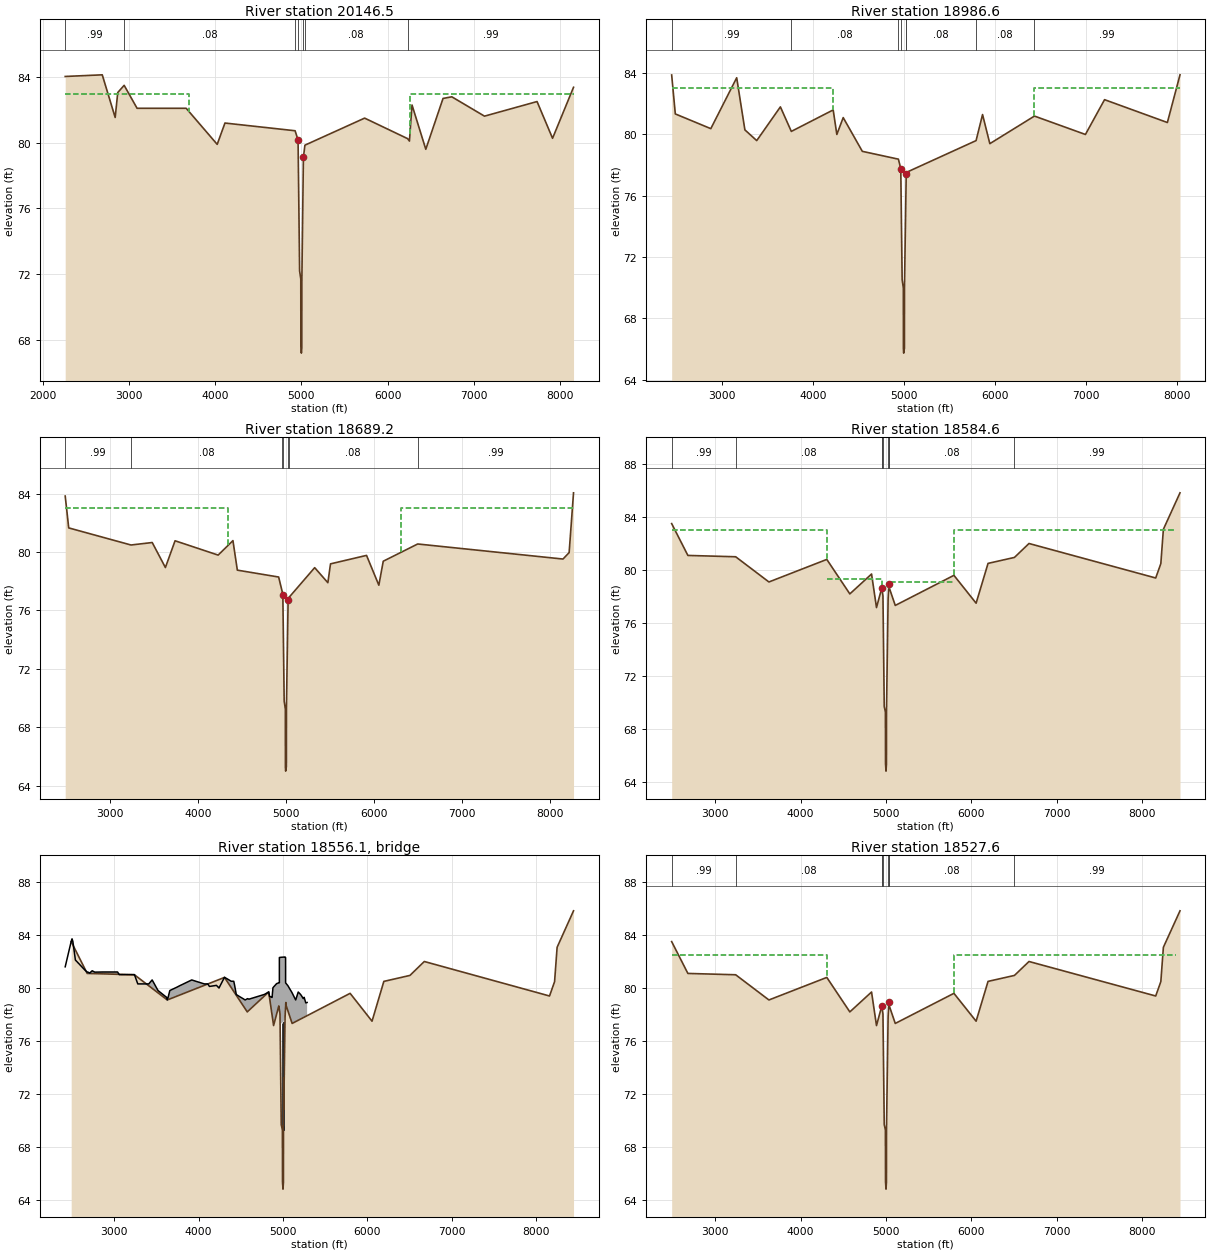
Type RM Length L Ch R = 1 ,20146.5 ,1013,1159.9,1128.3
BEGIN DESCRIPTION:
Cross Section x15
Located At: DS COLLEEN ROAD
END DESCRIPTION:
XS GIS Cut Line= 6
      3073758.27      13866717.9      3073778.07      13865893.3
      3073774.51      13864077.6      3073809.77      13863926.9
       3073716.7      13862298.4      3073516.93      13860838.6
#Sta/Elev= 30
  2258.7   84.04  2688.7   84.14  2838.7   81.54  2868.7   83.06  2942.8    83.5
  3092.8    82.1  3662.8    82.1  4022.8    79.9  4112.8    81.2  4926.9   80.73
  4961.4   80.17  4979.4   72.18  4993.1   71.68    4994   67.61  4999.7   67.17
  5004.6   67.48  5005.5   71.62  5023.3   79.11  5040.9   79.85    5734    81.5
  6232.5   80.25    6254    80.1    6284    82.3    6444    79.6    6644    82.7
  6745.8    82.8  7125.2   81.62  7735.2   82.51  7915.2   80.27  8158.6   83.38
#Mann= 7 ,-1 , 0
  2258.7     .99       0  2942.8     .08       0  4926.9     .04       0
  4961.4    .015       0  5023.3     .04       0  5040.9     .08       0
  6232.5     .99       0
#XS Ineff= 2 , 0
       0    3700      83    6260       0      83
Permanent Ineff=
       F       F
Bank Sta=4961.4,5023.3
XS Rating Curve= 0
Exp/Cntr=.3,.1

Type RM Length L Ch R = 1 ,18986.6 ,412.2,297.4,625.7
BEGIN DESCRIPTION:
Cross Section x14
Located At: US HOLLISTER
END DESCRIPTION:
XS GIS Cut Line= 4
      3074714.73      13866142.9      3074741.32      13865453.3
       3074794.4     13863058.83      3074335.47      13860602.6
#Sta/Elev= 30
  2448.9   83.88  2488.9   81.34  2878.9   80.38  3163.2    83.7  3253.2    80.3
  3383.2    79.6  3643.2    81.8  3763.2    80.2  4223.2    81.6  4263.2      80
  4333.2    81.1  4543.2    78.9  4939.4   78.39  4965.6   77.77  4980.6   70.53
  4993.9   69.99  4994.6   66.02  4997.5   65.74  5005.6   66.06  5006.3   70.03
  5025.4   77.44  5028.1   77.53  5792.7    79.6    5864    81.3    5944    79.4
    6434    81.2    6994      80  7204.1   82.27  7894.1   80.78  8032.8   83.89
#Mann= 8 ,-1 , 0
  2448.9     .99       0  3763.2     .08       0  4939.4     .04       0
  4965.6    .015       0  5025.4     .04       0  5028.1     .08       0
  5792.7     .08       0    6434     .99       0
#XS Ineff= 2 , 0
       0    4223      83    6433       0      83
Permanent Ineff=
       F       F
Bank Sta=4965.6,5025.4
XS Rating Curve= 0
Exp/Cntr=.3,.1

Type RM Length L Ch R = 1 ,18689.2 ,126.6,104.6,152.3
BEGIN DESCRIPTION:
HOLLISTER - XS 4
Interplotated channel, LIDAR overbanks
END DESCRIPTION:
XS GIS Cut Line= 5
      3074939.07       13866148.      3075056.77     13864333.36
       3075085.6     13863243.61      3075487.93      13861782.9
 3075501.320002313860422.9507514
#Sta/Elev= 30
  2489.2   83.83  2529.2   81.65    3238   80.48  3479.2   80.65  3629.2   78.94
  3739.2   80.77  4229.2   79.79  4397.7   80.78  4447.7   78.76  4917.7   78.29
    4960  77.247  4965.6   77.04  4980.6    69.8  4993.9   69.26  4994.6   65.29
  4997.5   65.01  5005.6   65.33  5006.3    69.3  5025.4   76.71    5030  76.856
  5327.7   78.93  5477.8    77.9  5507.8   79.19  5917.8   79.77  6057.8   77.73
  6107.8   79.37    6500   80.55  8152.9   79.52  8222.9   79.96  8272.9   84.05
#Mann= 7 ,-1 , 0
  2489.2     .99       0    3238     .08       0    4960     .04       0
  4965.6    .015       0  5025.4     .04       0    5030     .08       0
    6500     .99       0
#XS Ineff= 2 ,-1
  2488.1 4337.81      83    6308  8272.9      83
Permanent Ineff=
       F       F
Bank Sta=4965.6,5025.4
XS Rating Curve= 0
Exp/Cntr=.5,.3

Type RM Length L Ch R = 1 ,18584.6 ,56.9,57,62
BEGIN DESCRIPTION:
HOLLISTER - XS 3
HEC-RAS levee only, not a FEMA regulated levee.
END DESCRIPTION:
XS GIS Cut Line= 5
      3075039.76      13866153.2      3075157.46     13864338.57
      3075186.29     13863248.82      3075588.62      13861788.1
      3075603.73      13860253.4
#Sta/Elev= 30
  2488.1    83.5  2678.1    81.1  3238.1      81  3628.1    79.1  4306.5    80.8
  4576.5    78.2    4831    79.7    4889   77.17  4950.8   78.65  4952.4   78.58
  4964.7   78.05  4979.8   69.71  4993.6   69.29  4994.7   65.39  5000.4   64.84
  5005.6   65.36  5006.1   69.28    5025   77.81    5034   78.91    5039   78.65
  5108.9   77.33  5796.6    79.6  6056.6    77.5  6196.6    80.5    6506   80.95
  6676.6      82  8161.8    79.4  8221.8   80.48  8251.8   83.07  8446.5   85.82
#Mann= 9 ,-1 , 0
  2488.1     .99       0  3238.1     .08       0  4950.8     .08       0
  4952.4     .04       0  4964.7    .015       0    5025     .04       0
    5034     .04       0    5039     .08       0    6506     .99       0
#XS Ineff= 4 ,-1
  4306.7    4953    79.3    5031    5796    79.1  2488.1  4306.7      83
    5796    8400      83
Permanent Ineff=
       F       F       F       F
Bank Sta=4950.8,5034
XS Rating Curve= 0
Exp/Cntr=.5,.3

Type RM Length L Ch R = 3 ,18556.1 ,,,
BEGIN DESCRIPTION:
HOLLISTER ROAD and Pipeline upstream
Structure ID: E115-00-00-12 includes pipeline piers.
Low chord on Bridge u/s face lowered to simulate the low chord of the 1 foot diameter pipeline just upstream of the bridge.
END DESCRIPTION:
Bridge Culvert--1,0,-1,-1, 0
Deck Dist Width WeirC Skew NumUp NumDn MinLoCord MaxHiCord MaxSubmerge Is_Ogee
10,37,2.6,0, 115, 132, , , .95, 0, ,,,
  2417.2  2447.2  2467.2  2488.1  2497.2  2498.1  2508.1  2537.2  2538.1  2647.2
  2658.1  2678.1  2687.2  2707.2  2737.2  2767.2  2787.2  2868.1  2958.1  3027.2
  3038.1  3057.2  3058.1  3077.2  3127.2  3147.2  3167.2  3238.1  3239.4  3278.1
  3367.2  3408.1  3448.1  3457.2  3477.2  3518.1  3587.2  3607.2  3618.1  3628.1
  3638.1  3658.1  3677.2  3707.2  3727.2  3737.2  3747.2  3777.2  3787.2  3918.1
  3947.2  3987.2  4068.1    4101  4108.1  4128.1    4211  4238.1    4241  4306.5
    4331    4371  4386.5  4416.5  4426.5  4446.5  4448.8  4486.5  4526.5  4546.5
    4551  4566.5  4576.5    4581  4596.5    4781    4821    4831    4841  4870.5
    4871  4881.1    4889  4925.7  4928.3  4950.8  4952.4 4957.39  4957.5 4957.61
  4963.3 4963.41  4963.5  5025.3  5025.4 5031.19  5031.3 5031.41    5034    5039
  5047.8    5057  5062.9  5084.1    5106  5108.9    5151    5181  5196.5    5211
  5226.5    5241    5251    5271  5286.5
    81.6   82.41   82.95   83.51   83.69   83.71   83.51   82.15   82.11   81.38
   81.31    81.2    81.2   81.13    81.3    81.2    81.2   81.21   81.21   81.21
   81.21   81.02   81.01   81.01   81.01   81.01   81.01   81.01   80.99   80.31
   80.31   80.31   80.61   80.51   80.28   79.81   79.46   79.36   79.31   79.11
   79.31   79.81   79.87   79.96   80.02   80.05   80.08   80.18   80.21   80.61
   80.55   80.47   80.31   80.31   80.31   80.12    80.2   80.02      80   80.81
   80.72   80.57   80.51   80.51   80.21   79.51    79.5   79.35    79.2   79.12
    79.1   79.15   79.19    79.2   79.16   79.52   79.67   79.71   79.37   79.29
    79.3   80.02   80.08   80.34   80.34   80.39   80.39    80.4    82.3    82.3
   82.31   82.31   82.31   82.34   82.34   82.29   82.29   80.39   80.37   80.33
   80.26   80.19   80.13    79.9   79.67   79.63    79.1    79.7    79.6    79.5
   79.35    79.2    79.3   78.88   78.91
                                                                                
                                                                                
                                                                                
                                                                                
                                                                                
                                                                                
                                                                                
                                                                                
                                                                                
                   77.23   77.57
                                                                                
                                        
  2417.2  2447.2  2467.2  2488.1  2497.2  2498.1  2508.1  2537.2  2538.1  2647.2
  2658.1  2678.1  2687.2  2707.2  2737.2  2767.2  2787.2  2868.1  2958.1  3027.2
  3038.1  3057.2  3058.1  3077.2  3127.2  3147.2  3167.2  3238.1  3239.4  3278.1
  3367.2  3408.1  3448.1  3457.2  3477.2  3518.1  3587.2  3607.2  3618.1  3628.1
  3638.1  3658.1  3677.2  3707.2  3727.2  3737.2  3747.2  3777.2  3787.2  3918.1
  3947.2  3987.2  4068.1    4101  4108.1  4128.1    4211  4238.1    4241  4306.5
    4331    4371  4386.5  4416.5  4426.5  4446.5  4448.8  4486.5  4526.5  4546.5
    4551  4566.5  4576.5    4581  4596.5    4781    4821    4831    4841  4870.5
    4871  4881.1    4889  4925.7  4928.3  4950.8  4952.4 4957.39  4957.5 4957.61
  4963.3 4963.41  4963.5  4964.7  4979.8  4993.4  4993.6  4994.7  4996.1  4996.9
  4999.5  5000.4  5002.9  5003.9  5005.6  5006.1 5006.21  5006.6    5025 5025.19
  5025.3  5025.4 5031.19  5031.3 5031.41    5034    5039  5047.8    5057  5062.9
  5084.1    5106  5108.9    5151    5181  5196.5    5211  5226.5    5241    5251
    5271  5286.5
    81.6   82.41   82.95   83.51   83.69   83.71   83.51   82.15   82.11   81.38
   81.31    81.2    81.2   81.13    81.3    81.2    81.2   81.21   81.21   81.21
   81.21   81.02   81.01   81.01   81.01   81.01   81.01   81.01   80.99   80.31
   80.31   80.31   80.61   80.51   80.28   79.81   79.46   79.36   79.31   79.11
   79.31   79.81   79.87   79.96   80.02   80.05   80.08   80.18   80.21   80.61
   80.55   80.47   80.31   80.31   80.31   80.12    80.2   80.02      80   80.81
   80.72   80.57   80.51   80.51   80.21   79.51    79.5   79.35    79.2   79.12
    79.1   79.15   79.19    79.2   79.16   79.52   79.67   79.71   79.37   79.29
    79.3   80.02   80.08   80.34   80.34   80.39   80.39    80.4    82.3    82.3
   82.31   82.31   82.31   82.32   82.43   82.53   82.54   82.54   82.55   82.56
   82.58   82.57   82.55   82.54   82.52   82.52   82.52   82.51   82.34   82.34
   82.34   82.34   82.29   82.29   80.39   80.37   80.33   80.26   80.19   80.13
    79.9   79.67   79.63    79.1    79.7    79.6    79.5   79.35    79.2    79.3
   78.88   78.91
                                                                                
                                                                                
                                                                                
                                                                                
                                                                                
                                                                                
                                                                                
                                                                                
                                                                                
                   78.31   78.32   78.43   78.53   78.54   78.54   78.55   78.56
   78.58   78.57   78.55   78.54   78.52   78.52   78.52   78.51   78.34   78.34
   77.85
                                                                                
                
Pier Skew, UpSta & Num, DnSta & Num=  ,4993.4, 2 ,4993.4, 2 , 0 , 0 , 0 ,,
      .5      .5
    67.8      79
      .5      .5
    67.8      79
Pier Skew, UpSta & Num, DnSta & Num=  ,5006.2, 2 ,5006.2, 2 , 0 , 0 , 0 ,,
      .5      .5
    67.1      79
      .5      .5
    67.1      79
BR Coef= 1 , 1 , 1 ,.9, 0 ,,,.8,-1,1.2,0,
WSPro=,,,, 1 ,,,, 0 ,,,, 0 ,,,,-1 ,-1 ,-1 , 0 , 0 , 0 , 0 , 0
BC Design=,, 0 ,, 0 ,,,,,,
BC HTab HWMax=83.7

Type RM Length L Ch R = 1 ,18527.6 ,98.4,94.3,103.7
BEGIN DESCRIPTION:
HOLLISTER - XS 2
HEC-RAS levee only, not FEMA regulated levee.
END DESCRIPTION:
XS GIS Cut Line= 5
      3075096.38      13866156.4      3075214.14     13864340.85
      3075242.83     13863256.23       3075641.5      13861808.7
      3075652.87      13860258.3
#Sta/Elev= 30
  2488.1    83.5  2678.1    81.1  3238.1      81  3628.1    79.1  4306.5    80.8
  4576.5    78.2    4831    79.7    4889   77.17  4950.8   78.65  4952.4   78.58
  4964.7   78.05  4979.8   69.71  4993.6   69.29  4994.7   65.39  5000.4   64.84
  5005.6   65.36  5006.1   69.28    5025   77.81    5034   78.91    5039   78.65
  5108.9   77.33  5796.6    79.6  6056.6    77.5  6196.6    80.5    6506   80.95
  6676.6      82  8161.8    79.4  8221.8   80.48  8251.8   83.07  8446.5   85.82
#Mann= 9 ,-1 , 0
  2488.1     .99       0  3238.1     .08       0  4950.8     .08       0
  4952.4     .04       0  4964.7    .015       0    5025     .04       0
    5034     .04       0    5039     .08       0    6506     .99       0
#XS Ineff= 4 ,-1
 4306.48  4950.8    77.6    5034    5796    77.6  2488.1 4306.48    82.5
    5796    8400    82.5
Permanent Ineff=
       F       F       F       F
Bank Sta=4950.8,5034
XS Rating Curve= 0
Exp/Cntr=.5,.3

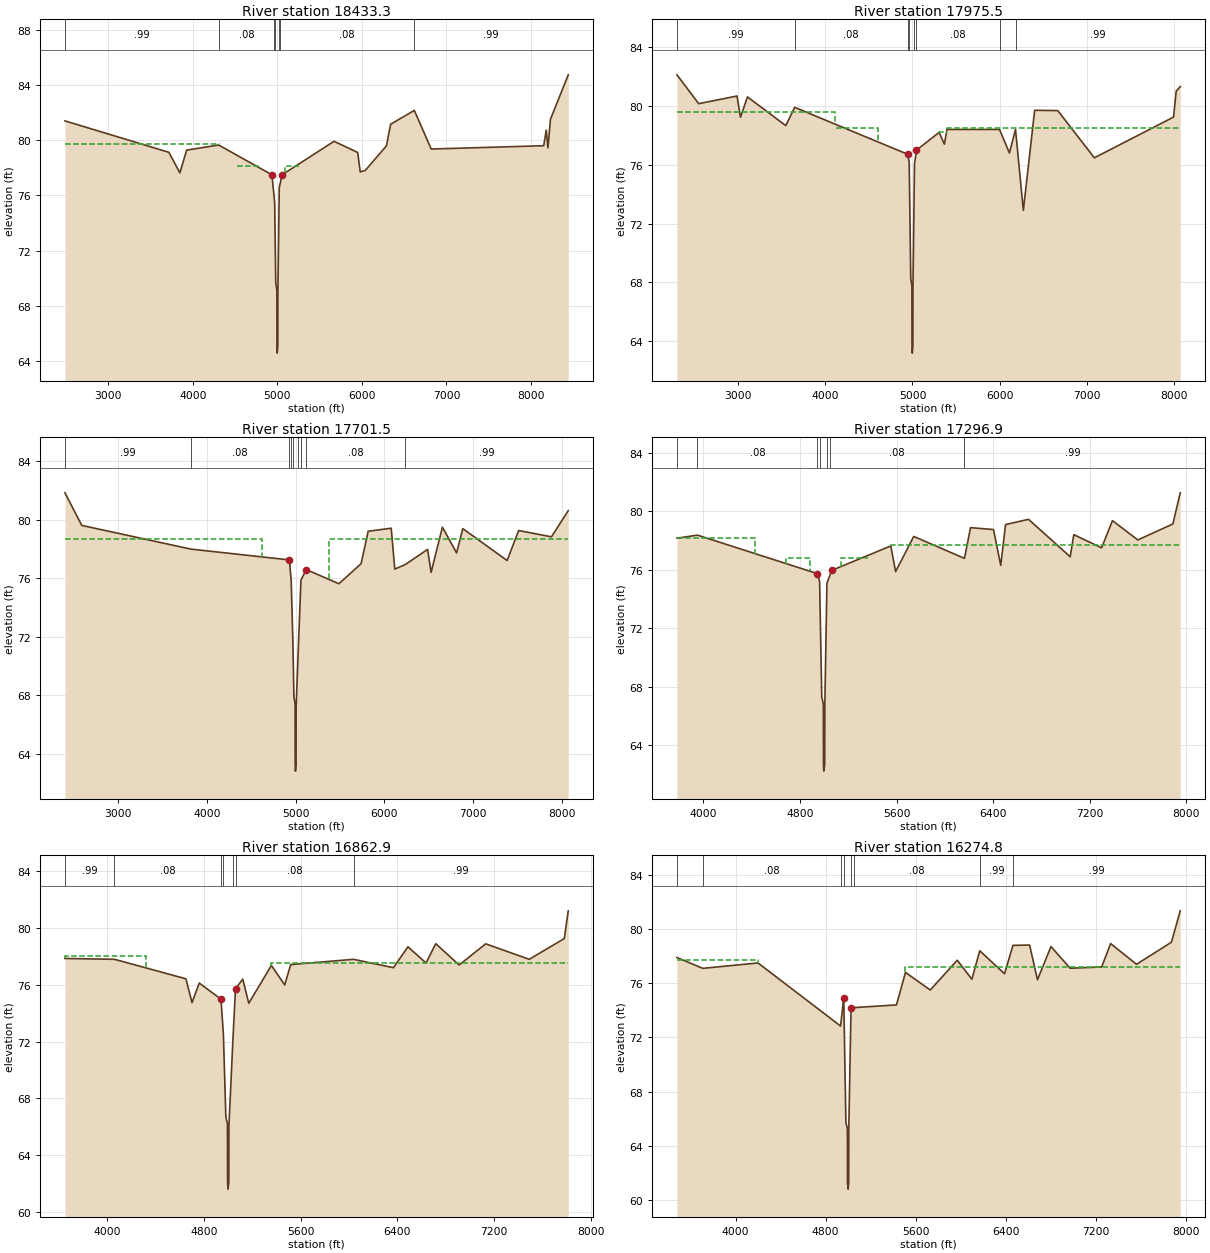
Type RM Length L Ch R = 1 ,18433.3 ,424.9,457.8,575.1
BEGIN DESCRIPTION:
HOLLISTER - XS 1
Interplotated channel, LIDAR overbanks
END DESCRIPTION:
XS GIS Cut Line= 5
      3075194.48     13866153.81      3075312.23     13864338.24
      3075340.92     13863253.63       3075739.6     13861806.19
      3075750.97     13860255.77
#Sta/Elev= 30
  2485.9    81.4  3715.9   79.12  3845.9   77.63  3925.9   79.28  4305.3   79.65
  4935.3   77.49    4960   75.97 4967.57    75.5  4980.4   69.65  4993.7   69.14
  4994.6   65.16  4997.6   64.56    5005   65.02  5005.9   69.01 5022.02   76.56
    5025   76.64  5055.3   77.49  5670.3   79.92  5950.3   79.11  5980.3    77.7
  6040.3   77.81  6290.3   79.59  6340.3   81.16  6620.3   82.16  6820.3   79.36
  8151.6    79.6  8181.6   80.73  8201.6   79.45  8231.6   81.52  8442.1   84.74
#Mann= 7 ,-1 , 0
  2485.9     .99       0  4305.3     .08       0    4960     .04       0
 4967.57    .015       0 5022.02     .04       0    5025     .08       0
  6620.3     .99       0
#XS Ineff= 4 ,-1
  2485.9 4305.13    79.7 4516.39 4766.63    78.1 5093.35 5260.18   78.14
 5669.91  8442.1    79.7
Permanent Ineff=
       F       F       F       F
Bank Sta=4935.3,5055.3
XS Rating Curve= 0
Exp/Cntr=.3,.1

Type RM Length L Ch R = 1 ,17975.5 ,289.4,274,244.6
BEGIN DESCRIPTION:
Cross Section x13
Located At: DS HOLLISTER
END DESCRIPTION:
XS GIS Cut Line= 6
       3075541.5      13866373.4      3075617.01      13864931.9
      3075656.38     13864154.92      3075878.22     13863254.78
      3076227.91      13862301.5      3076626.69      13860718.4
#Sta/Elev= 30
  2295.1   82.11  2545.1   80.15  2985.1   80.67  3025.1   79.23  3105.1   80.61
  3545.1   78.66  3647.8    79.9    4946   76.71  4962.7   76.16  4980.4   68.29
  4993.7   67.78  4994.6    63.8  4997.6    63.2    5005   63.66  5005.9   67.65
  5023.4   76.04  5046.4   76.99  5306.7    78.2  5366.7    77.4  5396.7    78.4
    6000    78.4  6113.7    76.8  6183.7    78.4  6273.7    72.9  6403.7    79.7
    6669   79.68    7089   76.47    7999   79.24    8029      81  8075.7   81.31
#Mann= 8 ,-1 , 0
  2295.1     .99       0  3647.8     .08       0    4946     .04       0
  4962.7    .015       0  5023.4     .04       0  5046.4     .08       0
    6000     .05       0  6183.7     .99       0
#XS Ineff= 4 ,-1
  2295.1    4105    79.6 4120.16  4599.8   78.47 5308.84    5400   78.25
    5400  8075.7    78.5
Permanent Ineff=
       F       F       F       F
#Block Obstruct= 2 , 0
       0                 6183.65       0    78.4
Bank Sta=4946,5046.4
XS Rating Curve= 0
Exp/Cntr=.3,.1

Type RM Length L Ch R = 1 ,17701.5 ,429.5,404.6,283.5
BEGIN DESCRIPTION:
interpolated XS downstream of x13
END DESCRIPTION:
XS GIS Cut Line= 6
      3075877.99     13866339.42       3075953.5     13864897.87
      3075992.88     13864120.85      3076072.98     13863457.26
      3076388.17     13862209.26      3076686.33     13860739.77
#Sta/Elev= 30
  2398.1   81.85  2588.1   79.62  3818.1      78  4929.6   77.26  4949.6   75.88
  4969.6   71.44  4980.4    67.9  4993.7   67.39  4994.6   63.41  4997.6   62.81
    5005   63.27  5005.9   67.26  5029.6    71.1  5059.6   75.87  5119.6    76.6
    5488   75.63    5738      77    5818   79.22    6078   79.43    6118   76.63
    6238   76.95    6488   77.98    6528   76.41  6655.2    79.5  6815.2   77.74
  6885.2    79.4  7385.2   77.22  7515.2   79.27  7885.2   78.84  8074.7   80.63
#Mann= 9 ,-1 , 0
  2398.1     .99       0  3818.1     .08       0  4929.6     .08       0
  4949.6     .04       0  4969.6    .015       0  5029.6     .04       0
  5059.6     .08       0  5119.6     .08       0    6238     .99       0
#XS Ineff= 2 , 0
       0 4614.98    78.7    5373       0    78.7
Permanent Ineff=
       F       F
Bank Sta=4929.6,5119.6
XS Rating Curve= 0
Exp/Cntr=.3,.1

Type RM Length L Ch R = 1 ,17296.9 ,430.9,434,405.9
BEGIN DESCRIPTION:
XS 12A
END DESCRIPTION:
XS GIS Cut Line= 6
       3076291.1       13864901.      3076477.18     13864069.93
      3076398.24     13863345.28      3076452.07      13862546.7
      3076512.81     13861854.27      3076711.22      13860781.2
#Sta/Elev= 30
  3781.4   78.16  3951.4   78.37  4943.3   75.74    4945   75.69  4962.7    75.2
  4980.4   67.33  4993.7   66.82  4994.6   62.84  4997.6   62.24    5005    62.7
  5005.9   66.69  5023.4   75.08    5045   75.56  5063.3   75.96  5552.2   77.63
  5592.2   75.88  5742.2   78.28  6162.2   76.78  6212.6   78.88  6402.6   78.75
  6462.6   76.31  6502.6   79.09  6692.6   79.45  7037.7   76.89  7067.7    78.4
  7297.7    77.5  7387.7   79.36  7597.7   78.04  7887.7   79.13    7949   81.26
#Mann= 7 ,-1 , 0
  3781.4     .99       0  3951.4     .08       0    4945     .04       0
  4962.7    .015       0  5023.4     .04       0    5045     .08       0
  6162.2     .99       0
#XS Ineff= 4 ,-1
  3781.4 4431.34    78.2 4683.22 4881.83   76.84 5140.02 5363.46   76.84
 5552.76    7949    77.7
Permanent Ineff=
       F       F       F       F
Bank Sta=4943.3,5063.3
XS Rating Curve= 0
Exp/Cntr=.3,.1

Type RM Length L Ch R = 1 ,16862.9 ,430.3,588.1,644.9
BEGIN DESCRIPTION:
interpolated XS upstream of x12
END DESCRIPTION:
XS GIS Cut Line= 5
       3076704.3      13864940.1      3076905.59     13864041.01
      3076820.36     13863258.57       3076743.4     13861836.88
      3076739.06      13860803.9
#Sta/Elev= 30
  3648.9   77.84  4058.9   77.78  4650.3   76.41  4700.3   74.73  4760.3   76.11
  4940.3   74.98  4960.3   72.47  4980.4   66.71  4993.7    66.2  4994.6   62.22
  4997.6   61.62    5005   62.08  5005.9   66.07  5040.3   72.37  5060.3   75.69
  5120.3   76.39  5170.3   74.69  5357.4   77.35  5467.4   75.98  5517.4   77.41
  6037.4   77.78  6367.4   77.19  6487.4   78.66  6637.4   77.52  6717.4   78.88
  6911.2   77.38  7131.2   78.87  7491.2   77.78  7781.2   79.24  7814.2   81.19
#Mann= 7 ,-1 , 0
  3648.9     .99       0  4058.9     .08       0  4940.3     .04       0
  4960.3    .015       0  5040.3     .04       0  5060.3     .08       0
  6037.4     .99       0
#XS Ineff= 2 , 0
       0    4323      78    5353       0    77.5
Permanent Ineff=
       F       F
Bank Sta=4940.3,5060.3
XS Rating Curve= 0
Exp/Cntr=.3,.1

Type RM Length L Ch R = 1 ,16274.8 ,1138,1012.8,832.4
BEGIN DESCRIPTION:
Cross Section x12
Located At: U/S ROMA
END DESCRIPTION:
XS GIS Cut Line= 5
      3076737.39     13864932.32      3077371.63     13863705.22
      3077523.22      13863390.8      3077114.16      13862238.4
      3076748.85      13860764.5
#Sta/Elev= 30
  3479.6    77.9  3709.6    77.1  4199.6    77.5  4933.4   72.84  4961.6   74.92
  4980.5   65.73  4994.1   65.25  4994.6   61.26  5000.3   60.79  5005.7   61.27
  5006.4   65.25  5026.3   74.16  5053.6    74.2    5430    74.4    5510    76.8
    5730    75.5    5970    77.7    6100    76.3    6170    78.4    6390    76.7
  6465.1    78.8  6612.8   78.82  6682.8   76.26  6802.8   78.71  6972.8   77.11
  7252.8    77.2  7332.8   78.93  7562.8    77.4  7872.8   79.03  7951.2   81.35
#Mann= 8 ,-1 , 0
  3479.6     .99       0  3709.6     .08       0  4933.4     .04       0
  4961.6    .015       0  5026.3     .04       0  5053.6     .08       0
    6170     .99       0  6465.1     .99       0
#XS Ineff= 2 , 0
       0  4199.6    77.7    5510       0    77.2
Permanent Ineff=
       F       F
Bank Sta=4961.6,5026.3
XS Rating Curve= 0
Exp/Cntr=.3,.1