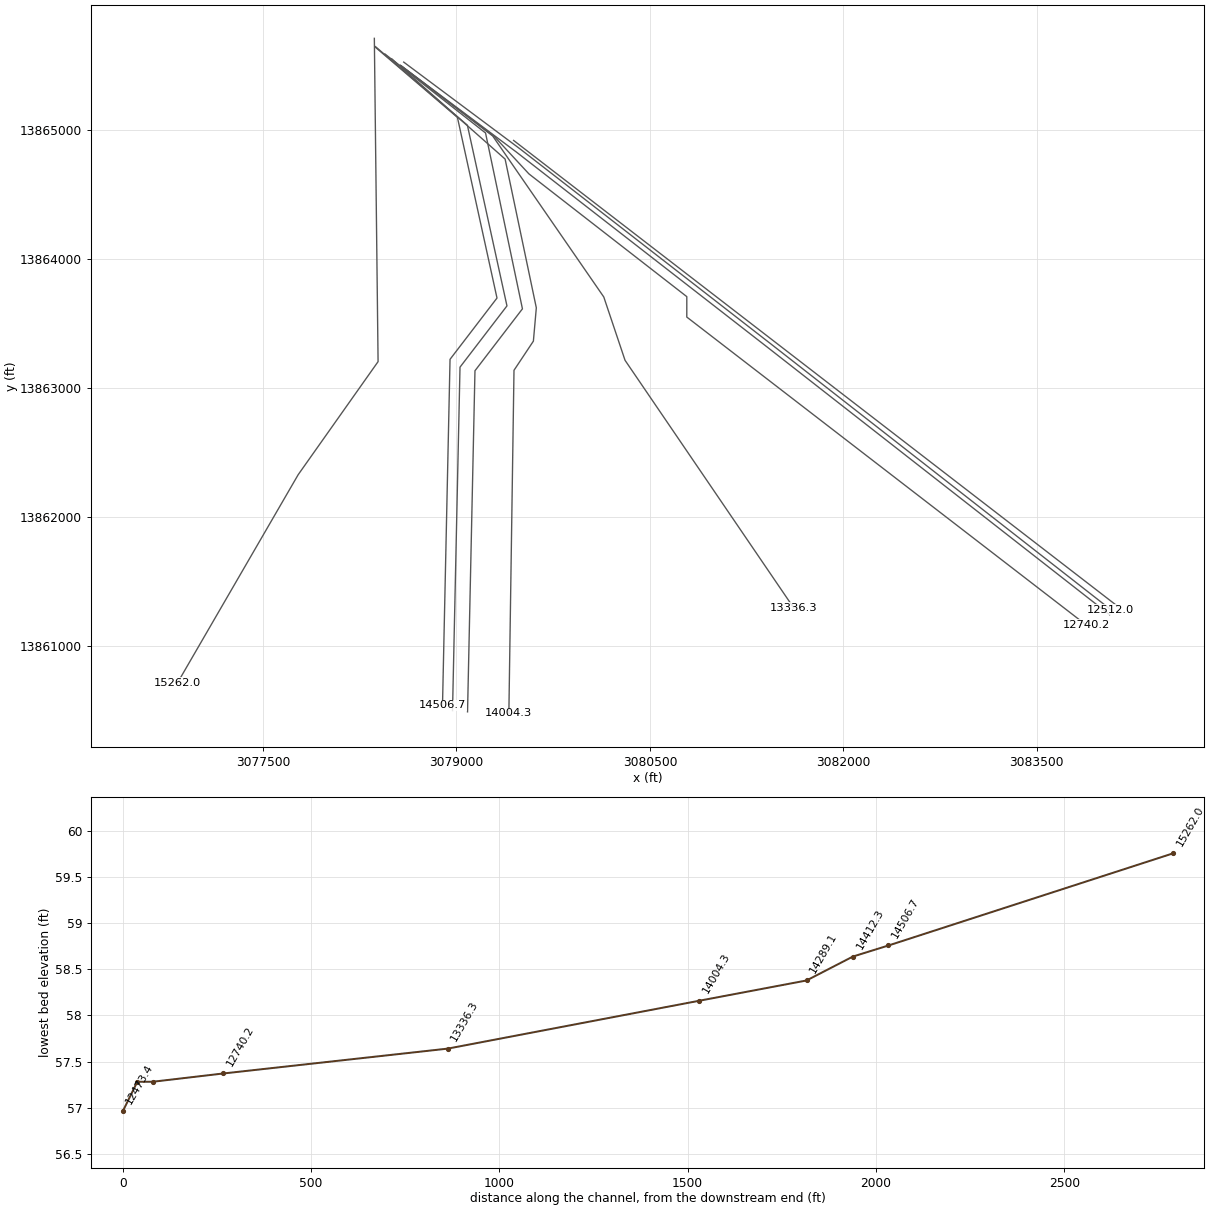
HEC-RAS study E115-00-00.prj: E115-00-00

--- E115-00-00.g01 (geometry) --- (continued)

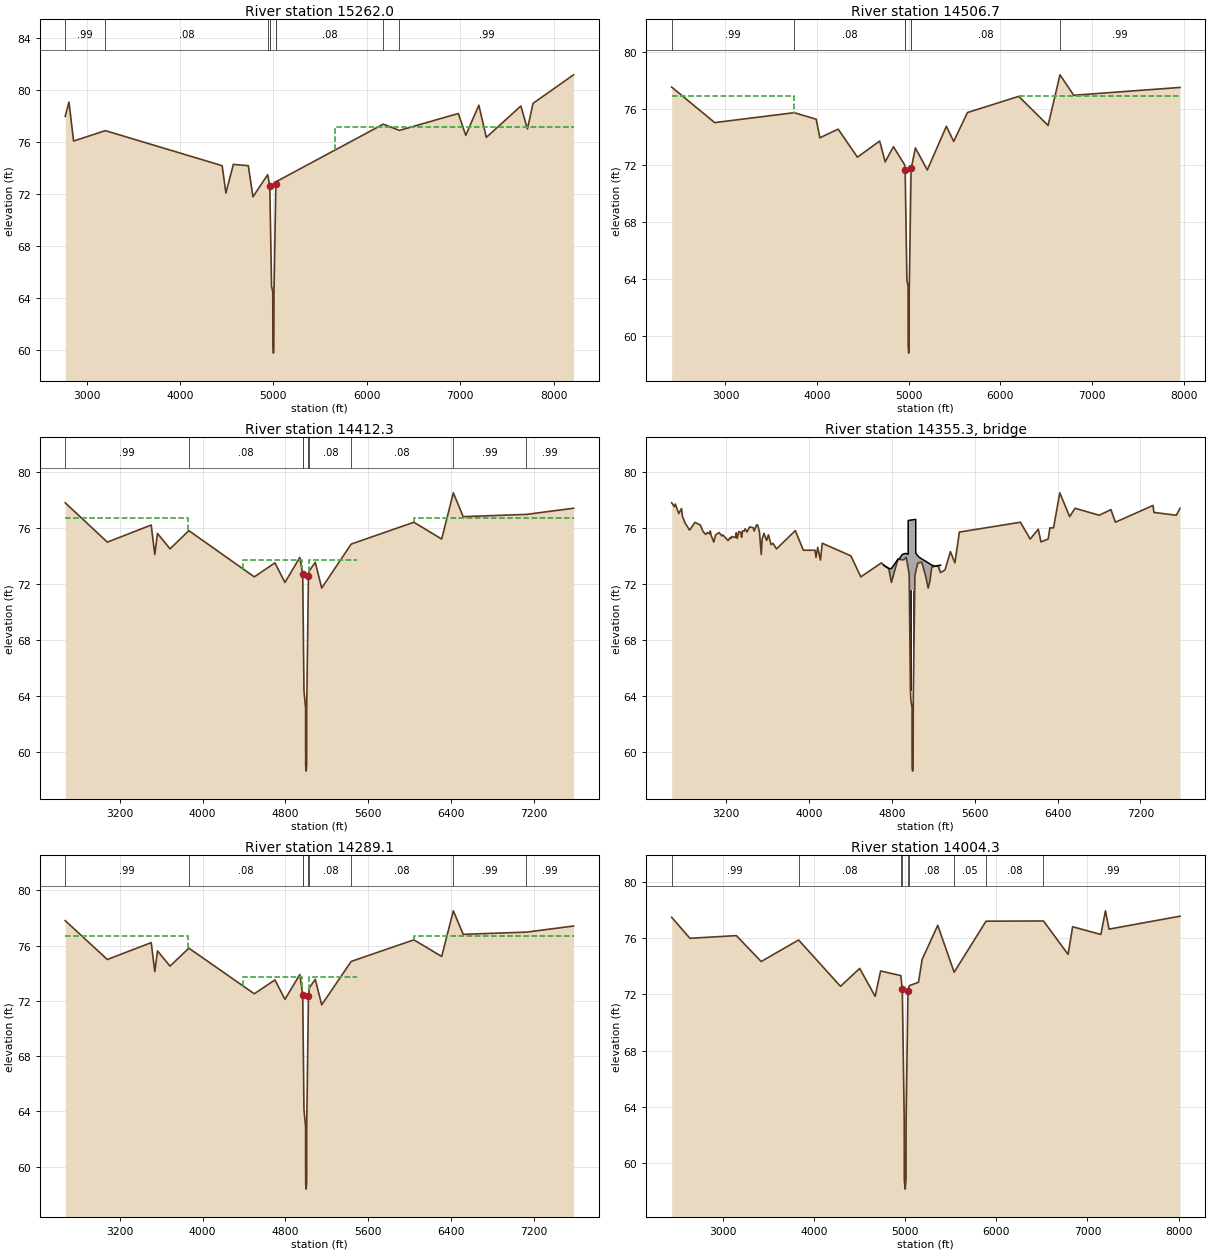
Type RM Length L Ch R = 1 ,15262.0 ,934.1,755.3,681.1
BEGIN DESCRIPTION:
Cross Section x11
Located At: U/S BINGLE
HEC-RAS levee only, not FEMA regulated levee.
END DESCRIPTION:
XS GIS Cut Line= 4
      3078363.26     13865707.76      3078392.24     13863203.21
      3077772.55      13862327.2      3076837.32      13860715.4
#Sta/Elev= 30
  2771.5      78  2811.5    79.1  2861.5    76.1  3201.5    76.9  4451.5    74.2
  4491.5    72.1  4571.5    74.3  4731.5    74.2  4781.5    71.8  4938.6   73.51
  4961.4   72.66  4961.5   72.66  4980.3   64.92  4993.5   64.46  4994.6   60.24
  5000.3   59.76  5004.5    60.1  5006.2   64.29  5026.5   72.79  5032.4   72.98
  6176.2    77.4  6349.2   76.92  6979.2   78.22  7059.2   76.54  7199.2   78.86
  7279.2   76.38  7649.2    78.8  7719.2   77.03  7779.2      79  8212.7    81.2
#Mann= 9 ,-1 , 0
  2771.5     .99       0  3201.5     .08       0  4938.6     .04       0
  4961.4    .015       0  4961.5    .015       0  5026.5     .04       0
  5032.4     .08       0  6176.2     .99       0  6349.2     .99       0
#XS Ineff= 2 , 0
       0                    5658       0    77.2
Permanent Ineff=
       F       F
Bank Sta=4961.5,5026.5
XS Rating Curve= 0
Exp/Cntr=.3,.1

Type RM Length L Ch R = 1 ,14506.7 ,72.8,94.4,79.7
BEGIN DESCRIPTION:
BINGLE RD - XS 4
Interplotated channel, LIDAR overbanks
END DESCRIPTION:
XS GIS Cut Line= 5
  3078370.720585  13865639.45347      3079007.55     13865095.38
       3079314.4     13863695.75      3078950.26     13863221.18
      3078891.83      13860541.8
#Sta/Elev= 30
  2412.8  77.523  2882.8   75.02  3750.4   75.72  3990.4   75.26  4030.4   73.95
  4230.4   74.56  4440.4   72.58  4683.3   73.72  4743.3   72.25  4833.3   73.32
    4955  72.056  4961.5   71.66  4980.3   63.92  4993.5   63.46  4994.6   59.24
  5000.3   58.76  5004.5    59.1  5006.2   63.29  5026.5   71.79    5030  71.872
  5073.3   73.23  5203.3   71.68  5411.4   74.76  5491.4   73.69  5641.4   75.73
  6201.4   76.87  6521.4   74.82  6651.4   78.39  6801.4   76.95  7961.5    77.5
#Mann= 7 ,-1 , 0
  2412.8     .99       0  3750.4     .08       0    4955     .04       0
  4961.5    .015       0  5026.5     .04       0    5030     .08       0
  6651.4     .99       0
#XS Ineff= 2 ,-1
    6201    8000    76.9    2400    3748    76.9
Permanent Ineff=
       F       F
Bank Sta=4961.5,5026.5
XS Rating Curve= 0
Exp/Cntr=.5,.3

Type RM Length L Ch R = 1 ,14412.3 ,119.4,123.2,125.4
BEGIN DESCRIPTION:
BINGLE RD - XS 3
END DESCRIPTION:
XS GIS Cut Line= 6
      3078371.95      13865643.6       3079084.8     13865034.61
      3079391.66     13863634.98      3079027.52     13863160.42
 3078970.328311313860537.7796088      3078969.54     13860501.63
#Sta/Elev= 30
2672.672    77.83079.672   74.993503.422   76.21 3538.06   74.11 3564.04   75.61
3685.282   74.513867.152   75.814499.351   72.514698.532   73.514795.272   72.11
4938.942    73.94966.482   72.724966.912    72.74979.042   64.394994.802   63.14
4995.231   59.04    5000   58.645004.852   59.075005.372   63.115022.249    72.6
 5032.21   72.965088.252   73.555150.342   71.715435.001   74.856040.792   76.41
6309.252   75.216421.842   78.516517.101   76.817128.342   76.97 7582.83   77.41
#Mann= 9 ,-1 , 0
2672.672     .99       03867.152     .08       04966.482     .04       0
4966.912    .015       05022.249     .04       0 5032.21     .08       0
5435.001     .08       06421.842     .99       07128.342     .99       0
#XS Ineff= 4 ,-1
 4394.87 4956.87    73.7 5029.87 5494.87    73.7    6039 7669.87    76.7
 2669.87    3859    76.7
Permanent Ineff=
       F       F       F       F
Bank Sta=4966.912,5022.249
XS Rating Curve= 0
Skew Angle= 30
Exp/Cntr=.5,.3

Type RM Length L Ch R = 3 ,14355.3 ,,,
BEGIN DESCRIPTION:
BINGLE ROAD
Structure ID: E115-00-00-11
Bridge has 30 degree skew with the channel.
END DESCRIPTION:
Bridge Culvert--1,0,-1,-1, 0
Deck Dist Width WeirC Skew NumUp NumDn MinLoCord MaxHiCord MaxSubmerge Is_Ogee
10,94,2.6,30, 52, 52, , , .95, 0, ,,,
4720.7924725.9924769.2924795.2724858.2324868.0224901.9524912.5324931.9324938.942
4956.9524957.0424957.1424966.4824966.9124968.8324968.9324968.9924979.0424982.762
4982.9424994.8024995.2324996.7925000.0025003.5525004.8525005.3725005.7125005.802
5006.4925019.9925020.0925022.2425027.7125030.2125030.3125030.4025032.2025032.722
5050.3125062.7025072.4825088.2525124.3625150.3425167.6625184.9825217.8025238.592
5244.0325270.022
   73.35   73.31   73.11    73.1   73.77   73.76   74.12   74.14   74.18   74.17
   74.13   76.53   76.53   76.54   76.54   76.54   76.55   76.55   76.56   76.56
   76.56   76.58   76.58   76.58   76.58   76.59   76.59   76.59   76.59   76.59
   76.59   76.61   76.61   76.61   76.62   76.59   76.59   74.19   74.17   74.17
   74.02   73.91   73.87   73.79   73.63   73.51   73.43   73.35   73.27    73.3
   73.31   73.35
                                                                                
                                                           71.55   71.56   71.56
   71.56   71.58   71.58   71.58   71.58   71.59   71.59   71.59   71.59   71.59
   71.59   71.61
                                                                                
                
4720.7924725.9924769.2924795.2724858.2324868.0224901.9524912.5324931.9324938.942
4956.9524957.0424957.1424966.4824966.9124968.8324968.9324968.9924979.0424982.762
4982.9424994.8024995.2324996.7925000.0025003.5525004.8525005.3725005.7125005.802
5006.4925019.9925020.0925022.2425027.7125030.2125030.3125030.4025032.2025032.722
5050.3125062.7025072.4825088.2525124.3625150.3425167.6625184.9825217.8025238.592
5244.0325270.022
   73.35   73.31   73.11    73.1   73.77   73.76   74.12   74.14   74.18   74.17
   74.13   76.53   76.53   76.54   76.54   76.54   76.55   76.55   76.56   76.56
   76.56   76.58   76.58   76.58   76.58   76.59   76.59   76.59   76.59   76.59
   76.59   76.61   76.61   76.61   76.62   76.59   76.59   74.19   74.17   74.17
   74.02   73.91   73.87   73.79   73.63   73.51   73.43   73.35   73.27    73.3
   73.31   73.35
                                                                                
                                                           71.55   71.56   71.56
   71.56   71.58   71.58   71.58   71.58   71.59   71.59   71.59   71.59   71.59
   71.59   71.61
                                                                                
                
Pier Skew, UpSta & Num, DnSta & Num=  ,4978.955, 2 ,4978.955, 2 , 0 , 0 , 0 ,,
       2       2
   63.25   72.56
       2       2
   63.01   72.32
Pier Skew, UpSta & Num, DnSta & Num=  ,5006.408, 2 ,5006.408, 2 , 0 , 0 , 0 ,,
       2       2
   62.11   72.59
       2       2
   61.87   72.35
BR Coef= 1 , 1 , 1 ,1.05, 0 ,,,.8,-1,1.2,0,
WSPro=,,,, 1 ,,,, 0 ,,,, 0 ,,,,-1 ,-1 ,-1 , 0 , 0 , 0 , 0 , 0
BR U #Sta/Elev= 174
 2672.67    77.8 2698.67   77.52 2707.27   77.71 2741.97   77.03 2767.87   77.39
 2776.57   76.84 2802.57   76.35 2845.87   75.85 2897.77    76.4 2949.77   76.21
 2975.77   75.75 3001.77   75.54 3019.07   75.68 3036.37   75.58 3045.07   75.79
 3053.67   75.48 3079.67   74.99 3096.97   75.51 3131.67   75.67 3157.57   75.43
 3166.27   75.51 3218.27    75.1 3235.57   75.31 3244.17   75.24 3252.87   75.39
 3287.47   75.32 3296.17   75.66 3304.87   75.25 3322.17   75.75 3339.47   75.68
 3348.17   75.34 3356.77   75.79 3374.17   75.78 3382.77   75.94 3400.07   75.71
 3426.07   76.08 3460.77   76.01 3469.37   75.78 3484.67   76.09 3493.27   76.22
 3503.42   76.21 3504.03   76.19 3520.74   75.71 3538.06   74.11 3538.67   74.19
 3546.72   75.21 3564.04   75.61 3564.65    75.6 3590.02   75.11 3607.34   75.51
 3633.32   74.81 3650.64   74.91 3685.28   74.51 3711.87    74.7 3746.51   74.95
 3833.11   75.57 3867.15   75.81 3945.09   74.41  4032.3   74.41 4040.96   74.41
 4057.68   74.41 4066.34   73.91 4066.94   73.93 4083.66   74.61 4084.26   74.59
 4101.58   73.99 4109.64   73.71 4126.96   74.91 4257.47   74.49 4261.02   74.47
 4404.09   74.01 4456.65   73.18 4482.63   72.77 4499.35   72.51 4655.84    73.3
 4690.48   73.47 4698.53   73.51 4720.79   73.35 4725.99   73.31 4769.29   73.11
 4795.27   72.11 4858.23   73.77 4868.02   73.76 4901.96   73.73 4912.53   73.72
 4931.93   73.85 4938.94    73.9 4956.95   73.13 4957.04   73.12 4957.14   73.12
 4966.48   72.72 4966.91    72.7 4968.83   71.39 4968.93   71.32 4968.99   71.28
 4979.04   64.39 4982.76   63.75 4982.93   63.74  4994.8   63.14 4995.23   59.04
 4996.79   58.75    5000   58.64 5003.55   58.83 5004.85   59.07 5005.37   63.11
 5005.71   63.13  5005.8   63.13 5006.49   63.83 5019.99   71.34 5020.09    71.4
 5022.25    72.6 5027.71    72.8 5030.21   72.89 5030.31   72.89  5030.4    72.9
 5032.21   72.96 5032.73   72.98 5050.31   73.49  5062.7   73.52 5072.48   73.54
 5088.25   73.55 5124.36   72.61 5150.34   71.71 5167.66   72.21 5184.98   73.21
  5217.8   73.27 5244.04   73.31 5270.02   72.81 5287.08   72.89 5313.33   73.01
 5356.37   74.09 5365.29   74.31 5408.59   73.51    5435   74.85 5451.89   75.71
 5494.93   75.76 6040.79   76.41 6136.05   75.21 6213.99   75.91 6231.05   75.32
 6239.97   75.01 6248.37   75.03 6291.67   75.16    6309   75.21 6309.25   75.21
 6326.58   76.01 6343.64   76.01 6361.22   76.01 6369.62   76.36 6421.84   78.51
 6430.24   78.36 6473.54   77.59  6517.1   76.81 6551.48   77.21 6569.06   77.41
 6586.12   77.37 6638.08   77.26 6707.37   77.11 6802.89   76.91 6837.27   77.03
 6915.47   77.31 6932.53   76.96 6958.77   76.41 6967.17   76.44 7003.46   76.56
 7045.12   76.69 7123.06   76.95 7128.34   76.97 7278.94   77.47  7322.5   77.61
 7331.16   77.11 7547.15   76.91 7582.05    77.4 7582.83   77.41
BR U #Mann= 9
 2672.67     .99 3867.15     .08 4966.48     .04 4966.91    .015 5022.25     .04
 5032.21     .08    5435     .08 6421.84     .99 7128.34     .99
BR U Banks=4966.91,5022.25
BR D #Sta/Elev= 174
 2672.67    77.8 2698.67   77.52 2707.27   77.71 2741.97   77.03 2767.87   77.39
 2776.57   76.84 2802.57   76.35 2845.87   75.85 2897.77    76.4 2949.77   76.21
 2975.77   75.75 3001.77   75.54 3019.07   75.68 3036.37   75.58 3045.07   75.79
 3053.67   75.48 3079.67   74.99 3096.97   75.51 3131.67   75.67 3157.57   75.43
 3166.27   75.51 3218.27    75.1 3235.57   75.31 3244.17   75.24 3252.87   75.39
 3287.47   75.32 3296.17   75.66 3304.87   75.25 3322.17   75.75 3339.47   75.68
 3348.17   75.34 3356.77   75.79 3374.17   75.78 3382.77   75.94 3400.07   75.71
 3426.07   76.08 3460.77   76.01 3469.37   75.78 3484.67   76.09 3493.27   76.22
 3503.42   76.21 3504.03   76.19 3520.74   75.71 3538.06   74.11 3538.67   74.19
 3546.72   75.21 3564.04   75.61 3564.65    75.6 3590.02   75.11 3607.34   75.51
 3633.32   74.81 3650.64   74.91 3685.28   74.51 3711.87    74.7 3746.51   74.95
 3833.11   75.57 3867.15   75.81 3945.09   74.41  4032.3   74.41 4040.96   74.41
 4057.68   74.41 4066.34   73.91 4066.94   73.93 4083.66   74.61 4084.26   74.59
 4101.58   73.99 4109.64   73.71 4126.96   74.91 4257.47   74.49 4261.02   74.47
 4404.09   74.01 4456.65   73.18 4482.63   72.77 4499.35   72.51 4655.84    73.3
 4690.48   73.47 4698.53   73.51 4720.79   73.35 4725.99   73.31 4769.29   73.11
 4795.27   72.11 4858.23   73.77 4868.02   73.76 4901.96   73.73 4912.53   73.72
 4931.93   73.85 4938.94    73.9 4956.95   73.13 4957.04   73.12 4957.14   73.12
 4966.48   72.46 4966.91   72.44 4968.83   71.13 4968.93   71.06 4968.99   71.02
 4979.04   64.13 4982.76   63.49 4982.93   63.48  4994.8   62.88 4995.23   58.78
 4996.79   58.49    5000   58.38 5003.55   58.57 5004.85   58.81 5005.37   62.85
 5005.71   62.87  5005.8   62.87 5006.49   63.57 5019.99   71.08 5020.09   71.14
 5022.25   72.34 5027.71    72.8 5030.21   72.89 5030.31   72.89  5030.4    72.9
 5032.21   72.96 5032.73   72.98 5050.31   73.49  5062.7   73.52 5072.48   73.54
 5088.25   73.55 5124.36   72.61 5150.34   71.71 5167.66   72.21 5184.98   73.21
  5217.8   73.27 5244.04   73.31 5270.02   72.81 5287.08   72.89 5313.33   73.01
 5356.37   74.09 5365.29   74.31 5408.59   73.51    5435   74.85 5451.89   75.71
 5494.93   75.76 6040.79   76.41 6136.05   75.21 6213.99   75.91 6231.05   75.32
 6239.97   75.01 6248.37   75.03 6291.67   75.16    6309   75.21 6309.25   75.21
 6326.58   76.01 6343.64   76.01 6361.22   76.01 6369.62   76.36 6421.84   78.51
 6430.24   78.36 6473.54   77.59  6517.1   76.81 6551.48   77.21 6569.06   77.41
 6586.12   77.37 6638.08   77.26 6707.37   77.11 6802.89   76.91 6837.27   77.03
 6915.47   77.31 6932.53   76.96 6958.77   76.41 6967.17   76.44 7003.46   76.56
 7045.12   76.69 7123.06   76.95 7128.34   76.97 7278.94   77.47  7322.5   77.61
 7331.16   77.11 7547.15   76.91 7582.05    77.4 7582.83   77.41
BR D #Mann= 9
 2672.67     .99 3867.15     .08 4966.48     .04 4966.91    .015 5022.25     .04
 5032.21     .08    5435     .08 6421.84     .99 7128.34     .99
BR D Banks=4966.91,5022.25
BC Design=,, 0 ,, 0 ,,,,,,
BC HTab HWMax=78.51

Type RM Length L Ch R = 1 ,14289.1 ,106.9,284.8,340.4
BEGIN DESCRIPTION:
BINGLE RD - XS 2
END DESCRIPTION:
XS GIS Cut Line= 6
      3078445.14      13865586.8      3079225.53     13864974.63
      3079511.71      13863612.3      3079143.57     13863132.52
 3079086.738267113860526.2396098      3079085.95     13860490.09
#Sta/Elev= 30
2672.672    77.83079.672   74.993503.422   76.21 3538.06   74.11 3564.04   75.61
3685.282   74.513867.152   75.814499.351   72.514698.532   73.514795.272   72.11
4938.942    73.94966.482   72.464966.912   72.444979.042   64.134994.802   62.88
4995.231   58.78    5000   58.385004.852   58.815005.372   62.855022.249   72.34
 5032.21   72.965088.252   73.555150.342   71.715435.001   74.856040.792   76.41
6309.252   75.216421.842   78.516517.101   76.817128.342   76.97 7582.83   77.41
#Mann= 9 ,-1 , 0
2672.672     .99       03867.152     .08       04966.482     .04       0
4966.912    .015       05022.249     .04       0 5032.21     .08       0
5435.001     .08       06421.842     .99       07128.342     .99       0
#XS Ineff= 4 ,-1
 4394.87 4956.87    73.7 5029.87 5494.87    73.7    6039 7669.87    76.7
 2669.87    3859    76.7
Permanent Ineff=
       F       F       F       F
Bank Sta=4966.912,5022.249
XS Rating Curve= 0
Skew Angle= 30
Exp/Cntr=.5,.3

Type RM Length L Ch R = 1 ,14004.3 ,387.8,668,1204
BEGIN DESCRIPTION:
BINGLE RD - XS 1
Interplotated channel, LIDAR overbanks
END DESCRIPTION:
XS GIS Cut Line= 6
      3078498.11     13865549.08      3079377.26     13864772.55
      3079619.35     13863620.11      3079596.58     13863362.01
      3079446.21     13863136.14      3079406.44     13860478.31
#Sta/Elev= 30
  2437.7   77.46  2637.7   75.97  3147.7   76.16  3419.7   74.32  3830.4   75.85
  4290.4   72.56  4500.4   73.83  4670.4   71.85  4730.4   73.65  4951.9   73.32
  4968.4   72.36  4989.7   62.98  4990.6   58.75  4999.7   58.16  5009.2   58.88
    5010   63.02  5030.8   72.23    5045  72.607    5146   72.85    5186   74.47
  5357.3   76.89  5537.3   73.56    5887  77.185  6517.3    77.2  6787.3   74.83
  6837.3   76.79  7147.3   76.24  7197.3   77.92  7237.3   76.62  8015.4   77.54
#Mann= 9 ,-1 , 0
  2437.7     .99       0  3830.4     .08       0  4951.9     .04       0
  4968.4    .015       0  5030.8     .04       0    5045     .08       0
  5537.3     .05       0    5887     .08       0  6517.3     .99       0
Bank Sta=4968.4,5030.8
XS Rating Curve= 0
Exp/Cntr=.3,.1

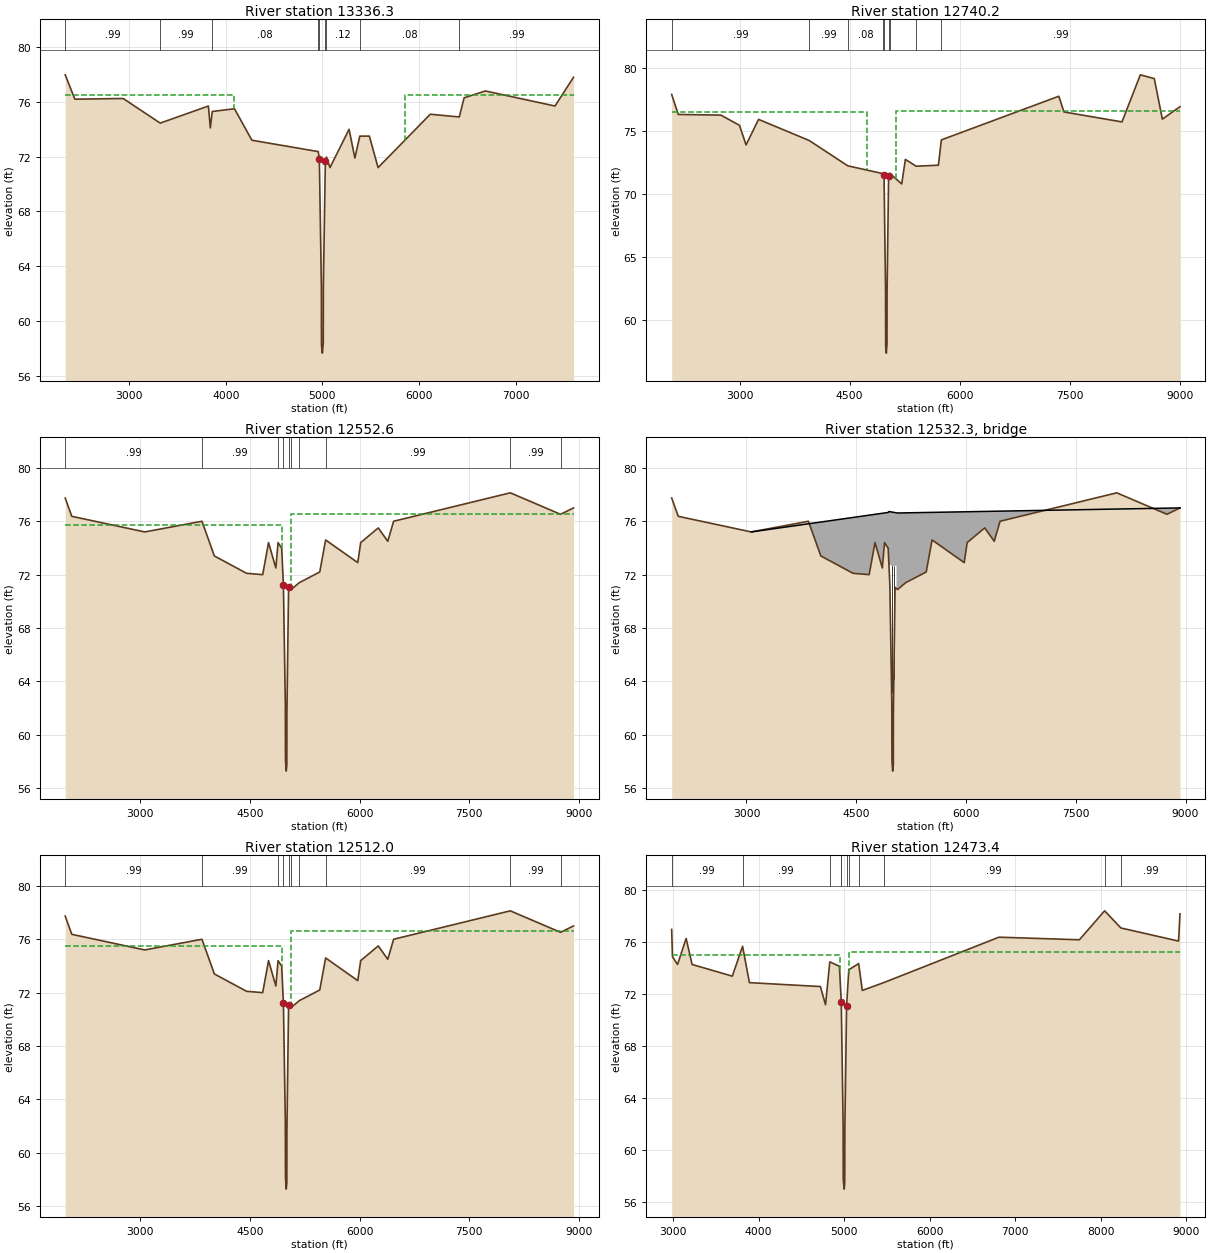
Type RM Length L Ch R = 1 ,13336.3 ,315.4,596.1,748.3
BEGIN DESCRIPTION:
Cross Section x10
Located At: U/S SOUTHERN PACIFIC RR
END DESCRIPTION:
XS GIS Cut Line= 5
      3078563.67      13865499.8       3079280.9     13864951.56
      3080142.47     13863704.13      3080307.34     13863213.56
      3081615.41     13861295.23
#Sta/Elev= 30
  2339.6   77.98  2439.6    76.2  2939.6   76.25  3322.4   74.45  3820.7    75.7
  3840.7    74.1  3860.7    75.3  4090.7    75.5  4270.7    73.2    4957   72.37
  4968.4   71.84  4989.7   62.46  4990.6   58.23  4999.7   57.64  5009.2   58.36
    5010    62.5  5030.8   71.71  5042.4   71.97  5078.5    71.2    5276      74
    5336    71.9    5387    73.5    5486    73.5    5576    71.2    6116    75.1
    6416    74.9    6466    76.3    6686    76.8    7406    75.7  7597.8    77.8
#Mann= 9 ,-1 , 0
  2339.6     .99       0  3322.4     .99       0  3860.7     .08       0
    4957     .04       0  4968.4    .015       0  5030.8     .04       0
  5042.4     .12       0    5387     .08       0    6416     .99       0
#XS Ineff= 2 , 0
       0    4085    76.5    5850       0    76.5
Permanent Ineff=
       F       F
Bank Sta=4968.4,5030.8
XS Rating Curve= 0
Exp/Cntr=.3,.1

Type RM Length L Ch R = 1 ,12740.2 ,83.2,187.6,201.6
BEGIN DESCRIPTION:
SP RR (1) - XS 4
Interplotated channel, LIDAR overbanks
END DESCRIPTION:
XS GIS Cut Line= 6
      3078568.29     13865496.69      3079296.05     13864944.68
      3079562.16     13864657.47      3080786.31     13863706.67
      3080786.11     13863548.59      3083884.13     13861162.54
#Sta/Elev= 30
  2076.2   77.92  2166.2   76.33  2746.2   76.28  2999.6   75.47  3089.6   73.91
  3259.6   75.94    3950   74.26    4475   72.25    4955   71.63  4968.4   71.57
  4968.5   71.53  4989.7   62.19  4990.6   57.96  4999.7   57.37  5009.2   58.09
    5010   62.23  5030.8   71.44    5045   71.66  5209.3   70.81  5259.3   72.76
 5406.75   72.22  5709.3    72.3  5749.3   74.31  7349.3   77.78  7419.3   76.53
  8209.3   75.74  8459.3   79.48  8649.3   79.18  8759.3   75.96  8999.6   76.95
#Mann= 9 ,-1 , 0
  2076.2     .99       0    3950     .99       0    4475     .08       0
    4955     .04       0  4968.4    .015       0  5030.8     .04       0
    5045     .05       0 5406.75     .99       0  5749.3     .99       0
#XS Ineff= 2 , 0
       0    4737    76.5  5135.5       0   76.62
Permanent Ineff=
       F       F
Bank Sta=4968.5,5030.8
XS Rating Curve= 0
Exp/Cntr=.5,.3

Type RM Length L Ch R = 1 ,12552.6 ,44.1,40.6,37.6
BEGIN DESCRIPTION:
SP RR (1) - XS 3  ***see notes***
Structure Skewed 33 degrees
END DESCRIPTION:
XS GIS Cut Line= 5
      3078572.66      13865493.7      3079465.04     13864826.45
      3081410.53     13863315.39      3084050.06     13861254.29
      3084065.35      13861242.3
#Sta/Elev= 30
  1978.1   77.74  2068.1   76.37  3065.1    75.2  3846.5      76  4016.5    73.4
  4456.5    72.1  4676.5      72  4756.5    74.4  4856.5    72.5  4886.5    74.4
  4936.4   73.98  4959.7   71.21    4986   62.32    4988   58.09    4998   57.28
  5006.9   57.76  5007.7   61.69  5030.5   71.06  5064.2   70.88  5176.5    71.4
  5456.5    72.2  5536.5    74.6  5975.7    72.9  6015.7    74.4  6255.7    75.5
  6385.7    74.5  6465.7      76    8060   78.13  8746.6   76.52    8924      77
#Mann= 10 ,-1 , 0
  1978.1     .99       0  3846.5     .99       0  4886.5     .04       0
  4959.7    .015       0  5030.5     .04       0  5064.2     .08       0
  5176.5     .99       0  5536.5     .99       0    8060     .99       0
  8746.6     .99       0
#XS Ineff= 2 , 0
       0    4937    75.7  5060.5       0   76.52
Permanent Ineff=
       F       F
Bank Sta=4959.7,5030.5
XS Rating Curve= 0
Exp/Cntr=.5,.3

Type RM Length L Ch R = 3 ,12532.3 ,,,
BEGIN DESCRIPTION:
SOUTHERN PACIFIC RR  ***see notes***
Structure ID: E115-00-00-10
Structure Skewed 33 degrees
END DESCRIPTION:
Bridge Culvert--1,0,-1,-1, 0
Deck Dist Width WeirC Skew NumUp NumDn MinLoCord MaxHiCord MaxSubmerge Is_Ogee
10,17,2.6,0, 10, 10, , , .95, 0, ,,,
  3065.1  4936.4 4947.59  4947.7 4947.81  5049.8 5049.91  5064.2  5070.8    8924
    75.2   76.66   76.73   76.73   76.73   76.63   76.63   76.62   76.62      77
                                   72.73   72.63
  3065.1  4936.4 4947.59  4947.7 4947.81  5049.8 5049.91  5064.2  5070.8    8924
    75.2   76.66   76.73   76.73   76.73   76.63   76.63   76.62   76.62      77
                                   72.73   72.63
Pier Skew, UpSta & Num, DnSta & Num=  ,4983.7, 2 ,4983.7, 2 , 0 , 0 , 0 ,,
     2.5     2.5
   61.64   73.66
     2.5     2.5
   61.56   73.59
Pier Skew, UpSta & Num, DnSta & Num=  ,5013.8, 2 ,5013.8, 2 , 0 , 0 , 0 ,,
     2.5     2.5
   62.46   73.65
     2.5     2.5
   62.39   73.58
BR Coef= 1 , 1 , 1 ,1.05, 0 ,,,.8,0,1.2,0,
WSPro=,,,, 1 ,,,, 0 ,,,, 0 ,,,,-1 ,-1 ,-1 , 0 , 0 , 0 , 0 , 0
BC Design=,, 0 ,, 0 ,,,,,,
BC HTab HWMax=78.4

Type RM Length L Ch R = 1 ,12512.0 ,31.1,38.6,31.9
BEGIN DESCRIPTION:
SP RR (1) - XS 2  *** see notes***
Structure Skewed 33 degrees
END DESCRIPTION:
XS GIS Cut Line= 4
      3078591.11      13865523.6      3079494.76     13864849.84
      3081434.84     13863342.97       3084074.4     13861281.85
#Sta/Elev= 30
  1978.1   77.74  2068.1   76.37  3065.1    75.2  3846.5      76  4016.5    73.4
  4456.5    72.1  4676.5      72  4756.5    74.4  4856.5    72.5  4886.5    74.4
  4936.4   73.98  4959.7   71.21    4986   62.32    4988   58.09    4998   57.28
  5006.9   57.76  5007.7   61.69  5030.5   71.06  5064.2   70.88  5176.5    71.4
  5456.5    72.2  5536.5    74.6  5975.7    72.9  6015.7    74.4  6255.7    75.5
  6385.7    74.5  6465.7      76    8060   78.13  8746.6   76.52    8924      77
#Mann= 10 ,-1 , 0
  1978.1     .99       0  3846.5     .99       0  4886.5     .04       0
  4959.7    .015       0  5030.5     .04       0  5064.2     .08       0
  5176.5     .99       0  5536.5     .99       0    8060     .99       0
  8746.6     .99       0
#XS Ineff= 2 , 0
       0    4937   75.48  5060.5       0    76.6
Permanent Ineff=
       F       F
Bank Sta=4959.7,5030.5
XS Rating Curve= 0
Exp/Cntr=.5,.3

Type RM Length L Ch R = 1 ,12473.4 ,106.4,86,89.7
BEGIN DESCRIPTION:
HEMPSTEAD - XS 3
END DESCRIPTION:
XS GIS Cut Line= 3
      3079443.16     13864916.88      3081437.88     13863380.27
      3084131.07     13861305.19
#Sta/Elev= 30
  2983.7   76.96  2992.7   74.86  3052.7   74.26  3152.7   76.26  3222.7   74.26
  3692.7   73.36  3812.7   75.66  3892.7   72.86  4722.7   72.56  4782.7   71.16
  4832.7   74.46  4945.1   74.12  4959.1   72.34  4966.8   71.36  4988.5   61.95
  4989.8   57.72  5000.6   56.96  5007.6   57.48  5008.6   61.45  5028.7   71.03
  5054.9   73.85    5170   74.33  5212.7   72.26  5462.7   72.86  6810.6   76.36
  7750.6   76.16  8046.1   78.39  8236.3   77.07  8910.5   76.06  8927.4   78.16
#Mann= 11 ,-1 , 0
  2983.7     .99       0  3812.7     .99       0  4832.7     .08       0
  4959.1     .04       0  4966.8    .015       0  5028.7     .04       0
  5054.9     .08       0    5170     .99       0  5462.7     .99       0
  8046.1     .99       0  8236.3     .99       0
#XS Ineff= 2 , 0
       0    4949      75    5052       0   75.25
Permanent Ineff=
       F       F
Bank Sta=4966.8,5028.7
XS Rating Curve= 0
Exp/Cntr=.5,.3