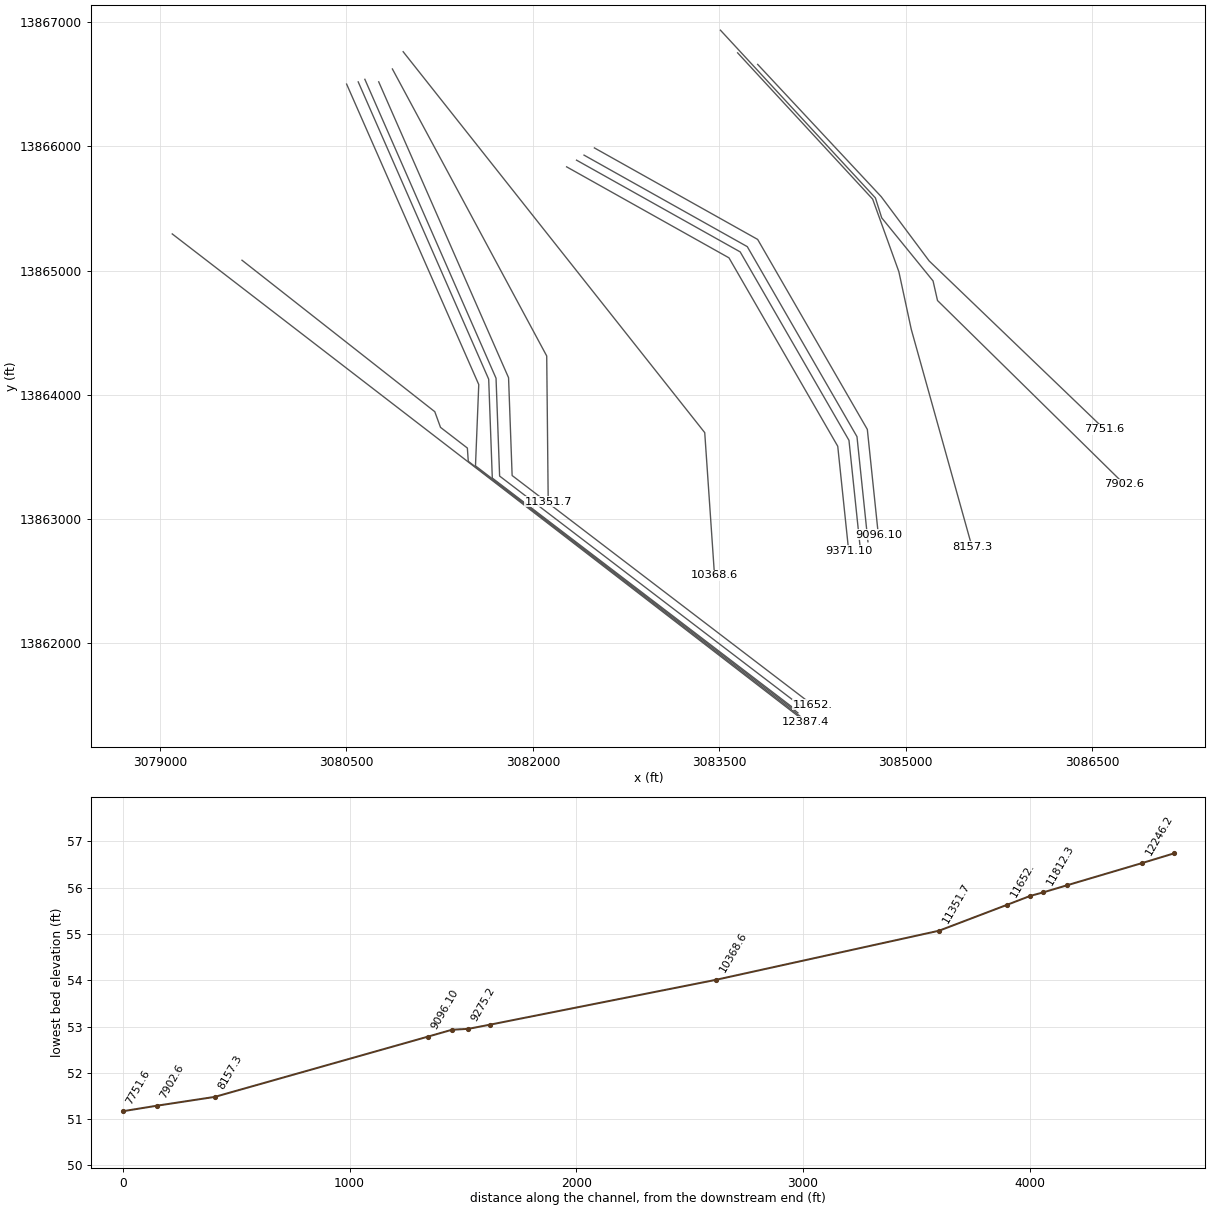
HEC-RAS study E115-00-00.prj: E115-00-00

--- E115-00-00.g01 (geometry) --- (continued)

Type RM Length L Ch R = 3 ,12430.4 ,,,
BEGIN DESCRIPTION:
HEMPSTEAD ROAD
Structure ID: E115-00-00-09
END DESCRIPTION:
Bridge Culvert--1,0,-1,-1, 0
Deck Dist Width WeirC Skew NumUp NumDn MinLoCord MaxHiCord MaxSubmerge Is_Ogee
10,66,2.6,0, 116, 117, , , .95, 0, ,,,
  2983.7  2992.7  3052.7  3112.7  3152.7  3222.7  3322.7  3332.7  3472.7  3482.7
  3542.7  3562.7  3692.7  3702.7  3712.7  3732.7  3752.7  3812.7  3832.7  3842.7
  3862.7  3892.7  3932.7  4132.7  4152.7  4282.7  4302.7  4332.7  4362.7  4382.7
  4402.7  4412.7  4432.7  4452.7  4512.7  4632.7  4672.7  4682.7  4722.7  4752.7
  4762.7  4782.7  4802.7  4812.7  4822.7  4832.7 4834.29  4834.4 4834.51  4846.2
  4895.2  4945.1 4958.91 4959.03  4959.1  4966.8  5040.5 5041.87 5041.99  5042.1
  5048.4  5054.3  5054.9 5078.39  5078.5 5078.61  5119.5  5124.8    5170  5192.7
  5212.7  5242.7  5302.7  5312.7  5322.7  5402.7  5422.7  5432.7  5462.7  5890.6
  5900.6  6080.6  6170.6  6660.6  6723.7  6810.6  6940.6  7000.6  7310.6  7320.6
  7340.6  7580.6  7590.6  7630.6  7640.6  7680.6  7710.6  7750.6  7760.6  7770.6
  7910.6  7970.6  7980.6  8000.6  8046.1  8100.6  8140.6  8230.6  8236.3  8400.6
  8550.6  8570.6  8640.6  8650.6  8910.5  8927.4
    76.9   76.89   76.83   76.77   76.72   76.65   76.55   76.54   76.39   76.38
   76.32    76.3   76.16   76.15   76.14   76.12    76.1   76.04   76.02   76.01
   75.99   75.96   75.92   75.71   75.69   75.55   75.53    75.5   75.47   75.45
   75.43   75.42    75.4   75.38   75.31   75.19   75.15   75.14    75.1   75.06
   75.05   75.03   75.01      75   74.99   74.98   74.98   76.08   76.08   76.09
   76.15    76.2   76.22   76.22   76.22   76.23   76.31   76.31   76.31   76.31
   76.32   76.33   76.33   76.35   76.35   75.25   75.27   75.28   75.35   75.39
   75.42   75.47   75.57   75.59    75.6   75.73   75.77   75.78   75.83   76.53
   76.55   76.85   76.99    77.8    77.9   77.91   77.92   77.93   77.95   77.95
   77.96   77.98   77.98   77.98   77.98   77.99   77.99   77.99   77.99      78
   78.01   78.01   78.01   78.61   78.34   78.02   78.03   78.04   78.04   78.05
   78.07   78.07   78.07   78.07    78.1    78.1
                                                                                
                                                                                
                                                                                
                                                                                
                                                                                
                    72.3   72.29   72.32   72.33   72.41   72.41   72.41
                                                                                
                                                                                
                                                                                
                                                                                
                                                                                
                                                
    2478  2983.7  2992.7  3052.7  3112.7  3152.7  3222.7  3322.7  3332.7  3472.7
  3482.7  3542.7  3562.7  3692.7  3702.7  3712.7  3732.7  3752.7  3812.7  3832.7
  3842.7  3862.7  3892.7  3932.7  4132.7  4152.7  4282.7  4302.7  4332.7  4362.7
  4382.7  4402.7  4412.7  4432.7  4452.7  4512.7  4632.7  4672.7  4682.7  4722.7
  4752.7  4762.7  4782.7  4802.7  4812.7  4822.7  4832.7 4834.29  4834.4 4834.51
  4846.2  4895.2  4945.1 4958.91 4959.03  4959.1  4966.8  5040.5 5041.87 5041.99
  5042.1  5048.4  5054.3  5054.9 5078.39  5078.5 5078.61  5119.5  5124.8    5170
  5192.7  5212.7  5242.7  5302.7  5312.7  5322.7  5402.7  5422.7  5432.7  5462.7
  5890.6  5900.6  6080.6  6170.6  6660.6  6723.7  6810.6  6940.6  7000.6  7310.6
  7320.6  7340.6  7580.6  7590.6  7630.6  7640.6  7680.6  7710.6  7750.6  7760.6
  7770.6  7910.6  7970.6  7980.6  8000.6  8046.1  8100.6  8140.6  8230.6  8236.3
  8400.6  8550.6  8570.6  8640.6  8650.6  8910.5  8927.4
      77    76.9   76.89   76.83   76.77   76.72   76.65   76.55   76.54   76.39
   76.38   76.32    76.3   76.16   76.15   76.14   76.12    76.1   76.04   76.02
   76.01   75.99   75.96   75.92   75.71   75.69   75.55   75.53    75.5   75.47
   75.45   75.43   75.42    75.4   75.38   75.31   75.19   75.15   75.14    75.1
   75.06   75.05   75.03   75.01      75   74.99   74.98   74.98   76.08   76.08
   76.09   76.15    76.2   76.22   76.22   76.22   76.23   76.31   76.31   76.31
   76.31   76.32   76.33   76.33   76.35   76.35   75.25   75.27   75.28   75.35
   75.39   75.42   75.47   75.57   75.59    75.6   75.73   75.77   75.78   75.83
   76.53   76.55   76.85   76.99    77.8    77.9   77.91   77.92   77.93   77.95
   77.95   77.96   77.98   77.98   77.98   77.98   77.99   77.99   77.99   77.99
      78   78.01   78.01   78.01   78.61   78.34   78.02   78.03   78.04   78.04
   78.05   78.07   78.07   78.07   78.07    78.1    78.1
                                                                                
                                                                                
                                                                                
                                                                                
                                                                                
                            72.3   72.29   72.32   72.33   72.41   72.41   72.41
                                                                                
                                                                                
                                                                                
                                                                                
                                                                                
                                                        
Pier Skew, UpSta & Num, DnSta & Num=  ,4984.8, 2 ,4984.8, 2 , 0 , 0 , 0 ,,
     1.2     1.2
   61.88   73.35
     1.2     1.2
   61.74   73.21
Pier Skew, UpSta & Num, DnSta & Num=  ,5015, 2 ,5015, 2 , 0 , 0 , 0 ,,
     1.2     1.2
   63.24   73.38
     1.2     1.2
    63.1   73.24
BR Coef= 1 , 1 , 1 ,1.05, 0 ,,,.8,0,1.2,0,
WSPro=,,,, 1 ,,,, 0 ,,,, 0 ,,,,-1 ,-1 ,-1 , 0 , 0 , 0 , 0 , 0
BC Design=,, 0 ,, 0 ,,,,,,
BC HTab HWMax=78.66

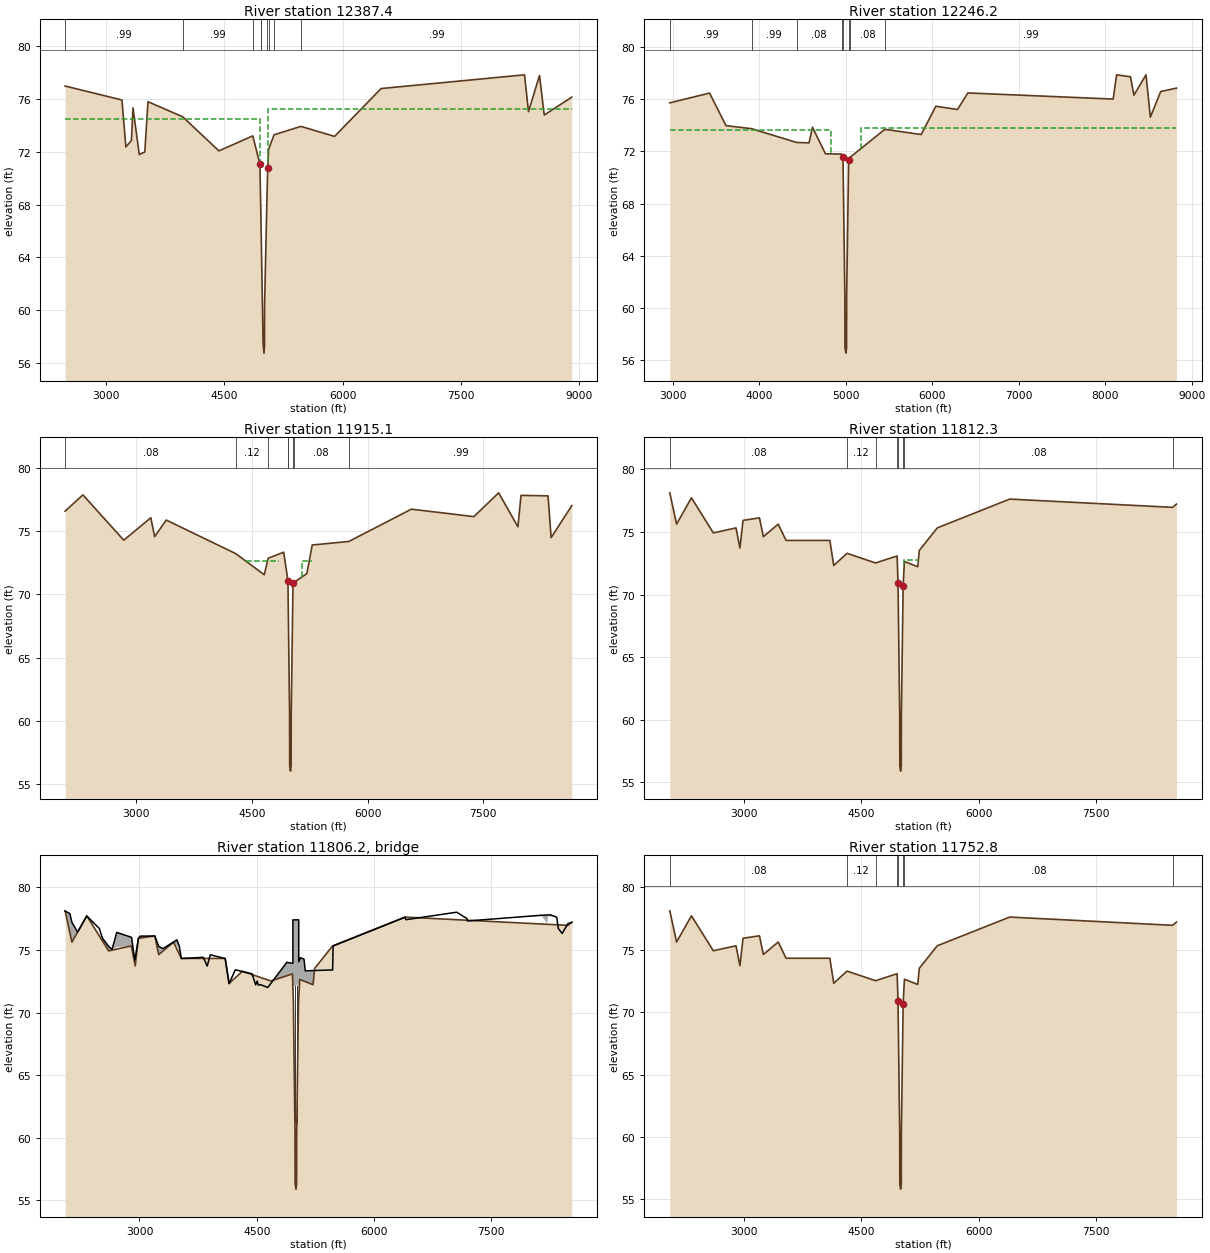
Type RM Length L Ch R = 1 ,12387.4 ,368.1,141.2,39.6
BEGIN DESCRIPTION:
HEMPSTEAD - XS 2
END DESCRIPTION:
XS GIS Cut Line= 4
 3079097.7959885 13865294.283897      3079502.61     13864982.44
      3081497.33     13863445.83      3084190.52     13861370.75
#Sta/Elev= 30
    2478      77    3199   75.94    3249   72.38    3319   72.87    3339   75.34
    3419    71.8    3489      72    3529   75.81    3969   74.67    4429   72.08
    4859   73.22    4949   71.09    4959   68.13    4969   64.66  4989.8    57.5
  5000.6   56.74  5007.6   57.26    5009   60.45    5039   68.56    5049   70.82
    5059   72.19    5129    73.3    5469   73.94  5896.9   73.18  6486.9   76.81
  8306.9   77.85  8356.9   75.06  8496.9    77.8  8556.9    74.8  8906.8   76.16
#Mann= 9 ,-1 , 0
    2478     .99       0    3969     .99       0    4859     .08       0
    4959     .04       0    4969    .015       0    5039     .04       0
    5059     .08       0    5129     .99       0    5469     .99       0
#XS Ineff= 2 , 0
       0    4949    74.5    5052       0   75.25
Permanent Ineff=
       F       F
Bank Sta=4949,5049
XS Rating Curve= 0
Exp/Cntr=.5,.3

Type RM Length L Ch R = 1 ,12246.2 ,755.6,331.1,144.2
BEGIN DESCRIPTION:
HEMPSTEAD - XS 1
Interplotated channel, LIDAR overbanks
END DESCRIPTION:
XS GIS Cut Line= 6
      3079659.23     13865082.54      3081210.52     13863863.92
      3081256.44     13863737.87      3081472.58     13863571.36
      3081479.92     13863464.73      3084154.06     13861410.22
#Sta/Elev= 30
  2965.2   75.73  3425.2   76.48  3615.2   73.98    3910   73.75  4432.5   72.69
  4575.2   72.66  4615.2   73.86  4765.2   71.82    4955    71.8  4967.9   71.57
  4989.2   60.99  4990.7   56.93  5001.3   56.53  5009.3   56.93  5010.2   60.91
  5033.2   71.35    5050   71.55  5451.8    73.7  5871.8    73.3  6041.8   75.47
  6291.8   75.22  6411.8   76.49  8091.8   76.02  8131.8   77.88  8291.8   77.73
  8331.8   76.32  8471.8   77.88  8521.8   74.63  8641.8    76.6    8824   76.86
#Mann= 8 ,-1 , 0
  2965.2     .99       0    3910     .99       0  4432.5     .08       0
    4955     .04       0  4967.9    .015       0  5033.2     .04       0
    5050     .08       0  5451.8     .99       0
#XS Ineff= 2 , 0
       0    4825   73.66    5175       0    73.8
Permanent Ineff=
       F       F
Bank Sta=4967.9,5033.2
XS Rating Curve= 0
Exp/Cntr=.3,.1

Type RM Length L Ch R = 1 ,11915.1 ,90.4,102.8,155.5
BEGIN DESCRIPTION:
LANG RD - XS 4
Interplotated channel, LIDAR overbanks
END DESCRIPTION:
XS GIS Cut Line= 4
      3080501.01     13866499.92      3081564.31     13864082.25
      3081537.89     13863427.98      3084132.37     13861440.63
#Sta/Elev= 30
  2081.4   76.58  2311.4   77.87  2841.4   74.29  3191.4   76.06  3241.4   74.57
  3391.4   75.88  4291.4   73.23  4661.4   71.56  4711.4   72.86  4912.6   73.34
    4965  71.218  4967.9   71.09  4989.2   60.51  4990.7   56.45  5001.3   56.05
  5009.3   56.45  5010.2   60.43  5033.2   70.87    5040  70.928  5212.6   71.65
  5282.6   73.91  5757.4   74.19  6567.4   76.74  7377.4   76.15  7697.4   78.03
  7947.4   75.35  7987.4   77.83  8337.4   77.79  8377.4   74.49  8645.5   77.02
#Mann= 8 ,-1 , 0
  2081.4     .08       0  4291.4     .12       0  4711.4     .08       0
    4965     .04       0  4967.9    .015       0  5033.2     .04       0
    5040     .08       0  5757.4     .99       0
#XS Ineff= 3 ,-1
  4431.4    4852   72.68    5147  5282.6   72.68  2081.4  3391.4   75.88
Permanent Ineff=
       F       F       F
Bank Sta=4967.9,5033.2
XS Rating Curve= 0
Exp/Cntr=.5,.3

Type RM Length L Ch R = 1 ,11812.3 ,64.9,59.5,59.4
BEGIN DESCRIPTION:
LANG RD - XS 3
END DESCRIPTION:
XS GIS Cut Line= 6
 3080594.326372813866517.6159468      3080601.71     13866500.79
      3081644.18     13864125.19      3081673.25     13863329.78
      3084099.77     13861476.76 3084114.373518913861465.6079746
#Sta/Elev= 30
  2048.9   78.12  2135.7   75.62  2325.7   77.72  2605.7   74.92  2895.7   75.32
  2945.7   73.72  2985.7   75.92  3195.7   76.12  3245.7   74.62  3435.7   75.62
  3535.7   74.32  4095.7   74.32  4145.7   72.32  4315.7   73.29  4680.2   72.52
  4956.4   73.08  4967.9   70.94  4989.2   60.36  4990.7    56.3  5001.3    55.9
  5009.3    56.3  5010.2   60.28  5033.2   70.72  5049.6   72.64    5220   72.22
    5240   73.52    5470   75.32  6395.9   77.62  8479.2   76.96    8529   77.22
#Mann= 8 ,-1 , 0
  2048.9     .08       0  4315.7     .12       0  4680.2     .08       0
  4956.4     .04       0  4967.9    .015       0  5033.2     .04       0
  5049.6     .08       0  8479.2     .99       0
#XS Ineff= 3 ,-1
  2048.9  3195.7   76.12  4095.7    4952   72.75    5047    5240   72.75
Permanent Ineff=
       F       F       F
Bank Sta=4967.9,5033.2
XS Rating Curve= 0
Exp/Cntr=.5,.3

Type RM Length L Ch R = 3 ,11806.2 ,,,
BEGIN DESCRIPTION:
LANG ROAD
Structure ID: E115-00-00-08
The is a 1 foot diameter pipeline just downstream of this structure that is not modeled because it is aligned within the bridge deck and is only a few feet away from the bridge.
END DESCRIPTION:
Bridge Culvert--1,0,-1,-1, 0
Deck Dist Width WeirC Skew NumUp NumDn MinLoCord MaxHiCord MaxSubmerge Is_Ogee
10,36,2.6,0, 60, 60, , , .95, 0, ,,,
  2048.9  2108.9  2135.7  2208.9  2325.7  2485.7  2525.7  2605.7  2648.9  2708.9
  2898.9  2938.9  2945.7  2985.7  3008.9  3195.7  3245.7  3298.9  3435.7  3478.9
  3495.7  3508.9  3535.7  3815.7  3865.7  3905.7  4095.7  4145.7  4225.7  4425.7
  4438.9  4485.7  4505.7  4518.9    4550    4640    4885    4962 4962.01  5036.7
 5036.71    5060    5104    5120    5470  5475.9  6395.9  6405.9  7055.9  7185.9
  7195.9  8145.9  8215.9  8225.9  8256.4  8335.9  8355.9  8405.9  8479.2    8529
    78.1    77.9    77.2   76.42   77.71   76.71   75.94   75.27   75.04    76.4
      76    74.2   74.38   75.91    76.1   76.11   75.28    75.1   75.63    75.8
   75.52    75.3   74.31   74.41   73.71   74.61   74.31   72.31   73.41   73.11
    73.1   72.21   72.51    72.2   72.22      72   74.01   73.92    77.4    77.4
   74.05   74.38   74.26   73.33    73.4   75.31   77.61   77.41   78.01   77.51
   77.31   77.77   77.79   77.79    77.8   77.61   76.71   76.31    77.1    77.2
    78.1    76.4    75.6   76.41    77.7    76.7    75.5    74.9   75.03   75.22
    75.2   73.92    73.7    75.9   75.95    76.1    74.6   74.88    75.6   75.31
    75.2    74.9    74.3    74.4    73.7    74.6    74.3    72.3    73.4    73.1
    72.9    72.2    72.5   72.19    71.5      71      71      71   72.12   72.25
      71      71      71      71      71    75.3    77.6    77.4      78    77.5
    77.3    77.7    77.1    77.7   77.67    77.6    76.7    76.3   76.94    77.2
  2048.9  2108.9  2135.7  2208.9  2325.7  2485.7  2525.7  2605.7  2648.9  2708.9
  2898.9  2938.9  2945.7  2985.7  3008.9  3195.7  3245.7  3298.9  3435.7  3478.9
  3495.7  3508.9  3535.7  3815.7  3865.7  3905.7  4095.7  4145.7  4225.7  4425.7
  4438.9  4485.7  4505.7  4518.9    4550    4640    4885    4962 4962.01  5036.7
 5036.71    5060    5104    5120    5470  5475.9  6395.9  6405.9  7055.9  7185.9
  7195.9  8145.9  8215.9  8225.9  8256.4  8335.9  8355.9  8405.9  8479.2    8529
    78.1    77.9    77.2   76.42   77.71   76.71   75.94   75.27   75.04    76.4
      76    74.2   74.38   75.91    76.1   76.11   75.28    75.1   75.63    75.8
   75.52    75.3   74.31   74.41   73.71   74.61   74.31   72.31   73.41   73.11
    73.1   72.21   72.51    72.2   72.22      72   74.01   73.92    77.4    77.4
   74.05   74.38   74.26   73.33    73.4   75.31   77.61   77.41   78.01   77.51
   77.31   77.77   77.79   77.79    77.8   77.61   76.71   76.31    77.1    77.2
      78    76.3    75.5   76.31    77.6    76.6    75.4    74.8   74.93   75.12
    75.1   73.82    73.6    75.8   75.85      76    74.5   74.78    75.5   75.21
    75.1    74.8    74.2    74.3    73.6    74.5    74.2    72.2    73.3      73
    72.8    72.1    72.4   72.09    71.5      71      71      71   72.12   72.25
      71      71      71      71      71    75.2    77.5    77.3    77.9    77.4
    77.2    77.6      77    77.6   77.57    77.5    76.6    76.2   76.84    77.1
Pier Skew, UpSta & Num, DnSta & Num=  ,4987.5, 2 ,4987.5, 2 , 0 , 0 , 0 ,,
     1.2     1.2
   59.82   73.15
     1.2     1.2
   59.72   73.05
Pier Skew, UpSta & Num, DnSta & Num=  ,5012.2, 2 ,5012.2, 2 , 0 , 0 , 0 ,,
     1.2     1.2
   59.89   73.22
     1.2     1.2
   59.79   73.12
BR Coef= 1 , 1 , 1 ,1.25, 0 ,,,.8,-1,2,0,
WSPro=,,,, 1 ,,,, 0 ,,,, 0 ,,,,-1 ,-1 ,-1 , 0 , 0 , 0 , 0 , 0
BR D #Sta/Elev= 147
  2048.9   78.12  2085.7   77.12  2108.9   76.42  2135.7   75.62  2208.9   76.43
  2325.7   77.72  2338.9   77.64  2418.9   77.14  2485.7   76.72  2518.9   75.72
  2525.7   75.52  2605.7   74.92  2648.9   75.05  2708.9   75.24  2735.7   75.32
  2865.7   75.22  2895.7   75.32  2898.9   75.22  2938.9   73.94  2945.7   73.72
  2985.7   75.92  3008.9   75.97  3085.7   76.12  3195.7   76.12  3245.7   74.62
  3298.9    74.9  3435.7   75.62  3478.9   75.33  3495.7   75.22  3508.9   74.92
  3535.7   74.32  3538.9   74.32  3815.7   74.42  3818.9   74.38  3838.9    74.1
  3865.7   73.72  3905.7   74.62  4038.9   74.41  4095.7   74.32  4118.9   73.39
  4145.7   72.32  4148.9   72.35  4165.7   72.52  4225.7   73.42  4315.7   73.29
  4425.7   73.12  4438.9   72.92  4485.7   72.22  4505.7   72.52  4508.9   72.45
  4518.9   72.21  4535.7   71.82  4548.9   71.88  4588.9   72.08  4638.9   72.32
    4680   72.52  4680.2   72.52  4684.1   72.52  4764.1   72.47  4884.1   72.39
  4908.1   72.38  4934.1   73.08  4936.2   73.14  4944.1   73.26  4952.4   73.39
  4954.8   73.43  4956.4   73.08 4961.99   71.84  4962.1   71.82 4962.21    71.8
 4962.41   71.75  4962.5   71.73  4962.6   71.71  4963.1   71.53  4967.9   70.86
  4987.5   61.02  4989.2   60.28  4990.7   56.22    4993   56.06  5001.3   55.82
  5007.7   56.01  5009.3   56.22  5010.2    60.2  5012.2    61.1  5033.2   70.64
  5036.1   70.97 5037.19   71.19  5037.3   71.21 5037.41   71.24 5042.39   72.24
  5042.5   72.27  5044.5   72.67  5049.6   72.64  5059.9   72.57  5064.1   72.55
  5068.5   72.52    5140   72.42    5220   72.22    5240   73.52    5450   74.52
    5470   75.32  5475.9   75.32  5496.4   75.37  5666.4    75.8  5716.4   75.92
  5736.4   75.97  5756.4   76.02  5816.4   76.17  5866.4    76.3  5876.4   76.32
  5956.4   76.52  5986.4    76.6  6046.4   76.75  6086.4   76.85  6106.4    76.9
  6146.4      77  6266.4    77.3  6286.4   77.35  6395.9   77.62  6405.9   77.42
  6486.4   77.49  6816.4    77.8  7055.9   78.02  7185.9   77.52  7195.9   77.32
  7246.4   77.34  7606.4   77.49  7846.4   77.59  7866.4    77.6  7886.4   77.61
  7906.4   77.62  8145.9   77.72  8215.9   77.12  8225.9   77.72  8256.4   77.69
  8266.4   77.68  8276.4   77.67  8286.4   77.66  8306.4   77.65  8335.9   77.62
  8355.9   76.72  8405.9   76.32  8426.4    76.5  8456.4   76.76  8479.2   76.96
  8485.9   77.02    8529   77.22
BR D #Mann= 8
  2048.9     .08  4315.7     .12  4680.2     .08  4956.4     .04  4967.9    .015
  5033.2     .04  5049.6     .08  8479.2     .99
BC Design=,, 0 ,, 0 ,,,,,,
BC HTab HWMax=78.12

Type RM Length L Ch R = 1 ,11752.8 ,110,100.8,100.9
BEGIN DESCRIPTION:
LANG RD - XS 2
END DESCRIPTION:
XS GIS Cut Line= 6
 3080647.7845944 13866538.324843      3080658.56     13866513.77
      3081703.34     13864132.94       3081732.1     13863345.96
      3084147.36     13861501.53 3084168.671568513861485.2552734
#Sta/Elev= 30
  2048.9   78.12  2135.7   75.62  2325.7   77.72  2605.7   74.92  2895.7   75.32
  2945.7   73.72  2985.7   75.92  3195.7   76.12  3245.7   74.62  3435.7   75.62
  3535.7   74.32  4095.7   74.32  4145.7   72.32  4315.7   73.29  4680.2   72.52
  4956.4   73.08  4967.9   70.86  4989.2   60.28  4990.7   56.22  5001.3   55.82
  5009.3   56.22  5010.2    60.2  5033.2   70.64  5049.6   72.64    5220   72.22
    5240   73.52    5470   75.32  6395.9   77.62  8479.2   76.96    8529   77.22
#Mann= 8 ,-1 , 0
  2048.9     .08       0  4315.7     .12       0  4680.2     .08       0
  4956.4     .04       0  4967.9    .015       0  5033.2     .04       0
  5049.6     .08       0  8479.2     .99       0
#XS Ineff= 2 , 0
       0    4952      72    5047       0      72
Permanent Ineff=
       F       F
Bank Sta=4967.9,5033.2
XS Rating Curve= 0
Exp/Cntr=.5,.3

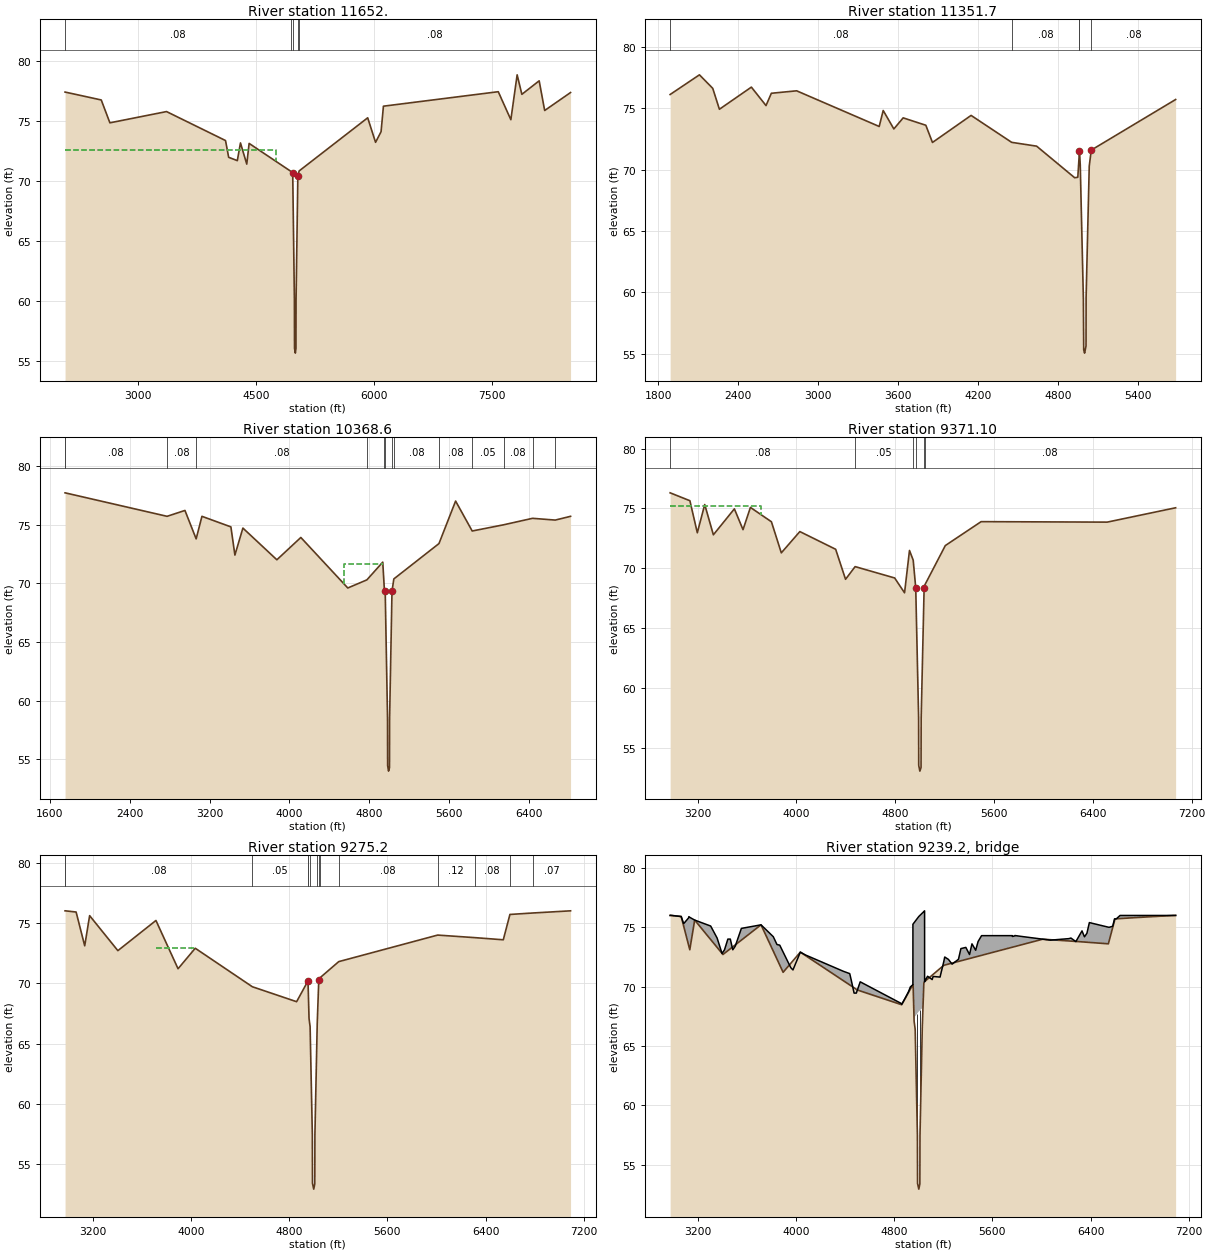
Type RM Length L Ch R = 1 ,11652.  ,339.7,300.3,298.7
BEGIN DESCRIPTION:
LANG RD - XS 1
Interplotated channel, LIDAR overbanks
END DESCRIPTION:
XS GIS Cut Line= 4
      3080759.26     13866518.12      3081804.03     13864137.28
      3081832.79      13863350.3      3084248.05     13861505.87
#Sta/Elev= 30
  2073.6   77.44  2533.6   76.78  2643.6   74.87  3363.6   75.81  4113.6   73.39
  4153.6   71.99  4263.6   71.71  4303.6   73.19  4383.6   71.42  4413.6   73.15
    4950  70.792  4967.9   70.67  4989.2   60.09  4990.7   56.03  5001.3   55.63
  5009.3   56.03  5010.2   60.01  5033.2   70.45    5050  70.853  5921.1   75.29
  6021.1   73.24  6091.1   74.13  6121.1   76.26  7581.1   77.47  7741.1   75.13
  7821.1   78.88  7881.1   77.25  8101.1   78.38  8171.1    75.9  8500.1    77.4
#Mann= 5 ,-1 , 0
  2073.6     .08       0    4950     .04       0  4967.9    .015       0
  5033.2     .04       0    5050     .08       0
#XS Ineff= 2 , 0
        4749.89772.60314
Permanent Ineff=
       F       F
Bank Sta=4967.9,5033.2
XS Rating Curve= 0
Exp/Cntr=.3,.1

Type RM Length L Ch R = 1 ,11351.7 ,751.3,983.1,1044.7
BEGIN DESCRIPTION:
Cross Section x09
END DESCRIPTION:
XS GIS Cut Line= 3
      3080869.34     13866621.68      3082111.06     13864312.22
  3082123.113917  13863138.35683
#Sta/Elev= 30
  1887.8    76.1  2107.8    77.7  2207.8    76.6  2257.8    74.9  2497.8    76.7
  2607.8    75.2  2647.8    76.2  2837.8    76.4  3457.8    73.5  3487.8    74.8
  3567.8    73.3  3637.8    74.2  3807.8    73.6  3857.8    72.2  4147.8    74.4
  4452.5   72.21  4639.9    71.9    4926   69.33  4949.2   69.37  4958.2    70.9
  4961.8   71.51  4967.6   70.36    4991    59.5  4993.6   55.34  5000.2   55.07
  5010.9   55.65  5011.6   59.65  5035.1   70.27  5050.3   71.58  5683.8  75.692
#Mann= 5 ,-1 , 0
  1887.8     .08       0  4452.5     .08       0  4958.2     .04       0
  4961.8    .015       0  5050.3     .08       0
#XS Ineff= 2 , 0
       0  4147.8    74.4               0
Permanent Ineff=
       F       F
Bank Sta=4961.8,5050.3
XS Rating Curve= 0
Exp/Cntr=.3,.1

Type RM Length L Ch R = 1 ,10368.6 ,997.8,997.5,960.7
BEGIN DESCRIPTION:
Cross Section x08
Located At: US BOLIN ROAD
END DESCRIPTION:
XS GIS Cut Line= 3
      3080956.02     13866760.37      3083382.57     13863695.46
      3083461.18     13862547.55
#Sta/Elev= 30
    1754    77.7  1754.1    77.7    2775    75.7  2954.1    76.2  3066.2   73.78
  3124.1    75.7  3414.1    74.8  3454.1    72.4  3534.1    74.7  3874.1      72
  4114.1    73.9  4584.1    69.6  4775.1   70.29  4934.1    71.8  4949.8   69.52
  4958.6   69.33  4981.9   58.48  4982.9   54.48  4992.1   54.01  5001.5   54.31
  5002.5   58.43  5026.5   69.32  5044.9   70.37  5496.8   73.38  5663.3      77
  5829.3   74.45  6144.8   74.98  6433.3   75.53  6660.6   75.38  6813.9    75.7
#Mann= 14 ,-1 , 0
    1754     .99       0  1754.1     .08       0    2775     .08       0
  3066.2     .08       0  4775.1     .08       0  4949.8     .04       0
  4958.6    .015       0  5026.5     .04       0  5044.9     .08       0
  5496.8     .08       0  5829.3     .05       0  6144.8     .08       0
  6433.3     .08       0  6660.6     .08       0
#XS Ineff= 2 ,-1
    3425  4114.1    73.9  4544.1  4934.1    71.6
Permanent Ineff=
       F       F
Bank Sta=4958.6,5026.5
XS Rating Curve= 0
Exp/Cntr=.3,.1

Type RM Length L Ch R = 1 ,9371.10 ,102.2,95.9,102.1
BEGIN DESCRIPTION:
BOLIN - XS 4
Interplotated channel, LIDAR overbanks
END DESCRIPTION:
XS GIS Cut Line= 4
      3082271.16     13865834.23      3083577.56     13865101.92
      3084452.82     13863585.79      3084540.54     13862746.44
#Sta/Elev= 30
  2977.8   76.31  3137.8   75.65  3197.8   72.97  3257.8   75.33  3327.8    72.8
  3497.8   74.97  3567.8   73.23  3627.8   75.09  3797.8   73.89  3877.8   71.29
  4027.8   73.07  4317.8   71.59  4397.8   69.08  4475.5   70.14  4795.5   69.19
  4875.5   67.95  4915.5   71.49  4945.5   70.68 4966.05   68.36 4989.35   57.51
 4990.35   53.51 4999.55   53.04 5008.95   53.34 5009.95   57.46 5033.95   68.35
    5040  68.614  5205.5    71.9  5495.5    73.9  6516.1   73.86    7070   75.06
#Mann= 6 ,-1 , 0
  2977.8     .08       0  4475.5     .05       0  4945.5     .04       0
 4966.05    .015       0 5033.95     .04       0    5040     .08       0
#XS Ineff= 2 ,-1
    3716 4036.07   72.91    2976    3716   75.21
Permanent Ineff=
       F       F
Bank Sta=4966.05,5033.95
XS Rating Curve= 0
Exp/Cntr=.5,.3

Type RM Length L Ch R = 1 ,9275.2  ,70.7,72,70.9
BEGIN DESCRIPTION:
BOLIN - XS 3
END DESCRIPTION:
XS GIS Cut Line= 6
 3082351.068145513865887.7940024      3082361.44     13865881.98
      3083667.84     13865149.67       3084543.1     13863633.54
      3084630.82     13862794.18 3084632.055897513862782.3541576
#Sta/Elev= 30
    2976   76.01  2978.4   76.01    3066   75.91    3136   73.11    3176   75.61
    3406   72.71    3716   75.21    3896   71.21    4036   72.91  4500.8   69.72
  4861.4   68.48  4951.8   70.16  4954.3   70.18  4962.6   67.09  4971.3   66.41
  4989.4   57.48  4990.7   53.43  5000.8   52.95  5009.4   53.39  5010.4   57.46
  5029.2   66.64    5042   70.31  5048.2   70.43  5204.3    71.8  6009.9      74
  6310.4   73.79  6544.3   73.61  6598.4   75.71  6784.6   75.83    7092   76.01
#Mann= 14 ,-1 , 0
    2976     .99       0  2978.4     .08       0  4500.8     .05       0
  4951.8     .04       0  4954.3     .04       0  4971.3    .015       0
  5029.2     .04       0    5042     .04       0  5048.2     .08       0
  5204.3     .08       0  6009.9     .12       0  6310.4     .08       0
  6598.4     .08       0  6784.6     .07       0
#XS Ineff= 4 ,-1
    3716 4036.07   72.91    4800    4952    68.5    5048    5100    68.5
    2976    3716   75.21
Permanent Ineff=
       F       F       F       F
Bank Sta=4954.3,5042
XS Rating Curve= 0
Exp/Cntr=.5,.3

Type RM Length L Ch R = 3 ,9239.2  ,,,
BEGIN DESCRIPTION:
BOLIN ROAD
Structure ID: E115-00-00-07
END DESCRIPTION:
Bridge Culvert--1,0,-1,-1, 0
Deck Dist Width WeirC Skew NumUp NumDn MinLoCord MaxHiCord MaxSubmerge Is_Ogee
10,52,2.6,0, 136, 136, , , .95, 0, ,,,
    2976  2978.4  3058.4    3066  3078.4    3086    3126  3128.4    3136    3176
    3306  3358.4    3376  3398.4    3406  3418.4    3446    3466  3478.4    3486
    3506    3556  3578.4  3598.4    3716    3816    3846  3868.4    3876    3896
  3958.4    3976  3988.4    4036  4038.4  4078.4    4386  4438.4  4451.9  4473.7
  4491.9  4500.8  4523.7  4853.7  4861.4  4891.9  4916.1  4931.1  4931.9  4941.9
  4951.8  4951.9  4952.5 4952.59  4952.7 4952.81  4954.3 4959.31  4959.4  4962.6
  4965.4  4971.3  4987.6  4989.4  4990.3  4990.4  4990.7  5000.8  5001.3  5009.4
  5009.5  5009.6  5010.4  5012.5  5029.2  5033.5  5037.6 5039.29  5039.4    5042
 5047.79  5047.9 5048.01  5048.1  5048.2  5072.1  5086.7  5109.6  5117.7  5171.9
  5173.7  5203.7  5204.3  5211.9  5223.7  5241.9  5271.9  5323.7  5343.7  5383.7
  5413.7  5433.7  5463.7  5481.9  5483.7  5511.9  5761.9  5763.7  5781.9  5783.7
  5811.9  5831.9  6009.9  6031.9  6071.9  6224.3  6239.6  6244.3  6279.6  6310.4
  6329.6  6349.6  6369.6  6389.6  6524.3  6544.3  6549.6  6579.6  6594.3  6598.4
  6599.6  6609.6  6639.6  6784.6  7068.2    7092
      76   76.01   75.92   75.91   75.54   75.31   75.79    75.9   75.84   75.61
   75.11    74.1   73.53    72.8   72.91    73.1   74.01   74.01   73.45   73.11
   73.41   74.91   74.95   74.99   75.21   74.21   73.55    73.5   73.34   72.92
    71.6   71.41   71.72   72.91    72.9   72.67    71.3    71.1    70.5   69.46
   69.46   69.72   70.41   68.61   68.51   69.08   69.56   69.97   69.98   70.07
   70.16   70.16   70.16   70.16   75.26   75.26   75.28   75.35   75.35   75.39
   75.43   75.51   75.73   75.76   75.77   75.77   75.78   75.91   75.92      76
      76      76   76.01   76.03    76.2   76.25   76.29    76.3   76.31   76.33
   76.39   76.39   70.42   70.43   70.43   70.88   70.77    70.6   70.86   70.81
   70.81   72.09   72.12    72.5   72.42    72.3    71.9   72.31   73.21   73.31
   72.71   73.61   73.07   73.74   73.81    74.3    74.3   74.23   74.28   74.31
   74.27   74.24      74   73.97   73.92   74.05    74.1   74.06    73.8   74.35
    74.7    74.2    74.5    75.4   75.06   75.01      75   75.09   75.71   75.71
   75.71   75.72      76      76      76      76
                                                                                
                                                                                
                                                                                
                                                                                
                                                                                
                                                                           67.39
   67.43   67.51   67.73   67.76   67.77   67.77   67.78   67.91   67.92      68
      68      68   68.01   68.03    68.2   68.25   68.29
                                                                                
                                                                                
                                                                                
                                                                                
                                                                                
                                                
    2976  2978.4  3058.4    3066  3078.4    3086    3126  3128.4    3136    3176
    3306  3358.4    3376  3398.4    3406  3418.4    3446    3466  3478.4    3486
    3506    3556  3578.4  3598.4    3716    3816    3846  3868.4    3876    3896
  3958.4    3976  3988.4    4036  4038.4  4078.4    4386  4438.4  4451.9  4473.7
  4491.9  4500.8  4523.7  4853.7  4861.4  4891.9  4916.1  4931.1  4931.9  4941.9
  4951.8  4951.9  4952.5 4952.59  4952.7 4952.81  4954.3 4959.31  4959.4  4962.6
  4965.4  4971.3  4987.6  4989.4  4990.3  4990.4  4990.7  5000.8  5001.3  5009.4
  5009.5  5009.6  5010.4  5012.5  5029.2  5033.5  5037.6 5039.29  5039.4    5042
 5047.79  5047.9 5048.01  5048.1  5048.2  5072.1  5086.7  5109.6  5117.7  5171.9
  5173.7  5203.7  5204.3  5211.9  5223.7  5241.9  5271.9  5323.7  5343.7  5383.7
  5413.7  5433.7  5463.7  5481.9  5483.7  5511.9  5761.9  5763.7  5781.9  5783.7
  5811.9  5831.9  6009.9  6031.9  6071.9  6224.3  6239.6  6244.3  6279.6  6310.4
  6329.6  6349.6  6369.6  6389.6  6524.3  6544.3  6549.6  6579.6  6594.3  6598.4
  6599.6  6609.6  6639.6  6784.6  7068.2    7092
      76   76.01   75.92   75.91   75.54   75.31   75.79    75.9   75.84   75.61
   75.11    74.1   73.53    72.8   72.91    73.1   74.01   74.01   73.45   73.11
   73.41   74.91   74.95   74.99   75.21   74.21   73.55    73.5   73.34   72.92
    71.6   71.41   71.72   72.91    72.9   72.67    71.3    71.1    70.5   69.46
   69.46   69.72   70.41   68.61   68.51   69.08   69.56   69.97   69.98   70.07
   70.16   70.16   70.16   70.16   75.26   75.26   75.28   75.35   75.35   75.39
   75.43   75.51   75.73   75.76   75.77   75.77   75.78   75.91   75.92      76
      76      76   76.01   76.03    76.2   76.25   76.29    76.3   76.31   76.33
   76.39   76.39   70.42   70.43   70.43   70.88   70.77    70.6   70.86   70.81
   70.81   72.09   72.12    72.5   72.42    72.3    71.9   72.31   73.21   73.31
   72.71   73.61   73.07   73.74   73.81    74.3    74.3   74.23   74.28   74.31
   74.27   74.24      74   73.97   73.92   74.05    74.1   74.06    73.8   74.35
    74.7    74.2    74.5    75.4   75.06   75.01      75   75.09   75.71   75.71
   75.71   75.72      76      76      76      76
                                                                                
                                                                                
                                                                                
                                                                                
                                                                                
                                                                           67.39
   67.43   67.51   67.73   67.76   67.77   67.77   67.78   67.91   67.92      68
      68      68   68.01   68.03    68.2   68.25   68.29
                                                                                
                                                                                
                                                                                
                                                                                
                                                                                
                                                
Pier Skew, UpSta & Num, DnSta & Num=  ,4987.6, 2 ,4987.6, 2 , 0 , 0 , 0 ,,
     1.2     1.2
   57.04   68.74
     1.2     1.2
   57.04   68.74
Pier Skew, UpSta & Num, DnSta & Num=  ,5012.5, 2 ,5012.5, 2 , 0 , 0 , 0 ,,
     1.2     1.2
   57.21   69.04
     1.2     1.2
   57.21   69.04
BR Coef= 1 , 1 , 1 ,1.25, 0 ,,,.8,-1,2,0,
WSPro=,,,, 1 ,,,, 0 ,,,, 0 ,,,,-1 ,-1 ,-1 , 0 , 0 , 0 , 0 , 0
BC Design=,, 0 ,, 0 ,,,,,,
BC HTab HWMax=76.01

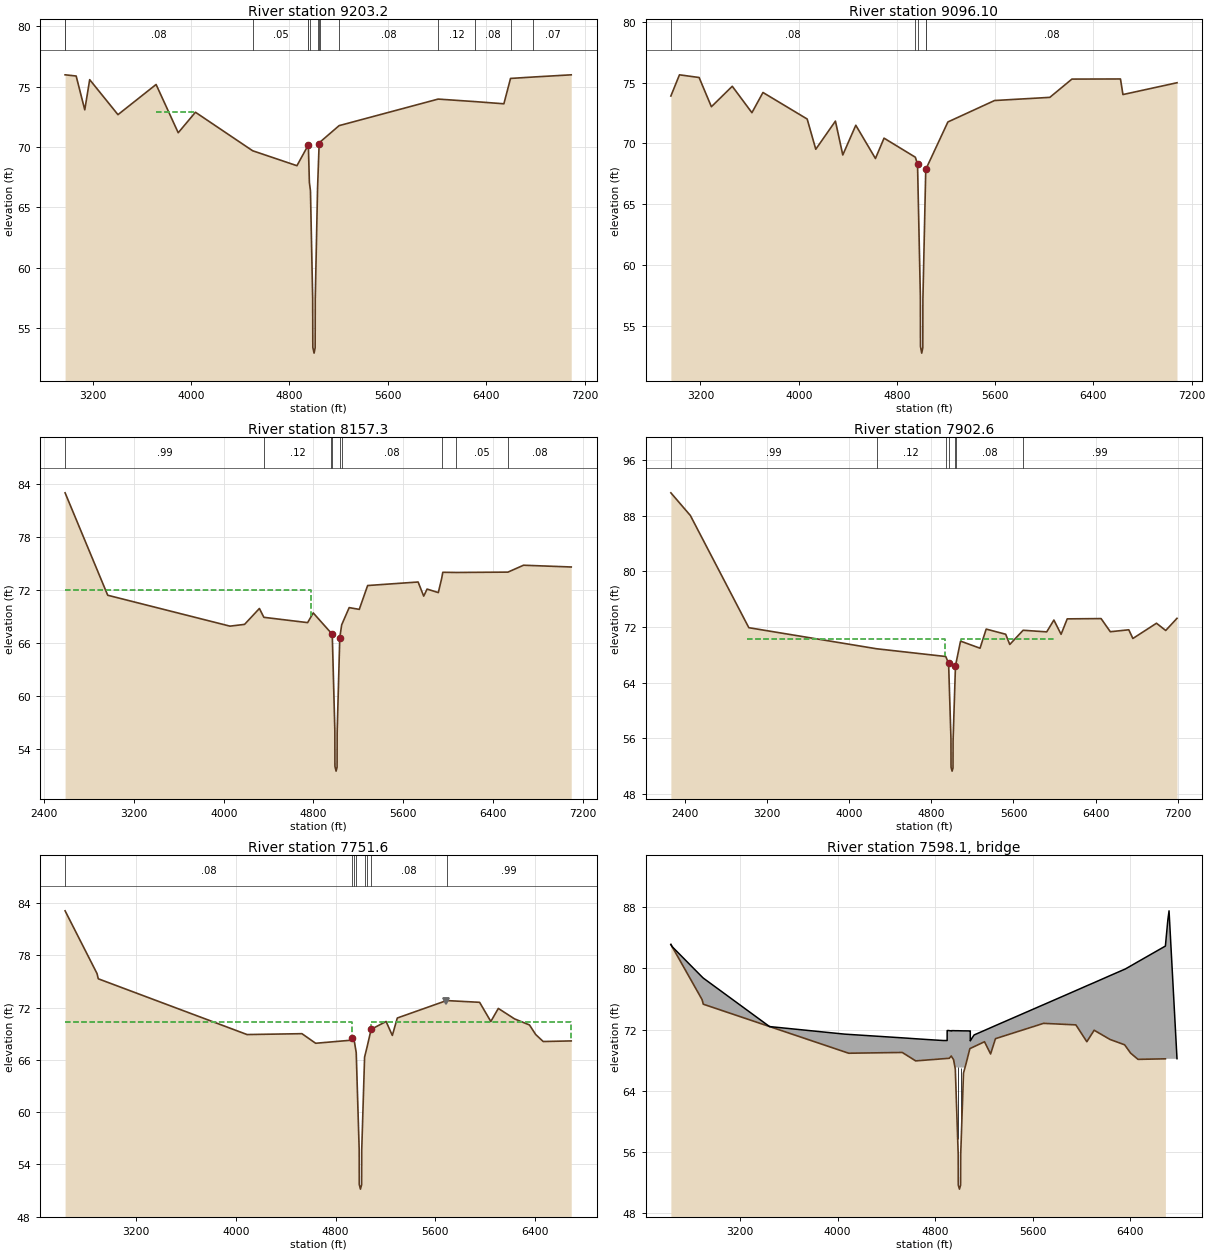
Type RM Length L Ch R = 1 ,9203.2  ,101.4,107.1,101.8
BEGIN DESCRIPTION:
BOLIN - XS 2
END DESCRIPTION:
XS GIS Cut Line= 4
      3082411.37      13865928.3      3083724.96     13865191.96
      3084607.54     13863663.16      3084695.92     13862817.45
#Sta/Elev= 30
    2976   75.99  2978.4   75.99    3066   75.89    3136   73.09    3176   75.59
    3406   72.69    3716   75.19    3896   71.19    4036   72.89  4500.8    69.7
  4861.4   68.46  4951.8   70.14  4954.3   70.16  4962.6   67.07  4971.3   66.39
  4989.4   57.46  4990.7   53.41  5000.8   52.93  5009.4   53.37  5010.4   57.44
  5029.2   66.62    5042   70.29  5048.2   70.41  5204.3   71.78  6009.9   73.98
  6310.4   73.77  6544.3   73.59  6598.4   75.69  6784.6   75.81    7092   75.99
#Mann= 14 ,-1 , 0
    2976     .99       0  2978.4     .08       0  4500.8     .05       0
  4951.8     .04       0  4954.3     .04       0  4971.3    .015       0
  5029.2     .04       0    5042     .04       0  5048.2     .08       0
  5204.3     .08       0  6009.9     .12       0  6310.4     .08       0
  6598.4     .08       0  6784.6     .07       0
#XS Ineff= 4 ,-1
    3716 4036.87   72.89    4800    4952    68.5    5048    5100    68.5
    2976    3716   75.19
Permanent Ineff=
       F       F       F       F
Bank Sta=4954.3,5042
XS Rating Curve= 0
Exp/Cntr=.5,.3

Type RM Length L Ch R = 1 ,9096.10 ,973.5,938.8,900.4
BEGIN DESCRIPTION:
BOLIN - XS 1
Interplotated channel, LIDAR overbanks
END DESCRIPTION:
XS GIS Cut Line= 4
       3082494.7     13865986.45       3083808.3     13865250.12
      3084690.87     13863721.32      3084779.25     13862875.61
#Sta/Elev= 30
    2959   73.89    3029   75.63    3189   75.41    3289   73.01    3459   74.69
    3619   72.52    3709   74.18    4069      72    4139   69.52    4299   71.83
    4359   69.05  4464.9   71.49  4624.9   68.76  4694.9   70.43    4950  68.864
  4967.7   68.27  4990.7   57.42  4991.6   53.33  5001.8   52.78  5010.5   53.22
  5011.3   57.16  5034.7    67.9    5040  67.979  5214.9   71.76  5594.9   73.52
  6044.9   73.78  6224.9   75.28  6620.2   75.29  6640.2   74.01  7080.5   74.98
#Mann= 5 ,-1 , 0
    2959     .08       0    4950     .04       0  4967.7    .015       0
  5034.7     .04       0    5040     .08       0
Bank Sta=4967.7,5034.7
XS Rating Curve= 0
Exp/Cntr=.3,.1

Type RM Length L Ch R = 1 ,8157.3  ,131.1,254.7,283.6
BEGIN DESCRIPTION:
Cross Section x07
Located At: US HWY290
END DESCRIPTION:
XS GIS Cut Line= 5
 3083647.157604113866751.3981436      3084733.88     13865574.16
      3084944.57      13864990.5       3085044.4     13864526.57
       3085532.6     13862778.31
#Sta/Elev= 30
  2585.8      83  2965.8    71.4  4055.8    67.9  4185.8    68.1    4318    69.9
    4358    68.9    4748    68.3    4798    69.4  4959.3    67.1  4967.7   66.97
  4990.7   56.12  4991.6   52.03  5001.8   51.48  5010.5   51.92  5011.3   55.86
  5034.7    66.6  5051.7   68.05  5118.5      70  5208.5    69.8  5283.1    72.5
  5733.1    72.9  5783.1    71.3  5813.1    72.1  5913.1    71.7  5943.3   73.31
  5953.1      74  6073.8   73.98  6533.9   74.02  6673.1    74.8  7098.2    74.6
#Mann= 9 ,-1 , 0
  2585.8     .99       0    4358     .12       0  4959.3     .04       0
  4967.7    .015       0  5034.7     .04       0  5051.7     .08       0
  5943.3     .08       0  6073.8     .05       0  6533.9     .08       0
#XS Ineff= 2 , 0
       0    4780      72  5283.1       0    72.5
Permanent Ineff=
       F       F
Bank Sta=4967.7,5034.7
XS Rating Curve= 0
Exp/Cntr=.3,.1

Type RM Length L Ch R = 1 ,7902.6  ,592.2,151,196.1
BEGIN DESCRIPTION:
US 290 - XS 4
Interplotated channel, LIDAR overbanks
END DESCRIPTION:
XS GIS Cut Line= 6
      3083508.83      13866933.8      3084755.77     13865584.17
      3084806.65      13865423.7      3085219.74     13864915.87
      3085255.56     13864758.37 3086760.014286713863278.9541445
#Sta/Elev= 30
  2260.4    91.3  2450.4   88.04  3020.4   71.91  4266.2   68.88    4940  67.767
  4967.7   66.78  4990.7   55.93  4991.6   51.84  5001.8   51.29  5010.5   51.73
  5011.3   55.67  5034.7   66.41    5040  66.812  5084.1   69.98  5274.1   68.96
  5334.1   71.71  5524.1   70.97  5564.1    69.5  5694.1   71.54  5924.1   71.31
  5994.1   73.01  6064.1   70.96  6124.1   73.18  6454.1   73.22  6544.1   71.33
  6724.1   71.61  6764.1   70.36  6994.1   72.55  7084.1   71.51  7194.1   73.26
#Mann= 7 ,-1 , 0
  2260.4     .99       0  4266.2     .12       0    4940     .04       0
  4967.7    .015       0  5034.7     .04       0    5040     .08       0
  5694.1     .99       0
#XS Ineff= 3 ,-1
    3000    4931    70.3    5085  5994.1    70.3  5994.1  7194.1   73.01
Permanent Ineff=
       F       F       F
Bank Sta=4967.7,5034.7
XS Rating Curve= 0
Exp/Cntr=.5,.3

Type RM Length L Ch R = 1 ,7751.6  ,308.5,307,320.2
BEGIN DESCRIPTION:
US 290 - XS 3
Levee installed on the right overbank does not represent a real regulated levee.  It is placed there to contain the floodplain within high ground without having to shorten the cross section.
END DESCRIPTION:
XS GIS Cut Line= 4
 3083808.505182913866658.4401959      3084802.79     13865593.89
      3085188.39     13865076.96 3086600.351493913863721.2693924
#Sta/Elev= 30
  2631.4   83.11  2887.5   75.91  2897.5   75.31  4090.8   68.91  4530.8   69.01
  4640.8   67.91  4916.7   68.25  4932.2   68.55  4951.8   68.07  4966.1   66.84
  4989.9    55.7  4990.5    51.7  5000.1   51.17  5009.4   51.68  5010.3   55.67
  5033.2   66.32  5053.5    67.5  5085.7   69.51  5205.7   70.41  5255.7   68.81
  5295.7   70.81  5690.4   72.81  5955.7   72.61  6045.7   70.41  6105.7   71.91
  6235.7   70.71  6355.7   70.01  6405.7   68.91  6465.7   68.11  6690.4   68.18
#Mann= 8 ,-1 , 0
  2631.4     .08       0  4932.2     .08       0  4951.8     .04       0
  4966.1    .015       0  5033.2     .04       0  5053.5     .08       0
  5085.7     .08       0  5690.4     .99       0
Levee=0,,,-1,5685.68,72.81,,
#XS Ineff= 2 , 0
       0    4931    70.3    5085       0    70.3
Permanent Ineff=
       F       F
Bank Sta=4932.2,5085.7
XS Rating Curve= 0
Exp/Cntr=.5,.3

Type RM Length L Ch R = 3 ,7598.1  ,,,
BEGIN DESCRIPTION:
US ROUTE 290
Structure ID: E115-00-00-06
END DESCRIPTION:
Bridge Culvert--1,0,-1,-1, 0
Deck Dist Width WeirC Skew NumUp NumDn MinLoCord MaxHiCord MaxSubmerge Is_Ogee
10,287,2.6,0, 65, 65, , , .95, 0, ,,,
  2631.4  2641.4  2887.5  2897.5  3441.4  4060.4  4090.8  4530.8  4640.8  4735.7
  4865.5 4898.99  4899.1 4899.21  4909.8  4916.7  4932.2  4935.2  4936.2  4951.8
  4952.2 4962.81  4962.9  4966.1  4985.6  4989.9  4990.4  4990.5  5000.1  5009.3
  5009.4  5010.3  5033.2  5039.6  5044.7 5044.79  5044.9  5045.7  5053.5  5085.7
 5088.89    5089 5089.11  5089.3    5094  5120.4  5205.7  5255.7  5295.7  5535.7
  5685.7  5690.4  5955.7  6045.7  6105.7  6225.7  6235.7  6355.7  6360.4  6405.7
  6465.7  6690.4  6710.4  6720.4  6785.7
    83.1   82.83   78.87   78.72   72.39    71.4   71.37   70.92    70.8    70.7
   70.57   70.57   71.87   71.87   71.88   71.86   71.83   71.82   71.86   71.86
   71.86   71.85   71.85   71.85   71.85   71.85   71.85   71.85   71.84   71.84
   71.84   71.84   71.83   71.83   71.83   71.83   71.83   71.83   71.83   71.82
   71.82   71.82   70.52   70.53   70.67    71.3   71.89   72.24   72.52   74.18
   75.22   75.25   77.09   77.72   78.13   78.97   79.04   79.87    79.9   80.31
   80.86    82.9    86.3    87.5    68.2
                                                                                
                                                                                
                   67.11   67.05   67.05   67.05   67.05   67.05   67.04   67.04
   67.04   67.04   67.03   67.03   67.11    67.1
                                                                                
                                                                                
                                        
  2631.4  2641.4  2887.5  2897.5  3441.4  4060.4  4090.8  4530.8  4640.8  4735.7
  4865.5 4898.99  4899.1 4899.21  4909.8  4916.7  4932.2  4935.2  4936.2  4951.8
  4952.2 4962.81  4962.9  4966.1  4985.6  4989.9  4990.4  4990.5  5000.1  5009.3
  5009.4  5010.3  5033.2  5039.6  5044.7 5044.79  5044.9  5045.7  5053.5  5085.7
 5088.89    5089 5089.11  5089.3    5094  5120.4  5205.7  5255.7  5295.7  5535.7
  5685.7  5690.4  5955.7  6045.7  6105.7  6225.7  6235.7  6355.7  6360.4  6405.7
  6465.7  6690.4  6710.4  6720.4  6785.7
    83.1   82.83   78.87   78.72   72.39    71.4   71.37   70.92    70.8    70.7
   70.57   70.57   71.87   71.87   71.88   71.86   71.83   71.82   71.86   71.86
   71.86   71.85   71.85   71.85   71.85   71.85   71.85   71.85   71.84   71.84
   71.84   71.84   71.83   71.83   71.83   71.83   71.83   71.83   71.83   71.82
   71.82   71.82   70.52   70.53   70.67    71.3   71.89   72.24   72.52   74.18
   75.22   75.25   77.09   77.72   78.13   78.97   79.04   79.87    79.9   80.31
   80.86    82.9    86.3    87.5    68.2
                                                                                
                                                                                
                   67.11   67.05   67.05   67.05   67.05   67.05   67.04   67.04
   67.04   67.04   67.03   67.03   67.11    67.1
                                                                                
                                                                                
                                        
Pier Skew, UpSta & Num, DnSta & Num=  ,4985.6, 2 ,4985.6, 2 , 0 , 0 , 0 ,,
     1.4     1.4
   56.25   68.05
     1.4     1.4
   56.25   68.05
Pier Skew, UpSta & Num, DnSta & Num=  ,5015.7, 2 ,5015.7, 2 , 0 , 0 , 0 ,,
     1.3     1.3
   56.87   68.04
     1.3     1.3
   56.87   68.04
BR Coef= 1 , 1 , 1 ,1.25, 0 ,,,.8,0,2,0,
WSPro=,,,, 1 ,,,, 0 ,,,, 0 ,,,,-1 ,-1 ,-1 , 0 , 0 , 0 , 0 , 0
BC Design=,, 0 ,, 0 ,,,,,,
BC HTab HWMax=83.11