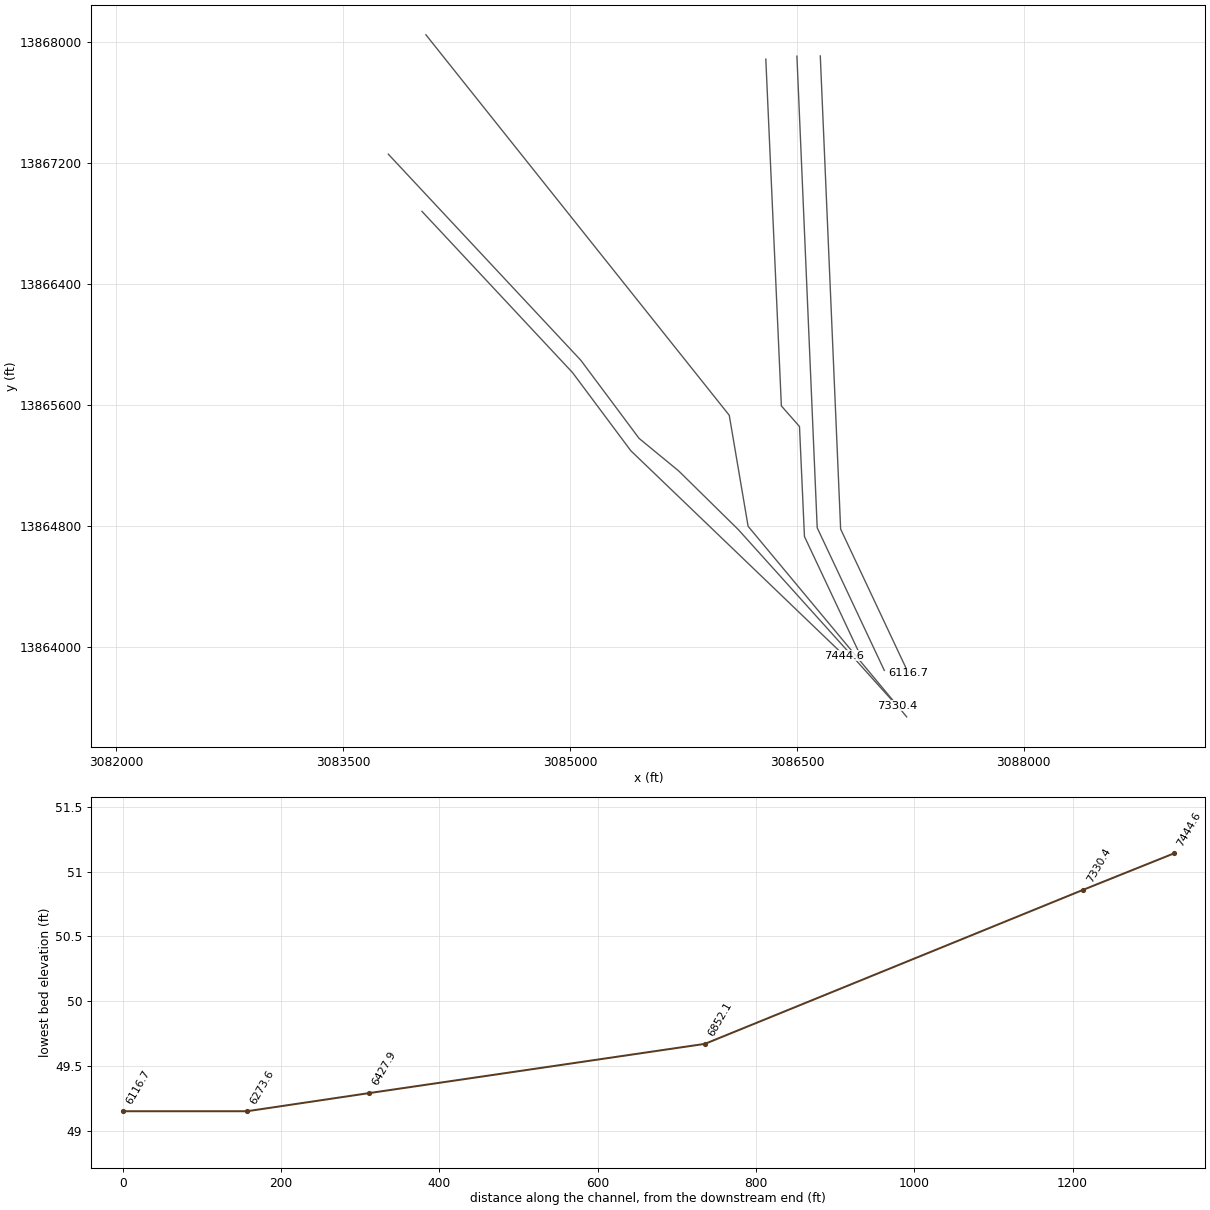
HEC-RAS study E115-00-00.prj: E115-00-00

--- E115-00-00.g01 (geometry) --- (continued)

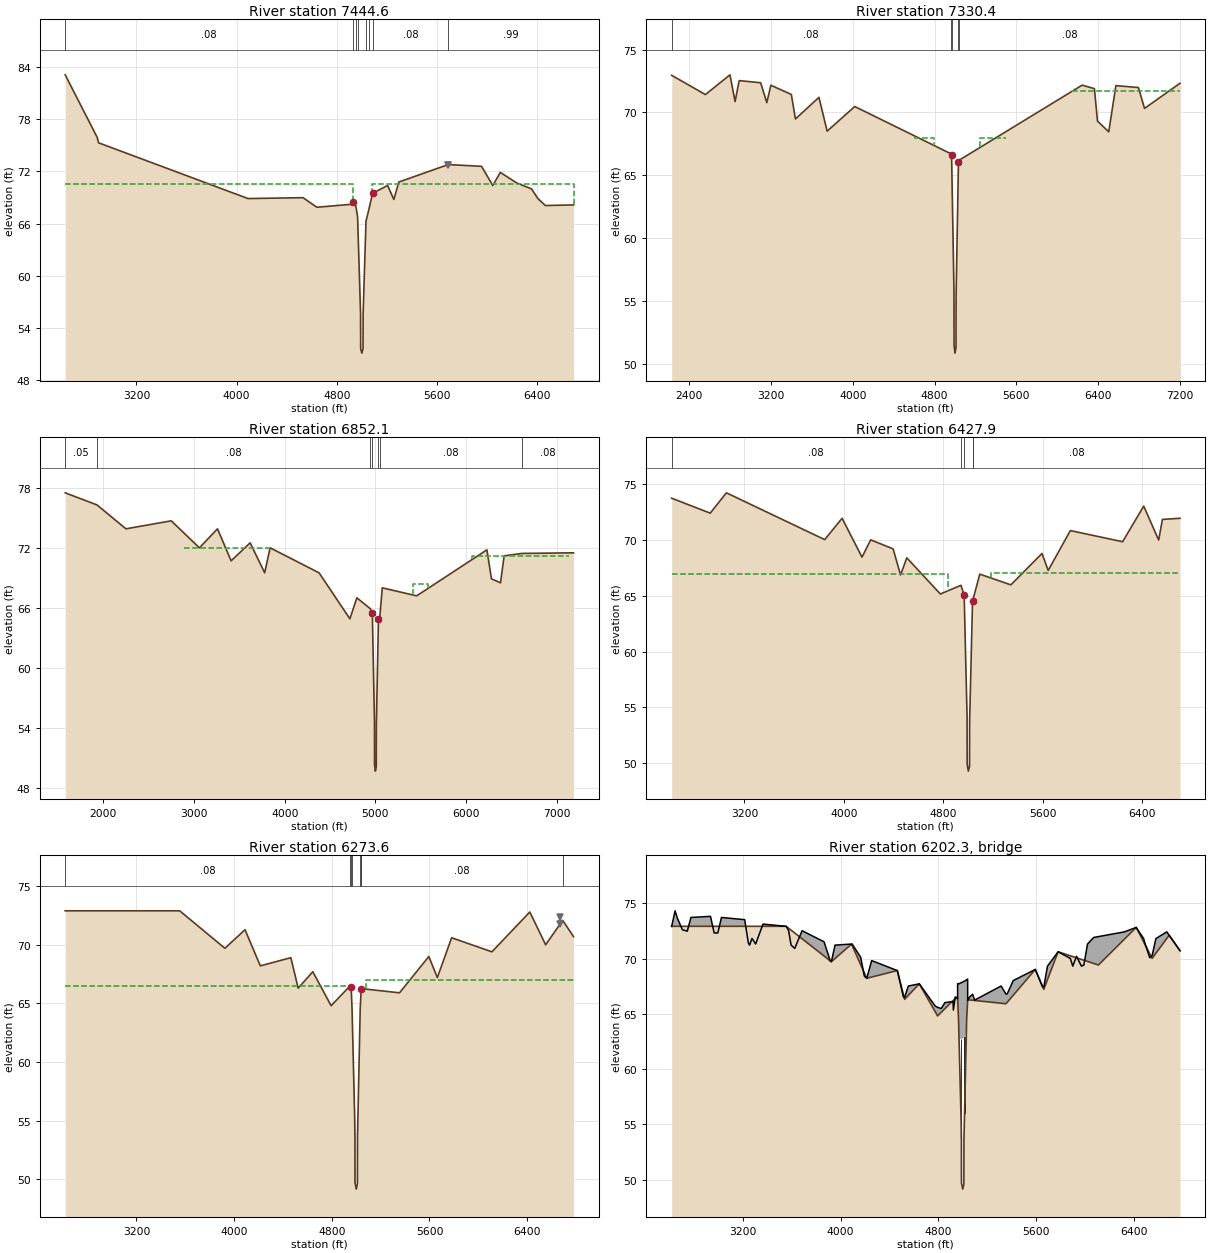
Type RM Length L Ch R = 1 ,7444.6  ,97.7,114.2,131.8
BEGIN DESCRIPTION:
US 290 - XS 2
Levee installed on the right overbank does not represent a real regulated levee.  It is placed there to contain the floodplain within high ground without having to shorten the cross section.
END DESCRIPTION:
XS GIS Cut Line= 4
 3084021.113768113866879.1489245      3085017.08     13865812.79
      3085402.19     13865296.52 3086812.963446313863941.9708397
#Sta/Elev= 30
  2631.4   83.08  2887.5   75.88  2897.5   75.28  4090.8   68.88  4530.8   68.98
  4640.8   67.88  4916.7   68.22  4932.2   68.52  4951.8   68.04  4966.1   66.81
  4989.9   55.67  4990.5   51.67  5000.1   51.14  5009.4   51.65  5010.3   55.64
  5033.2   66.29  5053.5   67.47  5085.7   69.48  5205.7   70.38  5255.7   68.78
  5295.7   70.78  5690.4   72.78  5955.7   72.58  6045.7   70.38  6105.7   71.88
  6235.7   70.68  6355.7   69.98  6405.7   68.88  6465.7   68.08  6690.4   68.15
#Mann= 8 ,-1 , 0
  2631.4     .08       0  4932.2     .08       0  4951.8     .04       0
  4966.1    .015       0  5033.2     .04       0  5053.5     .08       0
  5085.7     .08       0  5690.4     .99       0
Levee=0,,,-1,5685.63,72.78,,
#XS Ineff= 2 , 0
       0    4931   70.53    5085       0   70.53
Permanent Ineff=
       F       F
Bank Sta=4932.2,5085.7
XS Rating Curve= 0
Exp/Cntr=.5,.3

Type RM Length L Ch R = 1 ,7330.4  ,536,478.3,291.8
BEGIN DESCRIPTION:
US 290 - XS 1
Interplotated channel, LIDAR overbanks
END DESCRIPTION:
XS GIS Cut Line= 6
       3083798.8     13867257.32      3085071.76     13865894.39
      3085456.87     13865378.12      3085718.19     13865163.41
      3086113.58     13864774.32        3087162.     13863610.13
#Sta/Elev= 30
  2229.8   72.95  2559.8   71.42  2799.8   72.99  2849.8   70.86  2889.8   72.53
  3099.8   72.36  3159.8   70.78  3199.8   72.16  3399.8   71.43  3439.8   69.48
  3669.8    71.2  3749.8   68.51  4019.8   70.47    4960  66.713  4966.6   66.63
  4989.9   55.77  4990.7   51.48    5000   50.86  5009.7   51.28  5010.6   55.36
  5033.8   66.07    5040  66.199  6243.1   72.17  6363.1   71.89  6393.1   69.31
  6503.1   68.46  6573.1   72.13  6793.1   71.98  6853.1   70.32  7199.8   72.32
#Mann= 5 ,-1 , 0
  2229.8     .08       0    4960     .04       0  4966.6    .015       0
  5033.8     .04       0    5040     .08       0
#XS Ineff= 4 ,-1
    4600  4798.8   67.95  5248.4    5500   67.99  6143.1  7199.8   71.69
  3199.8  2229.8   72.16
Permanent Ineff=
       F       F       F       F
Bank Sta=4966.6,5033.8
XS Rating Curve= 0
Exp/Cntr=.3,.1

Type RM Length L Ch R = 1 ,6852.1  ,381.9,424.2,490.7
BEGIN DESCRIPTION:
Cross Section x06
Located At: US ANTOINE
END DESCRIPTION:
XS GIS Cut Line= 4
      3084047.52     13868046.46      3086052.84      13865531.1
       3086177.5     13864797.22      3087225.99     13863536.97
#Sta/Elev= 30
  1578.8    77.5  1929.5   76.29  2248.8    73.9  2748.8    74.7  3058.8      72
  3258.8    73.9  3408.8    70.7  3618.8    72.5  3778.8    69.5  3838.8      72
  4378.8    69.5  4718.8    64.9  4795.7      67  4945.7    65.9  4966.6   65.44
  4989.9   54.58  4990.7   50.29    5000   49.67  5009.7   50.09  5010.6   54.17
  5033.8   64.88  5046.2   64.75  5075.7      68  5455.7    67.2  6230.1    71.8
  6280.1    68.9  6380.1    68.5  6420.1    71.2  6616.2   71.44  7185.5    71.5
#Mann= 7 ,-1 , 0
  1578.8     .05       0  1929.5     .08       0  4945.7     .04       0
  4966.6    .015       0  5033.8     .04       0  5046.2     .08       0
  6616.2     .08       0
#XS Ineff= 4 ,-1
  2888.2 3838.51   72.03    4400  4795.7      67 5416.15 5583.85   68.39
 6068.32 7136.65   71.23
Permanent Ineff=
       F       T       F       F
Bank Sta=4966.6,5033.8
XS Rating Curve= 0
Exp/Cntr=.3,.1

Type RM Length L Ch R = 1 ,6427.9  ,218.4,154.3,99.7
BEGIN DESCRIPTION:
ANTOINE DR - XS 4
Interplotated channel, LIDAR overbanks
END DESCRIPTION:
XS GIS Cut Line= 5
       3086294.5     13867885.93      3086397.42     13865592.96
      3086517.25     13865456.75      3086550.08     13864729.43
      3086925.29     13863931.82
#Sta/Elev= 30
  2615.4   73.73  2925.4   72.39  3055.4   74.21  3845.4   70.02  3985.4   71.93
  4145.4   68.45  4215.4      70  4395.4   69.19  4455.4   66.86  4505.4   68.39
  4775.4   65.15  4940.7   65.93  4966.6   65.06  4989.9    54.2  4990.7   49.91
    5000   49.29  5009.7   49.71  5010.6   53.79  5033.8    64.5    5035  64.545
  5092.1   66.93  5342.1   65.97  5592.1   68.78  5642.1   67.26  5820.2   70.83
  6240.2   69.83  6410.2   73.02  6530.2   69.98  6560.2   71.83  6701.6   71.93
#Mann= 5 ,-1 , 0
  2615.4     .08       0  4940.7     .04       0  4966.6    .015       0
  5033.8     .04       0    5035     .08       0
#XS Ineff= 2 , 0
       0    4839    66.9    5181       0      67
Permanent Ineff=
       F       F
Bank Sta=4966.6,5033.8
XS Rating Curve= 0
Exp/Cntr=.5,.3

Type RM Length L Ch R = 1 ,6273.6  ,171.1,156.9,158.3
BEGIN DESCRIPTION:
ANTOINE DR - XS 3
END DESCRIPTION:
XS GIS Cut Line= 3
  3086500.21820513867905.2432542      3086634.36     13864787.23
 3087077.984518613863844.1585719
#Sta/Elev= 30
  2616.9   72.91  3554.8   72.91  3924.8   69.71 4089.62    71.3  4214.8   68.21
  4464.8   68.91  4524.8   66.31  4644.8   67.71  4794.8   64.81  4947.2   66.47
  4958.9   66.37  4966.1   64.52  4987.7   55.26  4989.6    53.7    4990   49.71
  5000.8   49.15 5009.91   49.62  5010.7   53.66  5033.1    64.6  5039.8   65.96
  5041.3   66.27  5354.8   65.91  5594.8   69.01  5664.8   67.21  5781.7   70.61
  6111.7   69.41  6421.7   72.81  6551.7   70.01  6691.2    72.1    6780   70.71
#Mann= 8 ,-1 , 0
  2616.9     .08       0  4947.2     .04       0  4958.9     .04       0
  4966.1    .015       0  5033.1     .04       0  5039.8     .08       0
  5041.3     .08       0  6691.2     .08       0
Levee=0,,,-1,6671.69,72.41,,
#XS Ineff= 2 , 0
       0    4939    66.5    5081       0      67
Permanent Ineff=
       T       F
Bank Sta=4958.9,5041.3
XS Rating Curve= 0
Exp/Cntr=.5,.3

Type RM Length L Ch R = 3 ,6202.3  ,,,
BEGIN DESCRIPTION:
ANTOINE DRIVE
Structure ID: E115-00-00-05
END DESCRIPTION:
Bridge Culvert--1,0,-1,-1, 0
Deck Dist Width WeirC Skew NumUp NumDn MinLoCord MaxHiCord MaxSubmerge Is_Ogee
10,135,2.6,0, 116, 116, , , .95, 0, ,,,
  2616.9  2644.8  2664.8  2704.8  2744.8  2774.8  2934.8  2964.8  2994.8  3024.8
  3214.8  3244.8  3254.8  3274.8  3304.8  3364.8  3554.8  3574.8  3594.8  3624.8
  3684.8  3864.8  3914.8  3924.8  3954.8  4094.8  4164.8  4194.8  4214.8  4254.8
  4464.8  4514.8  4524.8  4554.8  4644.8  4774.8  4794.8  4824.8  4854.8  4921.3
  4923.9  4936.9  4939.4  4946.9  4947.2  4956.9 4958.59  4958.7 4958.81  4958.9
  4966.1  4968.9 4969.81  4969.9  4987.7  4989.6    4990  4990.1 4990.21  5000.8
  5002.2  5009.7  5009.8 5009.91  5010.7  5015.5 5030.79  5030.9  5033.1  5038.2
  5039.8 5040.79  5040.9 5041.01  5041.3  5060.6  5068.7  5081.7    5098  5314.8
  5354.8  5364.8  5414.8  5594.8  5654.8  5664.8  5694.8  5742.5  5781.7  5881.7
  5882.5  5901.7  5932.5  5972.5  5992.5  6001.7  6022.5  6041.7  6072.5  6111.7
  6151.7  6241.7  6322.5  6421.7  6422.5  6482.5  6491.7  6532.5  6551.7  6552.5
  6581.7  6582.5  6671.7  6682.5  6691.2    6780
    72.9   74.31   73.61    72.6   72.47   73.71   73.81   72.31   72.31   73.71
   73.51   71.41   71.21   71.81   71.31   73.11   72.91   72.51   71.21   70.91
   72.51   71.51   69.81   69.71   71.21   71.31   70.11   68.41   68.21   69.81
   68.91   66.52   66.49   67.51   67.71   65.71   65.58   65.48   66.01   66.12
   65.34   66.34   66.53   66.47   66.47   66.39   66.37   67.72   67.72   67.72
   67.72   67.72   67.72   67.72   67.81   67.82   67.82   67.82   67.82   67.87
   67.88   67.93   67.93   67.93   67.93   67.96   68.06   68.06   68.08   68.11
   68.13   68.14   68.14   66.21   66.27   66.56   66.64   66.77   66.24   67.51
   66.78    66.8   68.01   69.01   67.42   67.44   69.31   70.02   70.61   70.01
   69.98   69.31    70.2   69.31    69.4   69.98    71.3   71.53    71.9   71.98
   72.06   72.24    72.4   72.81   72.78    71.8   71.41   70.07   70.28    70.3
   71.76    71.8   72.41   72.24    72.1    70.7
                                                                                
                                                                                
                                                                                
                                                                                
                                                                                
                   62.92   62.88   62.71   62.72   62.72   62.72   62.72   62.77
   62.78   62.83   62.83   62.83   62.83   62.86    63.3   63.36   64.59
                                                                                
                                                                                
                                                                                
                                                                                
                                                
  2616.9  2644.8  2664.8  2704.8  2744.8  2774.8  2934.8  2964.8  2994.8  3024.8
  3214.8  3244.8  3254.8  3274.8  3304.8  3364.8  3554.8  3574.8  3594.8  3624.8
  3684.8  3864.8  3914.8  3924.8  3954.8  4094.8  4164.8  4194.8  4214.8  4254.8
  4464.8  4514.8  4524.8  4554.8  4644.8  4774.8  4794.8  4824.8  4854.8  4921.3
  4923.9  4936.9  4939.4  4946.9  4947.2  4956.9 4958.59  4958.7 4958.81  4958.9
  4966.1  4968.9 4969.81  4969.9  4987.7  4989.6    4990  4990.1 4990.21  5000.8
  5002.2  5009.7  5009.8 5009.91  5010.7  5015.5 5030.79  5030.9  5033.1  5038.2
  5039.8 5040.79  5040.9 5041.01  5041.3  5060.6  5068.7  5081.7    5098  5314.8
  5354.8  5364.8  5414.8  5594.8  5654.8  5664.8  5694.8  5742.5  5781.7  5881.7
  5882.5  5901.7  5932.5  5972.5  5992.5  6001.7  6022.5  6041.7  6072.5  6111.7
  6151.7  6241.7  6322.5  6421.7  6422.5  6482.5  6491.7  6532.5  6551.7  6552.5
  6581.7  6582.5  6671.7  6682.5  6691.2    6780
    72.9   74.31   73.61    72.6   72.47   73.71   73.81   72.31   72.31   73.71
   73.51   71.41   71.21   71.81   71.31   73.11   72.91   72.51   71.21   70.91
   72.51   71.51   69.81   69.71   71.21   71.31   70.11   68.41   68.21   69.81
   68.91   66.52   66.49   67.51   67.71   65.71   65.58   65.48   66.01   66.12
   65.34   66.34   66.53   66.47   66.47   66.39   66.37   67.72   67.72   67.72
   67.72   67.72   67.72   67.72   67.81   67.82   67.82   67.82   67.82   67.87
   67.88   67.93   67.93   67.93   67.93   67.96   68.06   68.06   68.08   68.11
   68.13   68.14   68.14   66.21   66.27   66.56   66.64   66.77   66.24   67.51
   66.78    66.8   68.01   69.01   67.42   67.44   69.31   70.02   70.61   70.01
   69.98   69.31    70.2   69.31    69.4   69.98    71.3   71.53    71.9   71.98
   72.06   72.24    72.4   72.81   72.78    71.8   71.41   70.07   70.28    70.3
   71.76    71.8   72.41   72.24    72.1    70.7
                                                                                
                                                                                
                                                                                
                                                                                
                                                                                
                   62.92   62.88   62.71   62.72   62.72   62.72   62.72   62.77
   62.78   62.83   62.83   62.83   62.83   62.86    63.3   63.36   64.59
                                                                                
                                                                                
                                                                                
                                                                                
                                                
Pier Skew, UpSta & Num, DnSta & Num=  ,4987.7, 2 ,4987.7, 2 , 0 , 0 , 0 ,,
     1.5     1.5
   53.63   63.72
     1.5     1.5
   53.63   63.72
Pier Skew, UpSta & Num, DnSta & Num=  ,5015.5, 2 ,5015.5, 2 , 0 , 0 , 0 ,,
     1.5     1.5
   53.57   63.88
     1.5     1.5
   53.57   63.88
BR Coef= 1 , 1 , 1 ,1.05, 0 ,,,.8,0,1.2,0,
WSPro=,,,, 1 ,,,, 0 ,,,, 0 ,,,,-1 ,-1 ,-1 , 0 , 0 , 0 , 0 , 0
BC Design=,, 0 ,, 0 ,,,,,,
BC HTab HWMax=74.31

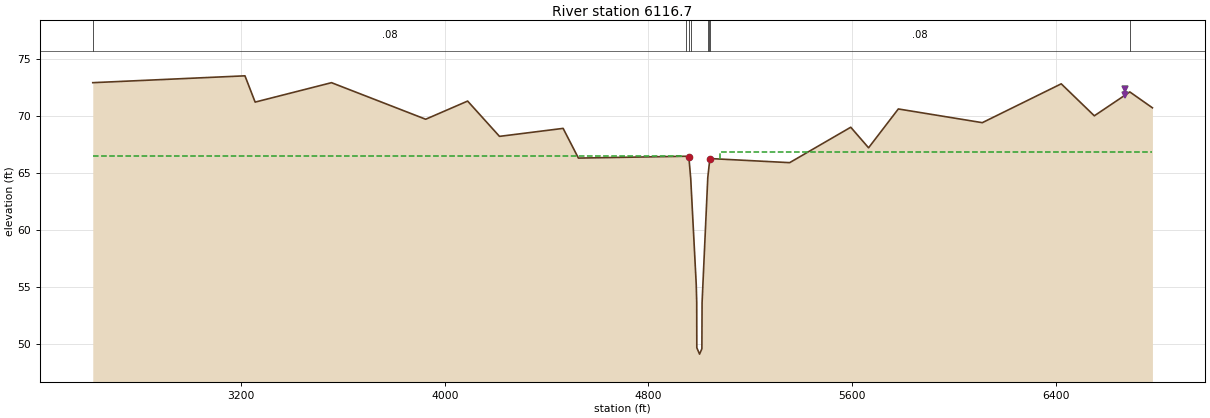
Type RM Length L Ch R = 1 ,6116.7  ,117.6,100.7,104.5
BEGIN DESCRIPTION:
ANTOINE DR - XS 2
END DESCRIPTION:
XS GIS Cut Line= 3
      3086654.72      13867906.6      3086789.29     13864778.61
      3087237.16      13863826.5
#Sta/Elev= 30
  2616.9   72.91  3214.8   73.51  3254.8   71.21  3554.8   72.91  3924.8   69.71
 4089.62    71.3  4214.8   68.21  4464.8   68.91  4524.8   66.31  4947.2   66.47
  4958.9   66.37  4966.1   64.52  4987.7   55.26  4989.6    53.7    4990   49.71
  5000.8   49.15 5009.91   49.62  5010.7   53.66  5033.1    64.6  5039.8   65.96
  5041.3   66.27  5354.8   65.91  5594.8   69.01  5664.8   67.21  5781.7   70.61
  6111.7   69.41  6421.7   72.81  6551.7   70.01  6691.2    72.1    6780   70.71
#Mann= 8 ,-1 , 0
  2616.9     .08       0  4947.2     .04       0  4958.9     .04       0
  4966.1    .015       0  5033.1     .04       0  5039.8     .08       0
  5041.3     .08       0  6691.2     .08       0
Levee=0,,,-1,6671.78,72.38,,
#XS Ineff= 2 , 0
       0    4939    66.5    5081       0    66.8
Permanent Ineff=
       T       F
Bank Sta=4958.9,5041.3
XS Rating Curve= 0
Exp/Cntr=.5,.3