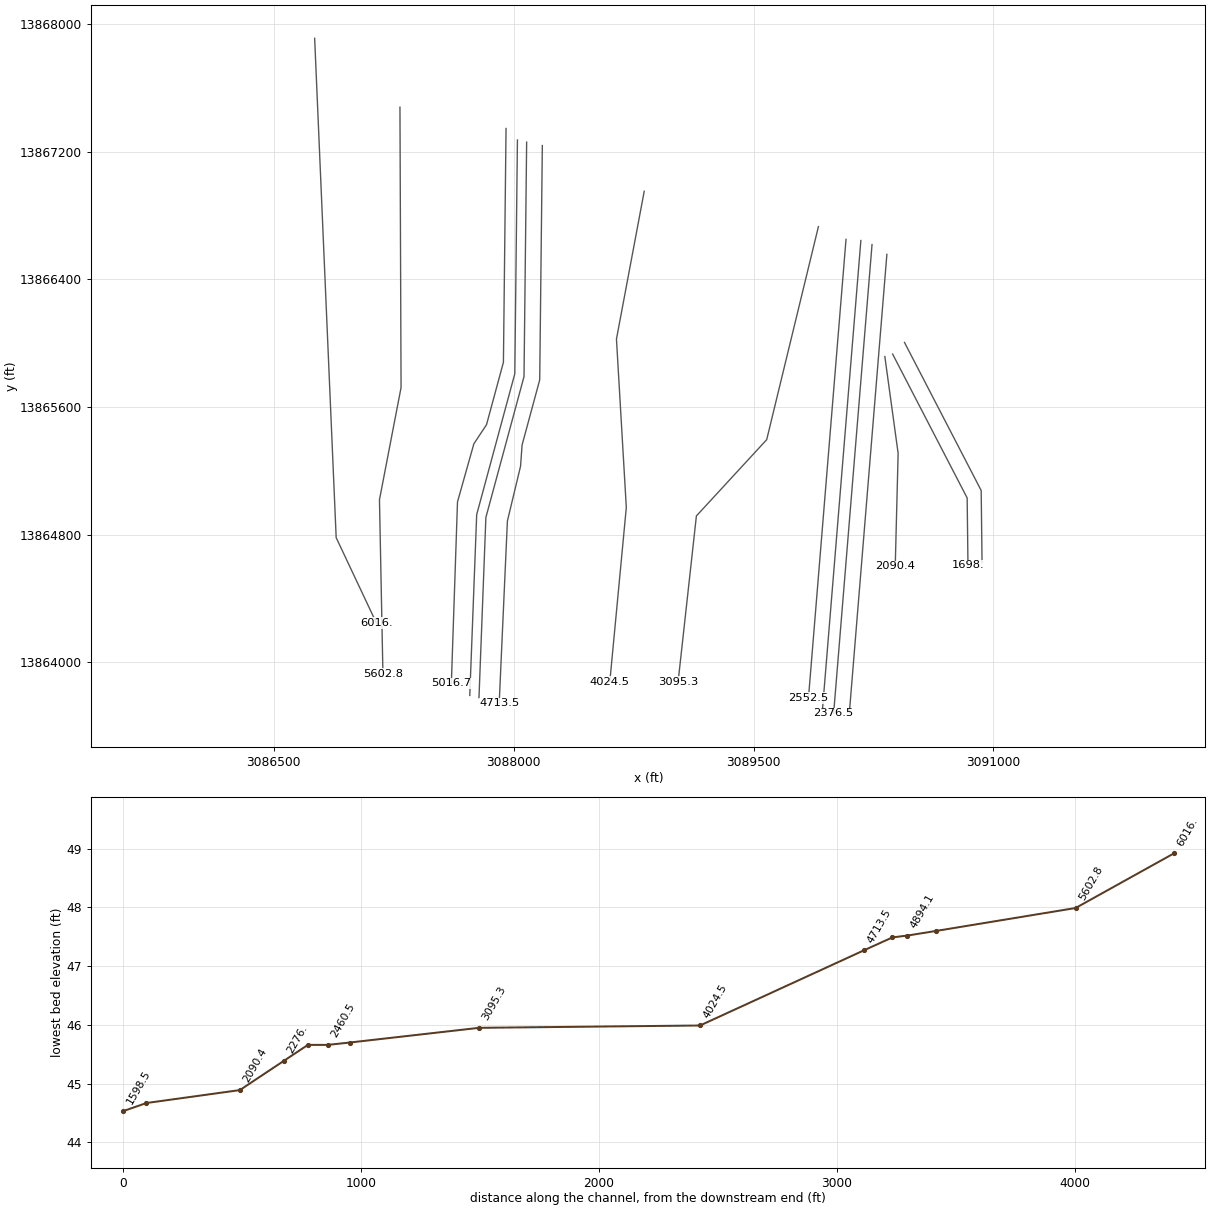
HEC-RAS study E115-00-00.prj: E115-00-00

--- E115-00-00.g01 (geometry) --- (continued)

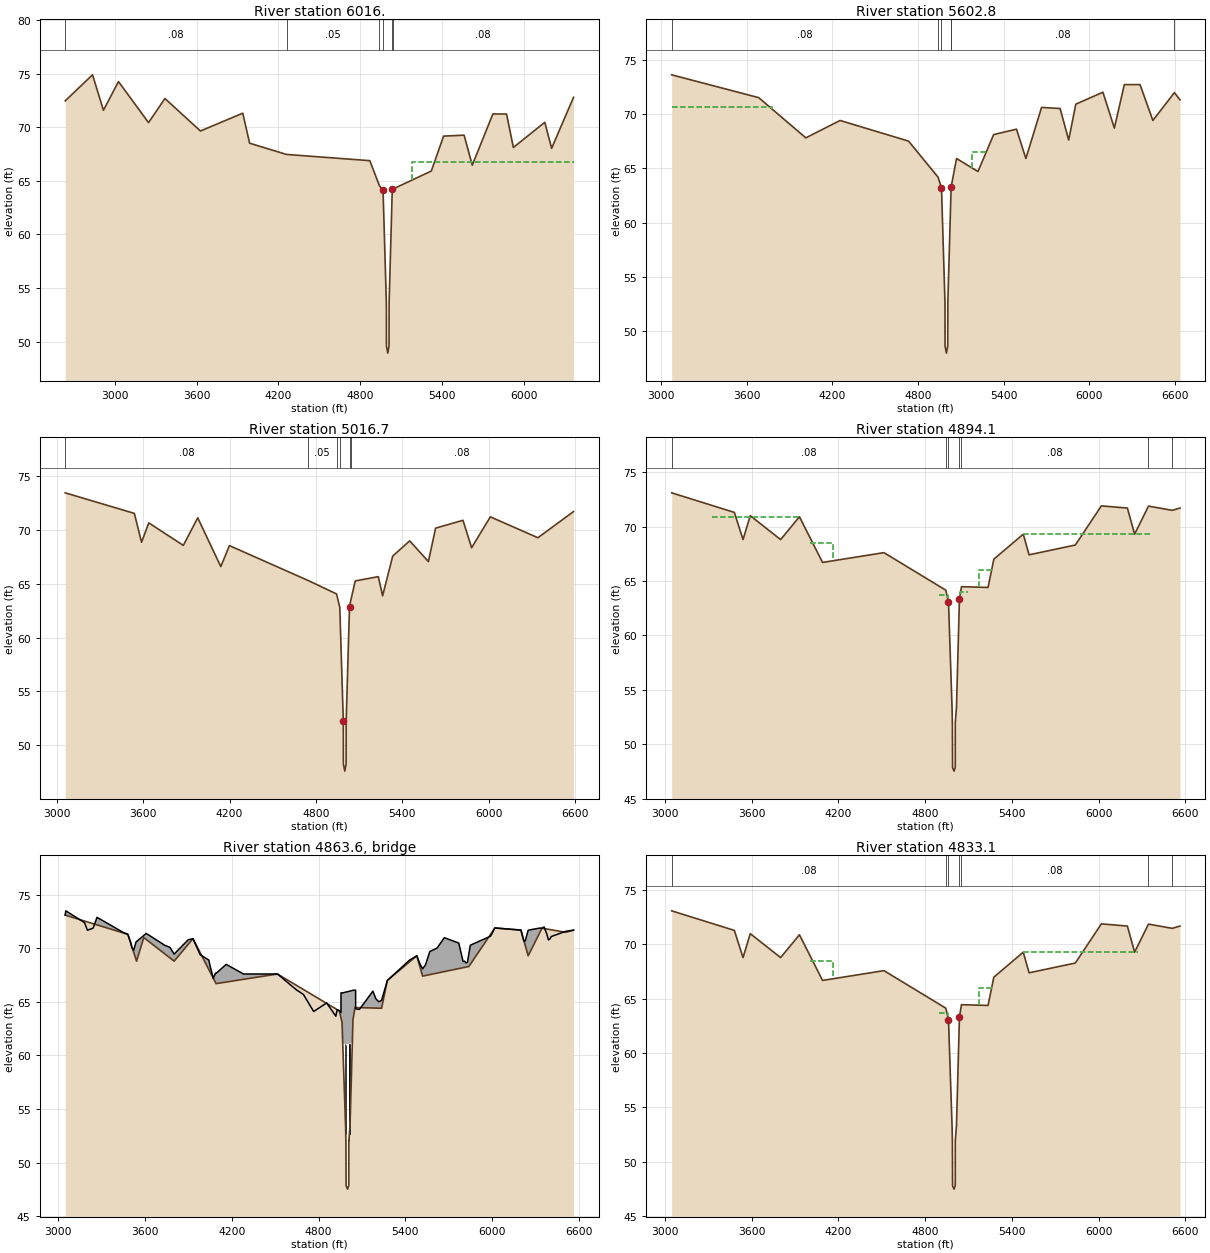
Type RM Length L Ch R = 1 ,6016.   ,437.3,413.2,367.2
BEGIN DESCRIPTION:
ANTOINE DR - XS 1
Interplotated channel, LIDAR overbanks
END DESCRIPTION:
XS GIS Cut Line= 3
      3086756.28      13867909.2      3086890.85     13864781.22
      3087142.12     13864247.04
#Sta/Elev= 30
  2638.7   72.46  2838.7   74.89  2918.7   71.58  3028.7   74.26  3248.7   70.43
  3368.7   72.68  3628.7   69.65  3938.7   71.31  3988.7   68.51  4258.7   67.46
  4868.7   66.88  4938.7   64.55  4965.4   64.13  4989.9   53.56  4990.4   49.57
  5000.2   48.92  5009.2   49.59  5009.9   53.62  5032.9   64.19    5035  64.218
  5318.7   65.91  5408.7   69.17  5558.7   69.26  5618.7   66.46  5769.6   71.24
  5869.6   71.23  5919.6   68.11  6149.6   70.46  6199.6   68.03  6359.9   72.79
#Mann= 6 ,-1 , 0
  2638.7     .08       0  4258.7     .05       0  4938.7     .04       0
  4965.4    .015       0  5032.9     .04       0    5035     .08       0
#XS Ineff= 2 , 0
       0                    5181       0    66.8
Permanent Ineff=
       F       F
Bank Sta=4965.4,5032.9
XS Rating Curve= 0
Exp/Cntr=.3,.1

Type RM Length L Ch R = 1 ,5602.8  ,605.9,586.1,505
BEGIN DESCRIPTION:
Cross Section x05
Located At: DS ANTOINE
END DESCRIPTION:
XS GIS Cut Line= 4
      3087289.54     13867477.92      3087296.52     13865721.63
      3087161.48     13865018.83      3087183.13     13863929.05
#Sta/Elev= 30
  3074.7    73.6  3684.7    71.5  4014.7    67.8  4254.7    69.4  4734.7    67.5
  4941.4   64.18  4965.4    63.2  4989.9   52.63  4990.4   48.64  5000.2   47.99
  5009.2   48.66  5009.9   52.69  5032.9   63.26  5035.5   63.46    5071    65.9
    5221    64.7    5331    68.1    5491    68.6  5556.7    65.9  5666.7    70.6
  5796.7    70.5  5856.7    67.6  5906.7    70.9  6096.7      72  6176.7    68.7
  6246.7    72.7  6356.7    72.7  6446.7    69.4  6597.4   71.96  6636.7    71.3
#Mann= 6 ,-1 , 0
  3074.7     .08       0  4941.4     .04       0  4965.4    .015       0
  5032.9     .04       0  5035.5     .08       0  6597.4     .08       0
#XS Ineff= 2 ,-1
  5180.2    5282    66.5  3074.7 3775.06    70.6
Permanent Ineff=
       F       F
Bank Sta=4965.4,5032.9
XS Rating Curve= 0
Exp/Cntr=.3,.1

Type RM Length L Ch R = 1 ,5016.7  ,144.2,122.6,134.6
BEGIN DESCRIPTION:
COSTA RICA - XS 4
Interplotated channel, LIDAR overbanks
END DESCRIPTION:
XS GIS Cut Line= 6
      3087952.77     13867344.44      3087936.37     13865879.95
      3087830.77     13865489.02      3087751.55     13865368.94
       3087649.3     13865005.37      3087610.84     13863868.53
#Sta/Elev= 30
  3059.4   73.44  3539.4   71.53  3589.4   68.85  3639.4   70.65  3879.4   68.56
  3979.4   71.12  4139.4   66.59  4199.4   68.54    4744   65.31    4943  64.052
  4965.4   62.81  4989.9   52.24  4990.4   48.25  5000.2    47.6  5009.2   48.27
  5009.9    52.3  5032.9   62.87    5040  63.351  5072.8   65.26  5232.8   65.66
  5262.8   63.88  5332.8   67.57  5450.5   68.98  5580.5   67.06  5630.5   70.16
  5820.5   70.89  5880.5   68.34  6010.5   71.21  6340.5   69.27  6587.9    71.7
#Mann= 6 ,-1 , 0
  3059.4     .08       0    4744     .05       0    4943     .04       0
  4965.4    .015       0  5032.9     .04       0    5040     .08       0
Bank Sta=4989.9,5032.9
XS Rating Curve= 0
Exp/Cntr=.5,.3

Type RM Length L Ch R = 1 ,4894.1  ,106.1,61,61.3
BEGIN DESCRIPTION:
COSTA RICA - XS 3
END DESCRIPTION:
XS GIS Cut Line= 4
      3088023.95     13867272.39      3088007.55      13865807.9
      3087769.27      13864925.8        3087726.     13863792.69
#Sta/Elev= 30
  3047.7   73.11  3481.3   71.31  3541.3   68.81  3591.3   71.01  3801.3   68.81
  3931.3   70.91  4091.3   66.71  4515.9   67.61  4943.7   64.16  4962.3   63.11
  4987.3    53.2  4989.2   51.91  4990.6   47.84  5000.7   47.52  5009.2   47.86
  5009.4   51.99  5017.5   53.39  5038.1   63.35  5052.2   64.48  5235.9   64.41
  5275.9   67.01  5479.6   69.31  5519.6   67.41  5839.6   68.31  6019.6   71.91
  6199.6   71.71  6249.7   69.31  6345.6   71.89  6509.5    71.5  6563.5   71.71
#Mann= 7 ,-1 , 0
  3047.7     .08       0  4943.7     .04       0  4962.3    .015       0
  5038.1     .04       0  5052.2     .08       0  6345.6     .08       0
  6509.5     .99       0
#XS Ineff= 6 ,-1
    4900    4957   63.75 3325.87 3931.62   70.91    5044    5100      64
 5478.23 6361.92   69.31 4002.85 4161.14   68.49  5175.9    5275   65.98
Permanent Ineff=
       F       F       F       F       F       F
Bank Sta=4962.3,5038.1
XS Rating Curve= 0
Exp/Cntr=.5,.3

Type RM Length L Ch R = 3 ,4863.6  ,,,
BEGIN DESCRIPTION:
COSTA RICA
Structure ID: E115-00-00-04
END DESCRIPTION:
Bridge Culvert--1,0,-1,-1, 0
Deck Dist Width WeirC Skew NumUp NumDn MinLoCord MaxHiCord MaxSubmerge Is_Ogee
10,41,2.6,0, 132, 132, , , .95, 0, ,,,
  3047.7  3051.3  3107.7  3167.7  3181.3  3201.3  3237.7  3241.3  3267.7  3271.3
  3291.3  3447.7  3477.7  3481.3  3501.3  3507.7  3521.3  3537.7  3541.3  3591.3
  3607.7  3737.7  3767.7  3771.3  3801.3  3831.3  3861.3  3897.7  3931.3  3981.3
  3987.7  4007.7  4037.7  4041.3  4047.7  4071.3  4087.7  4091.3  4161.3  4281.3
  4307.7  4475.4  4515.4  4515.9  4645.9  4695.4  4765.9  4775.4  4855.9  4919.4
  4928.6    4938  4943.7  4945.4 4954.89    4955 4955.11  4956.6 4961.81  4961.9
  4962.3  4967.2  4987.3  4988.1  4989.2  4990.6  4990.7  5000.7  5006.5  5009.1
  5009.2  5009.4  5010.7  5017.5 5033.29  5033.4  5038.1    5044  5049.3  5052.2
 5056.19  5056.3 5056.41  5060.3    5083  5175.9  5195.9  5215.9  5235.9  5275.9
  5369.7  5429.6  5479.6  5499.6  5499.7  5519.6  5539.6  5569.6  5619.6  5659.6
  5669.7  5769.7  5799.7  5809.6  5819.7  5829.7  5839.6  5849.7  5949.6  5989.6
  6019.6  6099.7  6159.7  6179.7  6189.7  6199.6  6209.7  6219.6  6229.6  6249.6
  6249.7  6299.6  6329.7  6345.6  6359.6  6359.7  6379.6  6389.6  6399.6  6409.6
  6509.5  6563.5
    73.1   73.51   73.03   72.53   72.41    71.7   71.87   71.91    72.9   72.87
   72.72    71.5   71.33   71.31   70.51   70.09   69.83    70.6   70.64   71.21
    71.4   70.28   70.13   70.11   69.47   69.88    70.3    70.8   70.91   69.41
   69.36   69.19   68.94   68.91   68.48   67.21    67.7   67.67   68.51   67.61
   67.61   67.61   67.61   67.61   66.14    65.7   64.11   64.19   64.91   63.67
   64.28   64.23   64.16   64.14   64.02   65.85   65.85   65.85   65.85   65.85
   65.85   65.85   65.92   65.92   65.92   65.93   65.93   65.96   65.98   65.99
   65.99   65.99   65.99   66.02   66.07   66.07   66.08    66.1    66.1    66.1
    66.1    66.1   64.41   64.34   64.31   66.01   65.31   65.02   65.15   67.01
   68.17   68.91   69.31   68.61    68.6   68.09   68.47   69.71   70.03    70.8
      71    70.5   68.78   68.81   68.64    68.7   69.49    70.3    70.9   71.14
   71.91   71.82   71.75   71.73   71.72   71.71   71.21   70.71    70.7    71.7
    71.7   71.82    71.9   71.89   72.01   72.01   71.31    70.8   70.87   71.11
    71.6    71.7
                                                                                
                                                                                
                                                                                
                                                                                
                                                                                
                                                                                
           61.16   61.02   61.02   61.02   61.03   61.03   61.06   61.08   61.09
   61.09   61.09   61.09   61.12   61.17   61.07
                                                                                
                                                                                
                                                                                
                                                                                
                                                                                
                
  3047.7  3051.3  3107.7  3167.7  3181.3  3201.3  3237.7  3241.3  3267.7  3271.3
  3291.3  3447.7  3477.7  3481.3  3501.3  3507.7  3521.3  3537.7  3541.3  3591.3
  3607.7  3737.7  3767.7  3771.3  3801.3  3831.3  3861.3  3897.7  3931.3  3981.3
  3987.7  4007.7  4037.7  4041.3  4047.7  4071.3  4087.7  4091.3  4161.3  4281.3
  4307.7  4475.4  4515.4  4515.9  4645.9  4695.4  4765.9  4775.4  4855.9  4919.4
  4928.6    4938  4943.7  4945.4 4954.89    4955 4955.11  4956.6 4961.81  4961.9
  4962.3  4967.2  4987.3  4988.1  4989.2  4990.6  4990.7  5000.7  5006.5  5009.1
  5009.2  5009.4  5010.7  5017.5 5033.29  5033.4  5038.1    5044  5049.3  5052.2
 5056.19  5056.3 5056.41  5060.3    5083  5175.9  5195.9  5215.9  5235.9  5275.9
  5369.7  5429.6  5479.6  5499.6  5499.7  5519.6  5539.6  5569.6  5619.6  5659.6
  5669.7  5769.7  5799.7  5809.6  5819.7  5829.7  5839.6  5849.7  5949.6  5989.6
  6019.6  6099.7  6159.7  6179.7  6189.7  6199.6  6209.7  6219.6  6229.6  6249.6
  6249.7  6299.6  6329.7  6345.6  6359.6  6359.7  6379.6  6389.6  6399.6  6409.6
  6509.5  6563.5
    73.1   73.51   73.03   72.53   72.41    71.7   71.87   71.91    72.9   72.87
   72.72    71.5   71.33   71.31   70.51   70.09   69.83    70.6   70.64   71.21
    71.4   70.28   70.13   70.11   69.47   69.88    70.3    70.8   70.91   69.41
   69.36   69.19   68.94   68.91   68.48   67.21    67.7   67.67   68.51   67.61
   67.61   67.61   67.61   67.61   66.14    65.7   64.11   64.19   64.91   63.67
   64.28   64.23   64.16   64.14   64.02   65.85   65.85   65.85   65.85   65.85
   65.85   65.85   65.92   65.92   65.92   65.93   65.93   65.96   65.98   65.99
   65.99   65.99   65.99   66.02   66.07   66.07   66.08    66.1    66.1    66.1
    66.1    66.1   64.41   64.34   64.31   66.01   65.31   65.02   65.15   67.01
   68.17   68.91   69.31   68.61    68.6   68.09   68.47   69.71   70.03    70.8
      71    70.5   68.78   68.81   68.64    68.7   69.49    70.3    70.9   71.14
   71.91   71.82   71.75   71.73   71.72   71.71   71.21   70.71    70.7    71.7
    71.7   71.82    71.9   71.89   72.01   72.01   71.31    70.8   70.87   71.11
    71.6    71.7
                                                                                
                                                                                
                                                                                
                                                                                
                                                                                
                                                                                
           61.16   61.02   61.02   61.02   61.03   61.03   61.06   61.08   61.09
   61.09   61.09   61.09   61.12   61.17   61.07
                                                                                
                                                                                
                                                                                
                                                                                
                                                                                
                
Pier Skew, UpSta & Num, DnSta & Num=  ,4983.3, 2 ,4983.3, 2 , 0 , 0 , 0 ,,
       2       2
   53.38   62.05
       2       2
   53.38   62.05
Pier Skew, UpSta & Num, DnSta & Num=  ,4988.1, 2 ,4988.1, 2 , 0 , 0 , 0 ,,
      .5      .5
   50.92   62.02
      .5      .5
   50.92   62.02
Pier Skew, UpSta & Num, DnSta & Num=  ,5009.4, 2 ,5009.4, 2 , 0 , 0 , 0 ,,
      .5      .5
   46.85   62.09
      .5      .5
   46.85   62.09
Pier Skew, UpSta & Num, DnSta & Num=  ,5013.5, 2 ,5013.5, 2 , 0 , 0 , 0 ,,
       2       2
   51.29   62.11
       2       2
   51.29   62.11
BR Coef= 1 , 1 , 1 ,1.05, 0 ,,,.8,0,1.2,0,
WSPro=,,,, 1 ,,,, 0 ,,,, 0 ,,,,-1 ,-1 ,-1 , 0 , 0 , 0 , 0 , 0
BC Design=,, 0 ,, 0 ,,,,,,
BC HTab HWMax=73.51

Type RM Length L Ch R = 1 ,4833.1  ,122,119.6,127
BEGIN DESCRIPTION:
COSTA RICA - XS 2
END DESCRIPTION:
XS GIS Cut Line= 4
      3088081.56     13867258.62      3088065.12     13865790.32
      3087826.73     13864907.82      3087783.59     13863778.12
#Sta/Elev= 30
  3047.7   73.08  3481.3   71.28  3541.3   68.78  3591.3   70.98  3801.3   68.78
  3931.3   70.88  4091.3   66.68  4515.9   67.58  4943.7   64.13  4962.3   63.08
  4987.3   53.17  4989.2   51.88  4990.6   47.81  5000.7   47.49  5009.2   47.83
  5009.4   51.96  5017.5   53.36  5038.1   63.32  5052.2   64.45  5235.9   64.38
  5275.9   66.98  5479.6   69.28  5519.6   67.38  5839.6   68.28  6019.6   71.88
  6199.6   71.68  6249.7   69.28  6345.6   71.86  6509.5   71.47  6563.5   71.68
#Mann= 7 ,-1 , 0
  3047.7     .08       0  4943.7     .04       0  4962.3    .015       0
  5038.1     .04       0  5052.2     .08       0  6345.6     .08       0
  6509.5     .99       0
#XS Ineff= 6 ,-1
    4900    4957    63.7 3403.16 3931.01   70.87 4002.85 4161.14   68.49
    5044    5100    63.7  5175.9    5275   65.98 5479.04    6276   69.28
Permanent Ineff=
       F       F       F       F       F       F
Bank Sta=4962.3,5038.1
XS Rating Curve= 0
Exp/Cntr=.5,.3

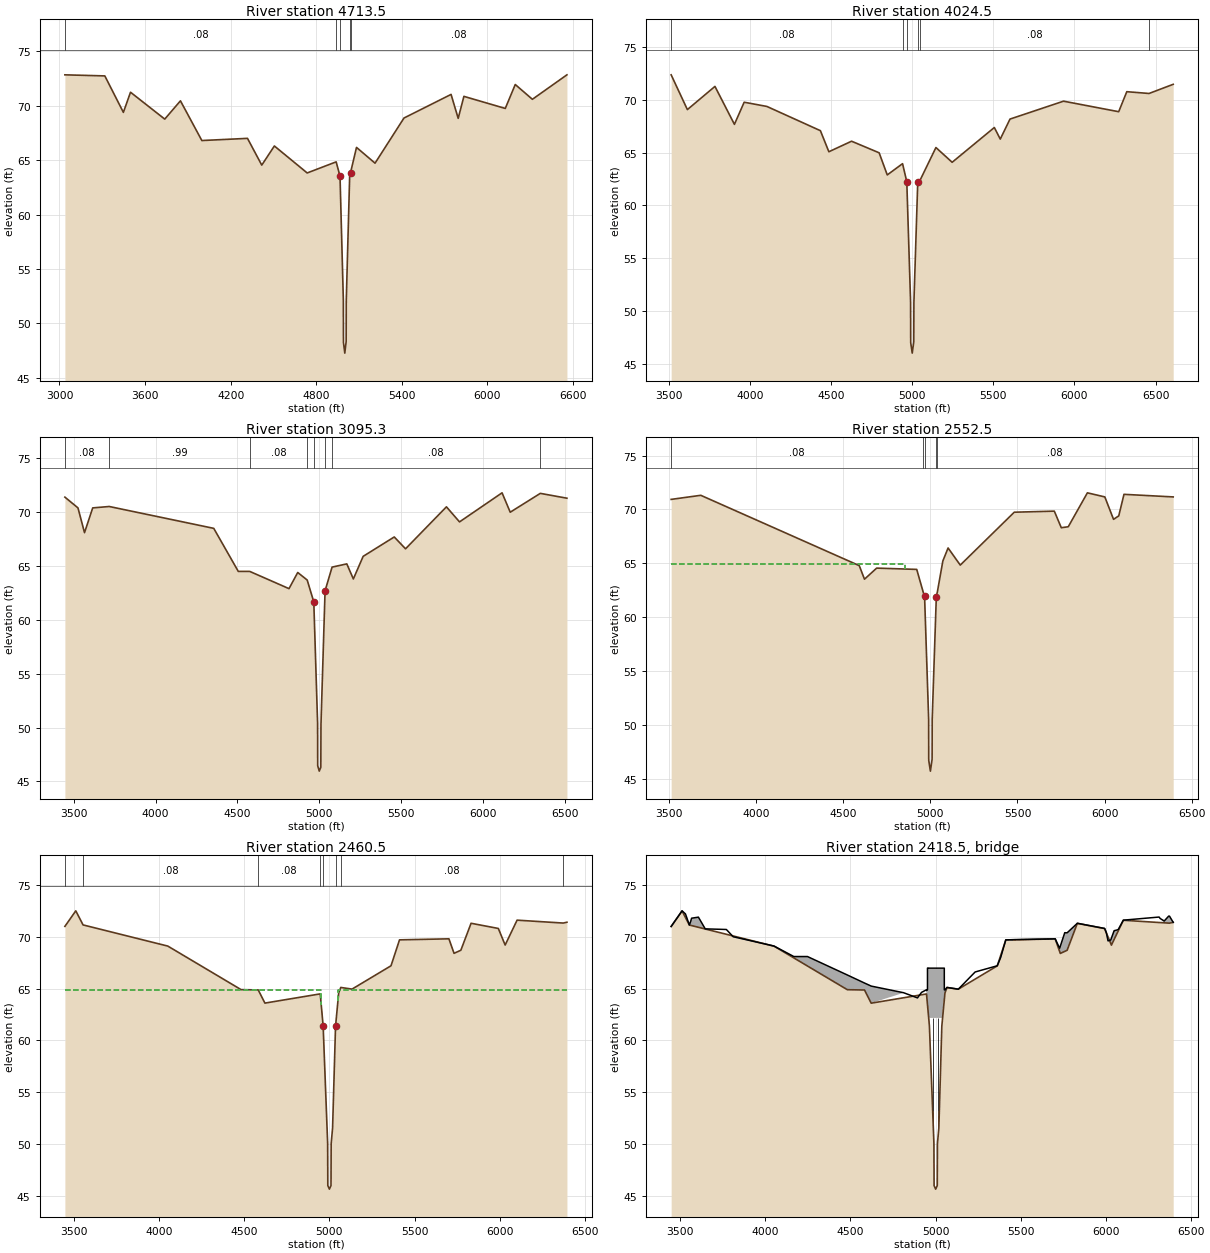
Type RM Length L Ch R = 1 ,4713.5  ,562.6,689,647.1
BEGIN DESCRIPTION:
COSTA RICA - XS 1
Interplotated channel, LIDAR overbanks
END DESCRIPTION:
XS GIS Cut Line= 6
      3088179.66     13867237.79      3088163.21     13865769.49
      3088052.87     13865361.03      3088043.52     13865228.77
      3087961.29      13864885.7      3087910.01     13863744.59
#Sta/Elev= 30
    3038   72.85    3318   72.75    3448    69.4    3498   71.25    3738   68.78
    3848   70.46    3998   66.81    4318   67.01    4418   64.55  4506.4   66.31
  4736.4   63.83  4939.5   64.85  4966.5   63.53  4989.9   52.12  4990.6   48.26
    5000   47.27  5009.5   48.34  5010.3   52.07    5034   63.48    5040  63.845
  5082.1   66.18  5212.1   64.73  5414.9   68.88  5744.9   71.05  5794.9   68.85
  5834.9   70.87  6124.9   69.76  6194.9   71.96  6314.9    70.6  6557.1   72.85
#Mann= 5 ,-1 , 0
    3038     .08       0  4939.5     .04       0  4966.5    .015       0
    5034     .04       0    5040     .08       0
Bank Sta=4966.5,5040
XS Rating Curve= 0
Exp/Cntr=.3,.1

Type RM Length L Ch R = 1 ,4024.5  ,1011.3,929.2,789.6
BEGIN DESCRIPTION:
Cross Section x04
Located At: DS COSTA RICA
END DESCRIPTION:
XS GIS Cut Line= 4
      3088816.56     13866951.18      3088643.03      13866025.2
      3088704.64     13864970.44      3088601.58     13863879.29
#Sta/Elev= 30
    3514    72.4    3614    69.1    3784    71.3    3904    67.7    3964    69.8
    4104    69.4    4434    67.1  4486.1    65.1  4626.1    66.1  4796.1      65
  4846.1    62.9  4940.4   63.97  4966.5   62.25  4989.9   50.84  4990.6   46.98
    5000   45.99  5009.5   47.06  5010.3   50.79    5034    62.2  5050.6   62.47
  5146.1    65.5  5246.1    64.1  5506.1    67.4  5542.7    66.3  5602.7    68.2
  5932.7    69.9  6272.7    68.9  6322.7    70.8  6459.8   70.63  6608.7    71.5
#Mann= 6 ,-1 , 0
    3514     .08       0  4940.4     .04       0  4966.5    .015       0
    5034     .04       0  5050.6     .08       0  6459.8     .08       0
#XS Ineff= 2 , 0
       0  4626.1    66.1  5146.1       0    65.5
Permanent Ineff=
       F       F
Bank Sta=4966.5,5034
XS Rating Curve= 0
Exp/Cntr=.3,.1

Type RM Length L Ch R = 1 ,3095.3  ,408.1,542.8,600.4
BEGIN DESCRIPTION:
Cross Section x03
Located At: US MANGUM RD
END DESCRIPTION:
XS GIS Cut Line= 4
 3089905.555841413866729.6085917      3089582.17     13865394.97
      3089142.76      13864917.3      3089028.27     13863876.96
#Sta/Elev= 30
    3445    71.4    3525    70.4    3565    68.1    3615    70.4  3715.8   70.53
    4355    68.5    4505    64.5    4575    64.5    4815    62.9  4868.3    64.4
  4926.1    63.7  4966.5   61.67  4989.8   50.37  4990.4   46.45    5000   45.95
  5009.4   46.31  5010.4   50.31  5035.4    62.7  5078.3    64.9  5168.3    65.2
  5208.3    63.8  5268.3    65.9  5458.3    67.7  5527.3    66.6  5777.3    70.5
  5857.3    69.1  6117.3    71.8  6167.3      70  6351.2   71.75  6513.9    71.3
#Mann= 8 ,-1 , 0
    3445     .08       0  3715.8     .99       0    4575     .08       0
  4926.1     .04       0  4966.5    .015       0  5035.4     .04       0
  5078.3     .08       0  6351.2     .07       0
#XS Ineff= 2 , 0
       0  4868.3    64.4    5164       0      65
Permanent Ineff=
       F       F
Bank Sta=4966.5,5035.4
XS Rating Curve= 0
Exp/Cntr=.3,.1

Type RM Length L Ch R = 1 ,2552.5  ,102.8,92,99.7
BEGIN DESCRIPTION:
MAGNUM - XS 4
Interplotated channel, LIDAR overbanks
END DESCRIPTION:
XS GIS Cut Line= 2
       3090078.1     13866649.71      3089843.34      13863776.7
#Sta/Elev= 30
  3511.5   70.93  3681.5   71.31  4591.5   64.78  4621.5   63.52  4691.5   64.55
  4921.5   64.43    4960  62.246  4966.5   61.96  4989.9   50.55  4990.4   46.98
  4990.6   46.69    5000    45.7  5009.5   46.77  5009.8   46.97  5010.3    50.5
    5034   61.91    5040  62.338  5071.5   65.21  5101.5   66.42  5171.5   64.83
  5481.5   69.74  5711.5   69.84  5751.5    68.3  5791.5   68.39  5901.5   71.54
  6001.5   71.16  6051.5   69.08  6081.5    69.4  6111.5    71.4  6394.1   71.16
#Mann= 5 ,-1 , 0
  3511.5     .08       0    4960     .04       0  4966.5    .015       0
    5034     .04       0    5040     .08       0
#XS Ineff= 2 , 0
       0    4852    64.9               0
Permanent Ineff=
       F       F
Bank Sta=4966.5,5034
XS Rating Curve= 0
Exp/Cntr=.5,.3

Type RM Length L Ch R = 1 ,2460.5  ,71.6,84,75.1
BEGIN DESCRIPTION:
MAGNUM - XS 3
END DESCRIPTION:
XS GIS Cut Line= 4
 3090170.976702513866642.5510151      3090168.37     13866610.65
      3089933.61     13863737.64 3089931.003297513863705.7389849
#Sta/Elev= 30
  3447.5      71  3511.5    72.5  3554.2   71.14  4051.5    69.1  4481.5    64.9
  4582.3   64.87  4621.5    63.6  4946.2   64.49  4963.3   61.39  4989.7   50.06
  4990.7      46  4999.9   45.66  5009.3      46  5010.3   50.05  5018.6   51.54
    5036   61.37  5054.6   64.59  5066.7   65.11  5132.9   64.95  5361.5    67.2
  5411.5    69.7  5701.5    69.8  5731.5    68.4  5771.5    68.7  5831.5    71.3
  5991.5    70.8  6031.5    69.2  6101.5    71.6  6372.2   71.32  6394.1    71.4
#Mann= 8 ,-1 , 0
  3447.5     .08       0  3554.2     .08       0  4582.3     .08       0
  4946.2     .04       0  4963.3    .015       0    5036     .04       0
  5066.7     .08       0  6372.2     .99       0
#XS Ineff= 2 , 0
       0    4952    64.9    5050       0    64.9
Permanent Ineff=
       F       F
Bank Sta=4963.3,5036
XS Rating Curve= 0
Exp/Cntr=.5,.3

Type RM Length L Ch R = 3 ,2418.5  ,,,
BEGIN DESCRIPTION:
MANGUM ROAD
Structure ID: E115-00-00-03
Bridge deck width was extended by 3' to accomodate the 3' diameter pipeline just downstream of it.
END DESCRIPTION:
Bridge Culvert--1,0,-1,-1, 0
Deck Dist Width WeirC Skew NumUp NumDn MinLoCord MaxHiCord MaxSubmerge Is_Ogee
10,67,2.6,0, 60, 60, , , .95, 0, ,,,
  3447.5  3511.5  3531.5  3554.2  3561.5  3567.5  3607.5  3647.5  3771.5  3811.5
  4051.5  4167.5  4247.5  4481.5  4581.5  4621.5  4811.5  4893.1    4917  4944.4
  4946.2 4951.89    4952  4956.8 4962.71  4962.8 5039.59  5039.7  5042.2  5050.6
 5050.71  5054.6    5066  5132.9  5231.5  5361.5  5381.5  5411.5  5701.5  5727.5
  5731.5  5757.5  5771.5  5831.5  5991.5  6001.5  6011.5  6027.5  6031.5  6047.5
  6051.5  6061.5  6071.5  6101.5  6311.5  6317.5  6341.5  6367.5  6372.2  6394.1
      71   72.51   72.21   71.15   71.46    71.8    71.9   70.77   70.71   70.01
   69.11    68.1    68.1   66.32   65.55   65.25   64.61   64.11   64.64   64.88
   64.82   64.89   66.99   66.99   66.98   66.98   66.98   66.98   66.98   66.98
   64.88   64.88   65.12   64.95   66.61   67.21   68.01   69.71   69.81    68.9
    69.1    70.4   70.39   71.31   70.81   70.41   69.61    69.7   69.88    70.6
   70.61   70.65   70.71   71.61   71.91   71.77   71.53      72      72    71.4
      71    72.5    72.2   71.14    70.8    70.8   70.78   70.76    70.7      70
    69.1   67.97   67.19    64.9    64.9    63.6    64.6   64.11   64.63   64.87
   64.49   63.31   63.28   62.28   61.47   62.18   62.18   61.87   62.76      64
   64.02   64.59   65.11   64.95    66.6    67.2      68    69.7    69.8   68.59
    68.4    68.6    68.7    71.3    70.8    70.4    69.6   69.28    69.2   69.28
    69.3    69.7    70.7    71.6    71.9   71.76    71.2    71.3   71.32    71.4
  3447.5  3511.5  3531.5  3554.2  3561.5  3567.5  3607.5  3647.5  3771.5  3811.5
  4051.5  4167.5  4247.5  4481.5  4581.5  4621.5  4811.5  4893.1    4917  4944.4
  4946.2 4951.89    4952  4956.8 4962.71  4962.8 5039.59  5039.7  5042.2  5050.6
 5050.71  5054.6    5066  5132.9  5231.5  5361.5  5381.5  5411.5  5701.5  5727.5
  5731.5  5757.5  5771.5  5831.5  5991.5  6001.5  6011.5  6027.5  6031.5  6047.5
  6051.5  6061.5  6071.5  6101.5  6311.5  6317.5  6341.5  6367.5  6372.2  6394.1
      71   72.51   72.21   71.15   71.46    71.8    71.9   70.77   70.71   70.01
   69.11    68.1    68.1   66.32   65.55   65.25   64.61   64.11   64.64   64.88
   64.82   64.89   66.99   66.99   66.98   66.98   66.98   66.98   66.98   66.98
   64.88   64.88   65.12   64.95   66.61   67.21   68.01   69.71   69.81    68.9
    69.1    70.4   70.39   71.31   70.81   70.41   69.61    69.7   69.88    70.6
   70.61   70.65   70.71   71.61   71.91   71.77   71.53      72      72    71.4
      71    72.5    72.2   71.14    70.8    70.8   70.78   70.76    70.7      70
    69.1   67.97   67.19    64.9    64.9    63.6    64.6   64.11   64.63   64.87
   64.49   63.31   63.28   62.28   61.47   62.18   62.18   61.87   62.76      64
   64.02   64.59   65.11   64.95    66.6    67.2      68    69.7    69.8   68.59
    68.4    68.6    68.7    71.3    70.8    70.4    69.6   69.28    69.2   69.28
    69.3    69.7    70.7    71.6    71.9   71.76    71.2    71.3   71.32    71.4
Pier Skew, UpSta & Num, DnSta & Num=  ,4985.7, 2 ,4985.7, 2 , 0 , 0 , 0 ,,
     1.5     1.5
   50.02   63.19
     1.5     1.5
   50.02   63.19
Pier Skew, UpSta & Num, DnSta & Num=  ,5014.6, 2 ,5014.6, 2 , 0 , 0 , 0 ,,
     1.5     1.5
   49.69   63.19
     1.5     1.5
   49.69   63.19
BR Coef= 1 , 1 , 1 ,1.05, 0 ,,,.8,-1,1.2,0,
WSPro=,,,, 1 ,,,, 0 ,,,, 0 ,,,,-1 ,-1 ,-1 , 0 , 0 , 0 , 0 , 0
BC Design=,, 0 ,, 0 ,,,,,,
BC HTab HWMax=72.5

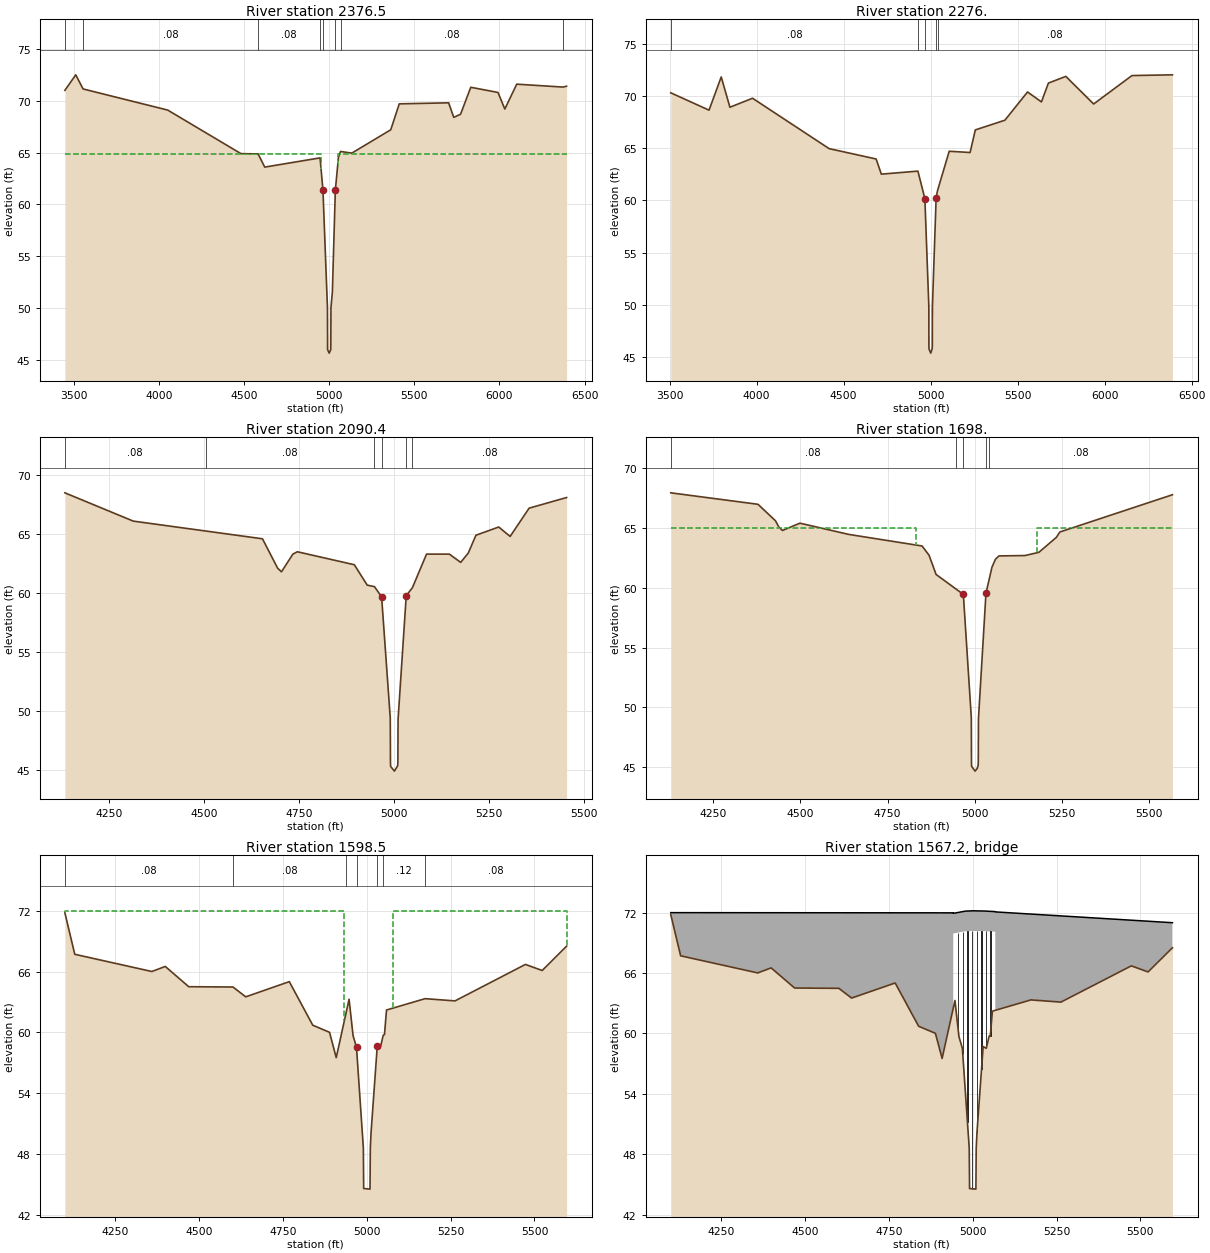
Type RM Length L Ch R = 1 ,2376.5  ,97.6,100.5,99.1
BEGIN DESCRIPTION:
MAGNUM - XS 2
END DESCRIPTION:
XS GIS Cut Line= 4
 3090240.716702513866617.2510151      3090238.11     13866585.35
      3090003.35     13863712.34 3090000.743297513863680.4389849
#Sta/Elev= 30
  3447.5      71  3511.5    72.5  3554.2   71.14  4051.5    69.1  4481.5    64.9
  4582.3   64.87  4621.5    63.6  4946.2   64.49  4963.3   61.39  4989.7   50.06
  4990.7      46  4999.9   45.66  5009.3      46  5010.3   50.05  5018.6   51.54
    5036   61.37  5054.6   64.59  5066.7   65.11  5132.9   64.95  5361.5    67.2
  5411.5    69.7  5701.5    69.8  5731.5    68.4  5771.5    68.7  5831.5    71.3
  5991.5    70.8  6031.5    69.2  6101.5    71.6  6372.2   71.32  6394.1    71.4
#Mann= 8 ,-1 , 0
  3447.5     .08       0  3554.2     .08       0  4582.3     .08       0
  4946.2     .04       0  4963.3    .015       0    5036     .04       0
  5066.7     .08       0  6372.2     .99       0
#XS Ineff= 2 , 0
       0    4952    64.9    5050       0    64.9
Permanent Ineff=
       F       F
Bank Sta=4963.3,5036
XS Rating Curve= 0
Exp/Cntr=.5,.3

Type RM Length L Ch R = 1 ,2276.   ,178.6,185.6,193.2
BEGIN DESCRIPTION:
MAGNUM - XS 1
Interplotated channel, LIDAR overbanks
END DESCRIPTION:
XS GIS Cut Line= 2
      3090333.59     13866555.84      3090098.83     13863682.82
#Sta/Elev= 30
    3507   70.29    3727   68.63    3797   71.81    3847   68.91    3977   69.77
    4417   64.95    4687   63.96    4717   62.51    4927    62.8  4967.1   60.18
  4989.9   49.88  4990.4   46.18  4990.8   45.79  5000.8   45.39  5009.4   45.85
  5009.9   46.18  5010.4   49.78  5031.9   60.27    5040  60.941    5107    64.7
    5227   64.58    5257   66.74    5427   67.67    5557   70.37    5637   69.42
    5677   71.22    5777   71.86    5937   69.22    6157   71.94  6389.6   72.01
#Mann= 5 ,-1 , 0
    3507     .08       0    4927     .04       0  4967.1    .015       0
  5031.9     .04       0    5040     .08       0
Bank Sta=4967.1,5031.9
XS Rating Curve= 0
Exp/Cntr=.3,.1

Type RM Length L Ch R = 1 ,2090.4  ,343.4,392.4,424.5
BEGIN DESCRIPTION:
Cross Section x02
Located At: DS MANGUM RD
END DESCRIPTION:
XS GIS Cut Line= 3
      3090320.78      13865915.9      3090403.91     13865309.84
      3090385.77     13864601.63
#Sta/Elev= 30
  4133.6    68.5  4313.6    66.1  4504.2   65.26  4653.6    64.6  4693.6    62.1
  4703.6    61.8  4733.6    63.3  4745.3    63.5  4895.3    62.4  4929.2   60.67
  4948.3   60.54  4967.1   59.68  4989.9   49.38  4990.4   45.68  4990.8   45.29
  5000.8   44.89  5009.4   45.35  5009.9   45.68  5010.4   49.28  5031.9   59.77
  5048.3   60.46  5085.3    63.3  5145.3    63.3  5175.3    62.6  5195.3    63.4
  5215.3    64.9  5275.3    65.6  5305.3    64.8  5355.3    67.2  5453.8    68.1
#Mann= 6 ,-1 , 0
  4133.6     .08       0  4504.2     .08       0  4948.3     .04       0
  4967.1    .015       0  5031.9     .04       0  5048.3     .08       0
#XS Ineff= 2 , 0
       0  4745.3    63.5               0
Permanent Ineff=
       F       F
Bank Sta=4967.1,5031.9
XS Rating Curve= 0
Exp/Cntr=.3,.1

Type RM Length L Ch R = 1 ,1698.   ,103.2,99.5,99.6
BEGIN DESCRIPTION:
MKT RR - XS 4
Interplotated channel, LIDAR overbanks
END DESCRIPTION:
XS GIS Cut Line= 3
      3090369.59     13865930.96      3090835.44     13865029.81
      3090840.53     13864607.23
#Sta/Elev= 30
    4129   67.96    4379      67    4429   65.62    4439   65.08    4449   64.81
    4499   65.42    4639   64.48    4849   63.51    4869   62.73    4889   61.13
    4945  59.933  4967.1   59.46  4989.9   49.16  4990.4   45.46  4990.8   45.07
  5000.8   44.67  5006.7   44.89  5009.4   45.13  5009.9   45.46  5010.4   49.06
  5031.9   59.55    5040  60.583    5049   61.73    5059    62.4    5069   62.68
  5143.4   62.71  5183.4   62.98  5233.4   64.23  5243.4   64.68    5566    67.8
#Mann= 5 ,-1 , 0
    4129     .08       0    4945     .04       0  4967.1    .015       0
  5031.9     .04       0    5040     .08       0
#XS Ineff= 2 , 0
       0    4832      65    5178       0      65
Permanent Ineff=
       F       F
Bank Sta=4967.1,5031.9
XS Rating Curve= 0
Exp/Cntr=.5,.3

Type RM Length L Ch R = 1 ,1598.5  ,35,35.4,36
BEGIN DESCRIPTION:
MKT RR - XS 2
END DESCRIPTION:
XS GIS Cut Line= 5
 3090443.586660613866004.2902877      3090457.26     13865977.84
      3090923.11     13865076.68      3090928.21     13864654.11
  3090928.56933413864624.3367098
#Sta/Elev= 30
  4099.1   71.81  4128.6   67.71  4358.6   66.01  4398.6   66.51  4468.6   64.51
  4600.6   64.48  4638.6   63.51  4768.6   65.01  4838.6   60.71  4888.6   60.01
  4908.6   57.51  4938.8   62.05  4946.9   63.27  4958.8   59.69  4969.1   58.51
  4989.5    48.6  4990.5   44.59  5009.4   44.53  5010.3   48.56  5012.5   50.11
  5031.1    58.7  5040.3   58.52  5048.9   59.73  5052.5   59.78  5058.6   62.21
  5173.6   63.33    5263   63.11    5473   66.71    5523   66.11  5595.7   68.51
#Mann= 7 ,-1 , 0
  4099.1     .08       0  4600.6     .08       0  4938.8     .04       0
  4969.1    .015       0  5031.1     .04       0  5048.9     .12       0
  5173.6     .08       0
#XS Ineff= 2 , 0
       0    4932      72    5078       0      72
Permanent Ineff=
       F       F
Bank Sta=4969.1,5031.1
XS Rating Curve= 0
Exp/Cntr=.5,.3

Type RM Length L Ch R = 3 ,1567.2  ,,,
BEGIN DESCRIPTION:
CR&RR(MKT RR)
Structure ID: E115-00-00-02
END DESCRIPTION:
Bridge Culvert--1,0,-1,-1, 0
Deck Dist Width WeirC Skew NumUp NumDn MinLoCord MaxHiCord MaxSubmerge Is_Ogee
10,15,2.6,0, 36, 36, , , .95, 0, ,,,
  4099.1  4941.7 4941.81  4941.9  4942.2  4946.9  4956.8  4958.8  4958.9  4969.1
  4970.2    4978  4984.1  4989.5  4990.5  4998.1  4998.3    5002  5009.4  5010.3
  5012.5  5026.3  5031.1  5035.5  5040.3  5045.6  5045.7  5048.9  5052.5  5058.6
 5067.19  5067.3  5067.4  5067.6  5069.3  5595.7
      72   71.98   71.97   71.96   71.93   71.96   72.02   72.03   72.03    72.1
    72.1   72.15   72.16   72.16   72.17   72.18   72.18   72.18   72.18   72.18
   72.17   72.17   72.16   72.16   72.15   72.14   72.14   72.13   72.13   72.12
    72.1    72.1   72.09   72.07   72.07      71
           62.48   62.49   69.96   69.93   69.96   70.02   70.03   70.03    70.1
    70.1   70.15   70.16   70.16   70.17   70.18   70.18   70.18   70.18   70.18
   70.17   70.17   70.16   70.16   70.15   70.14   70.14   70.13   70.13   70.12
    70.1   62.27   62.27   62.27   62.28
  4099.1  4941.7 4941.81  4941.9  4942.2  4946.9  4956.8  4958.8  4958.9  4969.1
  4970.2    4978  4984.1  4989.5  4990.5  4998.1  4998.3    5002  5009.4  5010.3
  5012.5  5026.3  5031.1  5035.5  5040.3  5045.6  5045.7  5048.9  5052.5  5058.6
 5067.19  5067.3  5067.4  5067.6  5069.3  5595.7
      72   71.98   71.97   71.96   71.93   71.96   72.02   72.03   72.03    72.1
    72.1   72.15   72.16   72.16   72.17   72.18   72.18   72.18   72.18   72.18
   72.17   72.17   72.16   72.16   72.15   72.14   72.14   72.13   72.13   72.12
    72.1    72.1   72.09   72.07   72.07      71
           62.48   62.49   69.96   69.93   69.96   70.02   70.03   70.03    70.1
    70.1   70.15   70.16   70.16   70.17   70.18   70.18   70.18   70.18   70.18
   70.17   70.17   70.16   70.16   70.15   70.14   70.14   70.13   70.13   70.12
    70.1   62.27   62.27   62.27   62.28
Pier Skew, UpSta & Num, DnSta & Num=  ,4956.8, 2 ,4956.8, 2 , 0 , 0 , 0 ,,
       1       1
   59.01   71.02
       1       1
   59.01   71.02
Pier Skew, UpSta & Num, DnSta & Num=  ,4970.2, 2 ,4970.2, 2 , 0 , 0 , 0 ,,
       1       1
   56.49    71.1
       1       1
   56.49    71.1
Pier Skew, UpSta & Num, DnSta & Num=  ,4984.1, 2 ,4984.1, 2 , 0 , 0 , 0 ,,
       1       1
    49.7   71.16
       1       1
    49.7   71.16
Pier Skew, UpSta & Num, DnSta & Num=  ,4998.1, 2 ,4998.1, 2 , 0 , 0 , 0 ,,
       1       1
   43.55   71.18
       1       1
   43.55   71.18
Pier Skew, UpSta & Num, DnSta & Num=  ,5012.5, 2 ,5012.5, 2 , 0 , 0 , 0 ,,
       1       1
   48.75   71.17
       1       1
   48.75   71.17
Pier Skew, UpSta & Num, DnSta & Num=  ,5026.3, 2 ,5026.3, 2 , 0 , 0 , 0 ,,
       1       1
   55.03   71.17
       1       1
   55.03   71.17
Pier Skew, UpSta & Num, DnSta & Num=  ,5040.3, 2 ,5040.3, 2 , 0 , 0 , 0 ,,
       1       1
   57.52   71.15
       1       1
   57.52   71.15
Pier Skew, UpSta & Num, DnSta & Num=  ,5052.5, 2 ,5052.5, 2 , 0 , 0 , 0 ,,
       1       1
   58.76   71.13
       1       1
   58.76   71.13
BR Coef= 1 , 1 , 1 ,2.5, 0 ,,,.8,0,2,0,
WSPro=,,,, 1 ,,,, 0 ,,,, 0 ,,,,-1 ,-1 ,-1 , 0 , 0 , 0 , 0 , 0
BC Design=,, 0 ,, 0 ,,,,,,
BC HTab HWMax=71.81