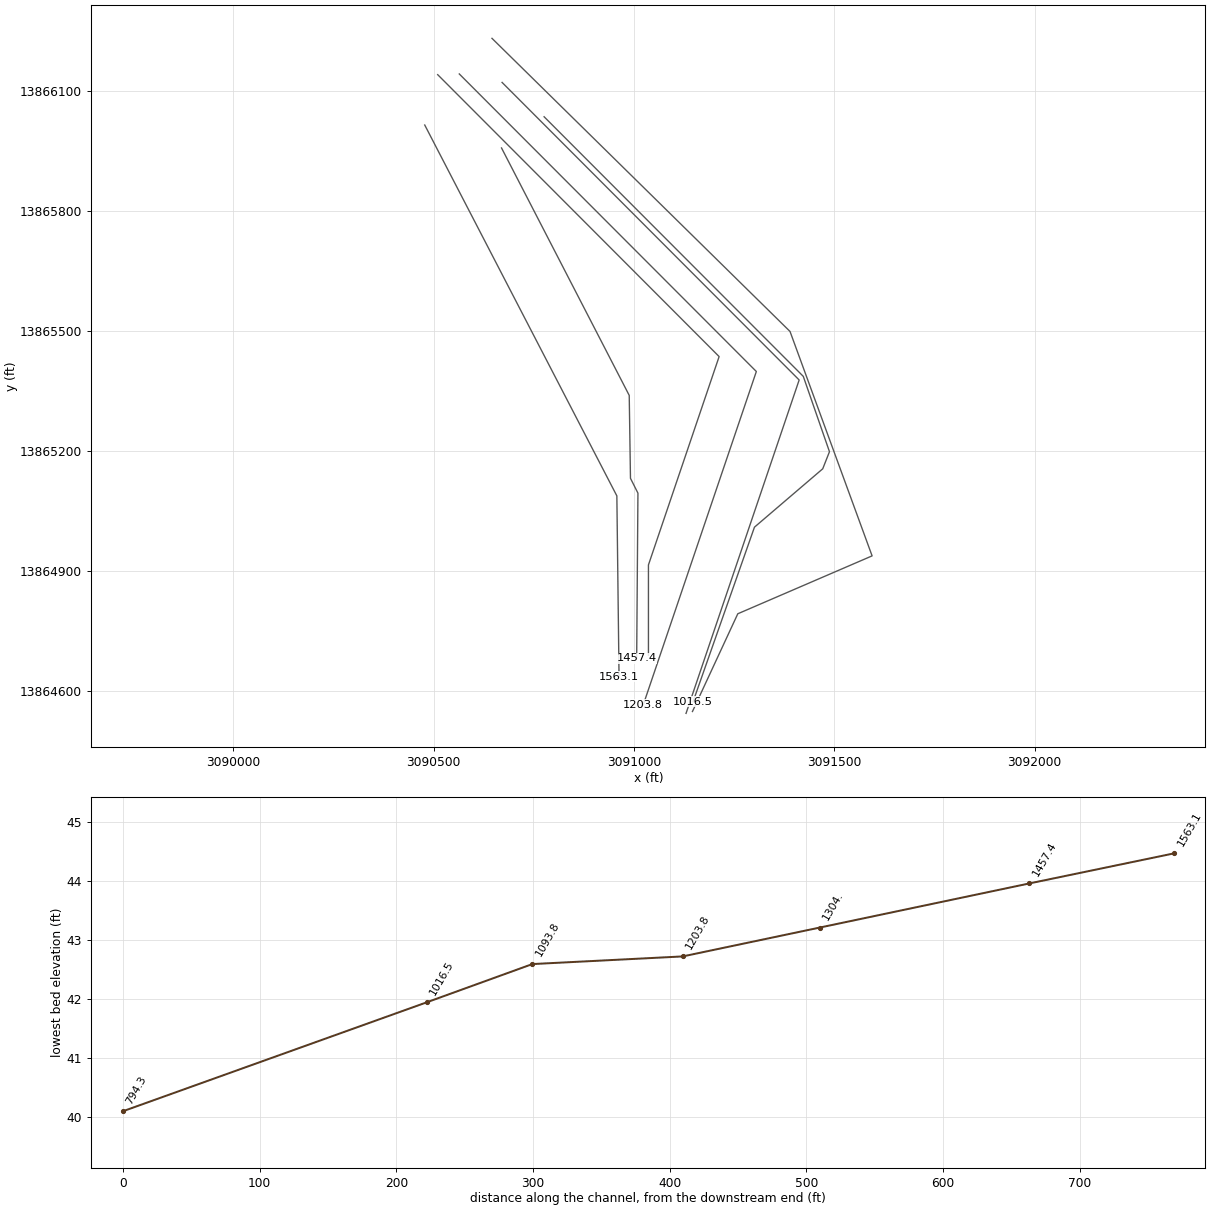
HEC-RAS study E115-00-00.prj: E115-00-00

--- E115-00-00.g01 (geometry) --- (continued)

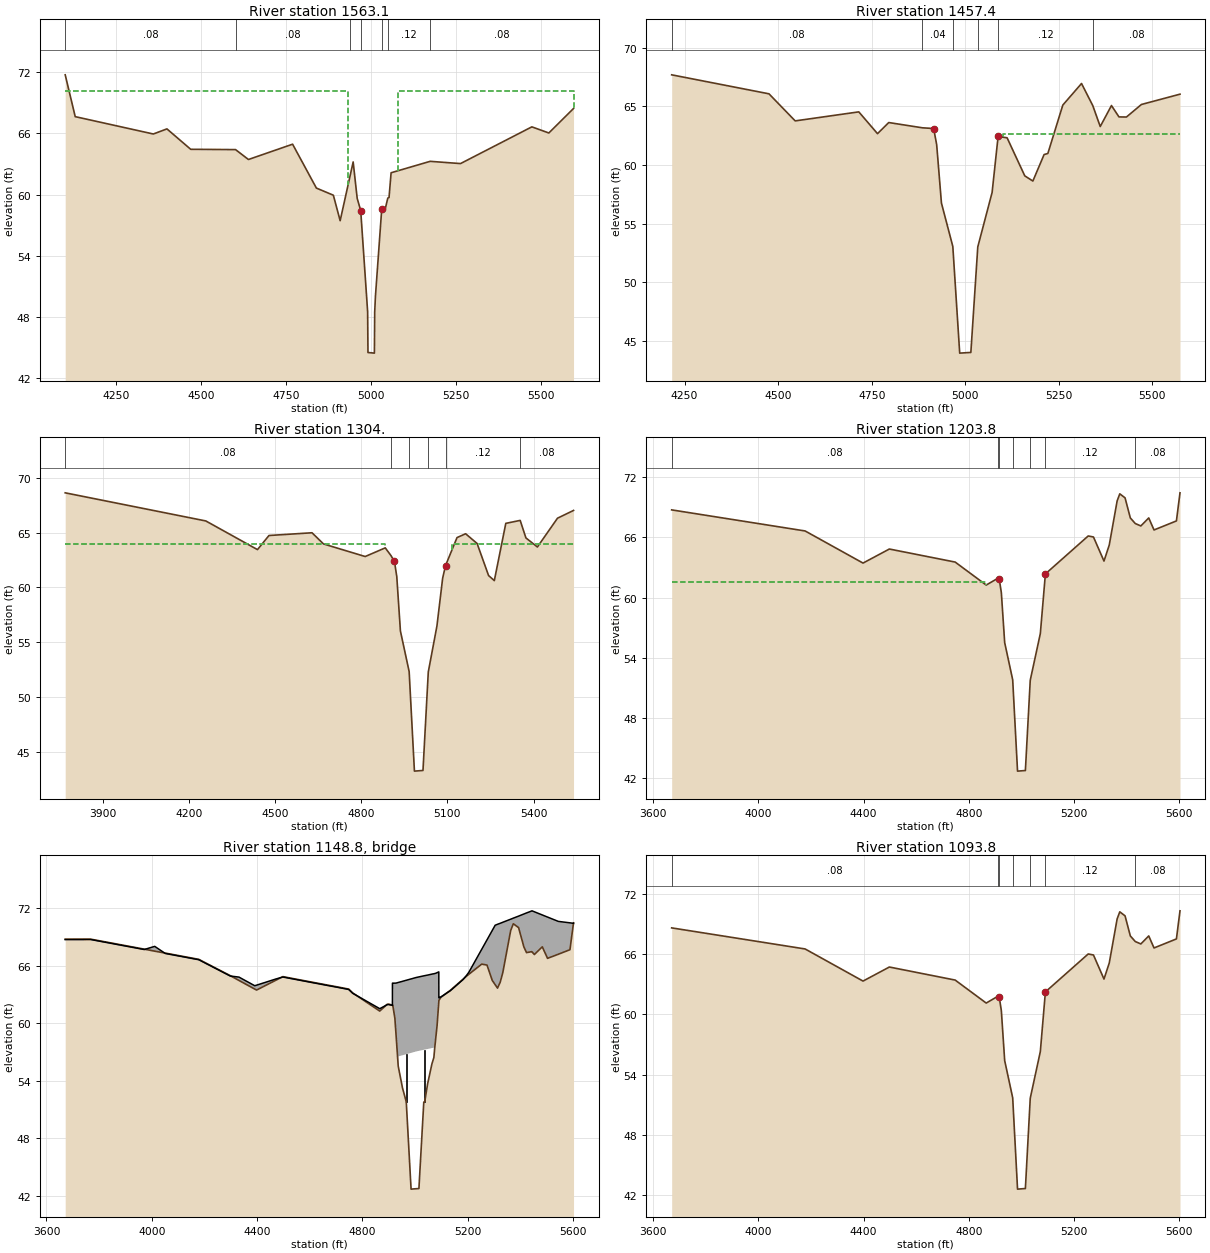
Type RM Length L Ch R = 1 ,1563.1  ,125.3,105.7,85.3
BEGIN DESCRIPTION:
MKT RR - XS 2
END DESCRIPTION:
XS GIS Cut Line= 5
 3090477.977934813866014.7414012      3090488.39      13865994.6
       3090957.5     13865087.14      3090962.68     13864657.46
   3090962.9533213864634.7881575
#Sta/Elev= 30
  4099.1   71.75  4128.6   67.65  4358.6   65.95  4398.6   66.45  4468.6   64.45
  4600.6   64.42  4638.6   63.45  4768.6   64.95  4838.6   60.65  4888.6   59.95
  4908.6   57.45  4938.8   61.99  4946.9   63.21  4958.8   59.63  4969.1   58.45
  4989.5   48.54  4990.5   44.53  5009.4   44.47  5010.3    48.5  5012.5   50.05
  5031.1   58.64  5040.3   58.46  5048.9   59.67  5052.5   59.72  5058.6   62.15
  5173.6   63.27    5263   63.05    5473   66.65    5523   66.05  5595.7   68.45
#Mann= 7 ,-1 , 0
  4099.1     .08       0  4600.6     .08       0  4938.8     .04       0
  4969.1    .015       0  5031.1     .04       0  5048.9     .12       0
  5173.6     .08       0
#XS Ineff= 2 , 0
       0    4932   70.18    5078       0   70.18
Permanent Ineff=
       F       F
Bank Sta=4969.1,5031.1
XS Rating Curve= 0
Exp/Cntr=.5,.3

Type RM Length L Ch R = 1 ,1457.4  ,173.1,153.4,137.3
BEGIN DESCRIPTION:
MKT RR - XS 1
Interplotated channel, LIDAR overbanks
END DESCRIPTION:
XS GIS Cut Line= 5
      3090669.64     13865957.38      3090988.39     13865338.46
      3090991.48     13865131.12      3091010.11     13865094.02
      3091006.96     13864680.86
#Sta/Elev= 30
  4215.5    67.7  4475.5   66.08  4545.5   63.77  4715.5   64.54  4765.5   62.68
  4795.5   63.63  4885.5   63.18  4915.5   63.12  4923.6   61.74  4936.3   56.76
  4966.7   53.06  4985.1   43.96  5014.9   44.02  5033.4   53.02  5071.7   57.67
  5087.7   62.44  5111.7   62.33    5159   59.08  5180.6   58.64  5210.6    60.9
  5220.6   60.99  5260.6   65.12  5310.6   66.96  5340.6   65.08  5360.6   63.29
  5390.6   65.08  5410.6   64.11  5430.6    64.1  5470.6   65.17  5573.7   66.05
#Mann= 6 ,-1 , 0
  4215.5     .08       0  4885.5     .04       0  4966.7    .015       0
  5033.4     .04       0  5087.7     .12       0  5340.6     .08       0
#XS Ineff= 2 , 0
       0                  5101.7       0   62.65
Permanent Ineff=
       F       F
Bank Sta=4915.5,5087.7
XS Rating Curve= 0
Exp/Cntr=.3,.1

Type RM Length L Ch R = 1 ,1304.   ,100,100.2,100.9
BEGIN DESCRIPTION:
WATONGA - XS 4
Interplotated channel, LIDAR overbanks
END DESCRIPTION:
XS GIS Cut Line= 4
      3090510.32     13866140.68      3091212.77     13865435.59
      3091036.35      13864914.5      3091036.36     13864688.59
#Sta/Elev= 30
  3768.2   68.64  4258.2   66.07  4438.2   63.45  4478.2   64.74  4628.2   64.99
  4668.2   63.97  4813.5   62.82  4883.5   63.61  4903.5    62.9  4915.5   62.37
  4923.6   60.99  4936.3   56.01  4966.7   52.31  4985.1   43.21  5014.9   43.27
  5033.4   52.27  5063.5   56.47  5083.5   60.85  5093.5   61.99  5133.5   64.55
  5163.5    64.9  5203.5   64.01  5243.5   61.08  5263.5   60.62  5303.5   65.85
  5353.6   66.12  5373.6   64.52  5413.6   63.69  5483.6   66.32  5539.5   67.03
#Mann= 6 ,-1 , 0
  3768.2     .08       0  4903.5     .04       0  4966.7    .015       0
  5033.4     .04       0  5093.5     .12       0  5353.6     .08       0
#XS Ineff= 2 , 0
        4883.685 63.95675115.499         63.9567
Permanent Ineff=
       F       F
Bank Sta=4915.5,5093.5
XS Rating Curve= 0
Exp/Cntr=.5,.3

Type RM Length L Ch R = 1 ,1203.8  ,108.8,110,110.5
BEGIN DESCRIPTION:
WATONGA - XS 3
END DESCRIPTION:
XS GIS Cut Line= 5
 3090564.215583413866142.4803737       3090603.2     13866103.35
      3091305.66     13865398.26      3091041.05      13864616.7
 3091023.336754913864564.3816301
#Sta/Elev= 30
  3671.3   68.75  4178.2   66.65  4398.2   63.45  4498.2   64.85  4748.2   63.55
  4866.1   61.26  4909.4   61.92  4915.5   61.88  4923.6    60.5  4936.3   55.52
  4966.7   51.82  4985.1   42.72  5014.9   42.78  5033.4   51.78  5071.7   56.43
  5090.9   62.37  5253.5   66.15  5273.5   66.05  5313.5   63.65  5333.5   65.25
  5363.5   69.65  5373.5   70.35  5393.5   69.95  5413.5   67.95  5432.4   67.39
  5453.5   67.15  5483.5   67.95  5503.5   66.75  5588.6   67.65  5602.2   70.45
#Mann= 7 ,-1 , 0
  3671.3     .08       0  4909.4     .04       0  4915.5     .04       0
  4966.7    .015       0  5033.4     .04       0  5090.9     .12       0
  5432.4     .08       0
#XS Ineff= 2 , 0
       0    4865   61.55    5130       0   61.55
Permanent Ineff=
       F       F
Bank Sta=4915.5,5090.9
XS Rating Curve= 0
Exp/Cntr=.5,.3

Type RM Length L Ch R = 3 ,1148.8  ,,,
BEGIN DESCRIPTION:
WATONGA BLVD
Structure ID: E115-00-00-01
END DESCRIPTION:
Bridge Culvert--1,0,-1,-1, 0
Deck Dist Width WeirC Skew NumUp NumDn MinLoCord MaxHiCord MaxSubmerge Is_Ogee
10,90,2.6,0, 85, 85, , , .95, 0, ,,,
  3671.3  3768.2  3971.3  4011.3  4051.3  4178.2  4181.3  4221.3  4298.2  4331.3
  4391.3  4398.2  4471.3  4498.2  4501.3  4601.3  4661.3  4704.5  4748.2  4763.5
  4866.1  4894.5  4900.5  4904.5  4909.4 4914.19  4914.3 4914.51  4915.5  4923.6
  4926.8  4928.2 4930.01  4930.1  4936.3  4936.4  4952.5  4966.7 4966.81  4985.1
  4999.5  5003.4  5014.9  5033.4  5036.7  5048.1  5064.2  5071.7  5071.8  5075.2
 5077.89    5078  5078.1  5083.8 5090.39  5090.5 5090.61  5090.9  5098.7  5134.1
  5140.5  5182.5  5194.5  5204.5  5253.5  5273.5  5293.5  5304.5  5313.5  5323.5
  5333.5  5363.5  5373.5  5393.5  5413.5  5423.5  5432.4  5443.5  5444.5  5453.5
  5483.5  5503.5  5544.5  5588.6  5602.2
    68.7   68.71   67.67      68   67.26   66.61   66.57      66   64.91    64.8
    63.9   63.96    64.6   64.81   64.79   64.27   63.96   63.74   63.51   63.11
   61.51   61.93   61.94   61.91   61.88   61.85   64.17   64.17   64.17   64.17
   64.17   64.18   64.19   64.19   64.24   64.24   64.36   64.47   64.47   64.61
   64.72   64.75   64.82   64.93   64.95   65.01   65.11   65.15   65.15   65.17
   65.19   65.19   65.19   65.26   65.34   65.34   62.64   62.64   62.74   63.38
   63.53   64.54   64.93    65.3    67.7   68.68   69.66    70.2    70.3    70.4
   70.51   70.83   70.94   71.15   71.37   71.48   71.57   71.69    71.7    71.6
   71.27   71.05    70.6   70.45    70.4
                                                                                
                                                                                
                                                                                
                                           56.54   56.66   56.77   56.77   56.91
   57.02   57.05   57.12   57.23   57.25   57.31   57.41   57.45
                                                                                
                                                                                
                                                                                
                                        
  3671.3  3768.2  3971.3  4011.3  4051.3  4178.2  4181.3  4221.3  4298.2  4331.3
  4391.3  4398.2  4471.3  4498.2  4501.3  4601.3  4661.3  4704.5  4748.2  4763.5
  4866.1  4894.5  4900.5  4904.5  4909.4 4914.19  4914.3 4914.51  4915.5  4923.6
  4926.8  4928.2 4930.01  4930.1  4936.3  4936.4  4952.5  4966.7 4966.81  4985.1
  4999.5  5003.4  5014.9  5033.4  5036.7  5048.1  5064.2  5071.7  5071.8  5075.2
 5077.89    5078  5078.1  5083.8 5090.39  5090.5 5090.61  5090.9  5098.7  5134.1
  5140.5  5182.5  5194.5  5204.5  5253.5  5273.5  5293.5  5304.5  5313.5  5323.5
  5333.5  5363.5  5373.5  5393.5  5413.5  5423.5  5432.4  5443.5  5444.5  5453.5
  5483.5  5503.5  5544.5  5588.6  5602.2
    68.7   68.71   67.67      68   67.26   66.61   66.57      66   64.91    64.8
    63.9   63.96    64.6   64.81   64.79   64.27   63.96   63.74   63.51   63.11
   61.51   61.93   61.94   61.91   61.88   61.85   64.17   64.17   64.17   64.17
   64.17   64.18   64.19   64.19   64.24   64.24   64.36   64.47   64.47   64.61
   64.72   64.75   64.82   64.93   64.95   65.01   65.11   65.15   65.15   65.17
   65.19   65.19   65.19   65.26   65.34   65.34   62.64   62.64   62.74   63.38
   63.53   64.54   64.93    65.3    67.7   68.68   69.66    70.2    70.3    70.4
   70.51   70.83   70.94   71.15   71.37   71.48   71.57   71.69    71.7    71.6
   71.27   71.05    70.6   70.45    70.4
                                                                                
                                                                                
                                                                                
                                           56.54   56.66   56.77   56.77   56.91
   57.02   57.05   57.12   57.23   57.25   57.31   57.41   57.45
                                                                                
                                                                                
                                                                                
                                        
Pier Skew, UpSta & Num, DnSta & Num=  ,4966.8, 2 ,4966.8, 2 , 0 , 0 , 0 ,,
     2.5     2.5
   50.15   57.78
     2.5     2.5
   50.15   57.78
Pier Skew, UpSta & Num, DnSta & Num=  ,5036.7, 2 ,5036.7, 2 , 0 , 0 , 0 ,,
     2.5     2.5
   50.73   58.26
     2.5     2.5
   50.73   58.26
BR Coef= 1 , 1 , 1 ,1.05, 0 ,,,.8,0,1.2,1,
WSPro=,,,, 1 ,,,, 0 ,,,, 0 ,,,,-1 ,-1 ,-1 , 0 , 0 , 0 , 0 , 0
BR U #Sta/Elev= 85
  3671.3   68.75  3768.2   68.75  3971.3   67.71  4011.3    67.5  4051.3    67.3
  4178.2   66.65  4181.3   66.61  4221.3   66.04  4298.2   64.95  4331.3   64.45
  4391.3   63.55  4398.2   63.45  4471.3   64.47  4498.2   64.85  4501.3   64.83
  4601.3   64.31  4661.3      64  4704.5   63.78  4748.2   63.55  4763.5   63.15
  4866.1   61.26  4894.5   61.97  4900.5   61.98  4904.5   61.95  4909.4   61.92
 4914.19   61.89  4914.3   61.89 4914.51   61.89  4915.5   61.88  4923.6    60.5
  4926.8   59.25  4928.2   58.71 4930.01      58  4930.1   57.96  4936.3   55.52
  4936.4   55.51  4952.5   53.26  4966.7   51.82 4966.81   51.82  4985.1   42.72
  4999.5   42.75  5003.4   42.76  5014.9   42.78  5033.4   51.78  5036.7   51.78
  5048.1   53.71  5064.2   55.75  5071.7   56.43  5071.8   56.46  5075.2   57.48
 5077.89   58.18    5078   58.21  5078.1   58.24  5083.8   59.72 5090.39   62.18
  5090.5   62.22 5090.61   62.26  5090.9   62.37  5098.7    62.7  5134.1   63.42
  5140.5   63.57  5182.5   64.58  5194.5   64.87  5204.5   65.09  5253.5   66.15
  5273.5   66.05  5293.5   64.45  5304.5   64.01  5313.5   63.65  5323.5   64.25
  5333.5   65.25  5363.5   69.65  5373.5   70.35  5393.5   69.95  5413.5   67.95
  5423.5   67.35  5432.4   67.39  5443.5   67.45  5444.5   67.42  5453.5   67.15
  5483.5   67.95  5503.5   66.75  5544.5   67.18  5588.6   67.65  5602.2   70.45
BR U #Mann= 6
  3671.3     .08  4909.4     .04  4966.7    .015  5033.4     .04  5090.9     .12
  5432.4     .08
BR D #Sta/Elev= 85
  3671.3   68.75  3768.2   68.75  3971.3   67.71  4011.3    67.5  4051.3    67.3
  4178.2   66.65  4181.3   66.61  4221.3   66.04  4298.2   64.95  4331.3   64.45
  4391.3   63.55  4398.2   63.45  4471.3   64.47  4498.2   64.85  4501.3   64.83
  4601.3   64.31  4661.3      64  4704.5   63.78  4748.2   63.55  4763.5   63.15
  4866.1   61.26  4894.5   61.97  4900.5   61.98  4904.5   61.95  4909.4   61.92
 4914.19   61.89  4914.3   61.89 4914.51   61.89  4915.5   61.75  4923.6   60.37
  4926.8   59.12  4928.2   58.58 4930.01   57.87  4930.1   57.83  4936.3   55.39
  4936.4   55.38  4952.5   53.13  4966.7   51.69 4966.81   51.69  4985.1   42.59
  4999.5   42.62  5003.4   42.63  5014.9   42.65  5033.4   51.65  5036.7   51.65
  5048.1   53.58  5064.2   55.62  5071.7    56.3  5071.8   56.33  5075.2   57.35
 5077.89   58.05    5078   58.08  5078.1   58.11  5083.8   59.59 5090.39   62.05
  5090.5   62.09 5090.61   62.13  5090.9   62.24  5098.7    62.7  5134.1   63.42
  5140.5   63.57  5182.5   64.58  5194.5   64.87  5204.5   65.09  5253.5   66.15
  5273.5   66.05  5293.5   64.45  5304.5   64.01  5313.5   63.65  5323.5   64.25
  5333.5   65.25  5363.5   69.65  5373.5   70.35  5393.5   69.95  5413.5   67.95
  5423.5   67.35  5432.4   67.39  5443.5   67.45  5444.5   67.42  5453.5   67.15
  5483.5   67.95  5503.5   66.75  5544.5   67.18  5588.6   67.65  5602.2   70.45
BR D #Mann= 6
  3671.3     .08  4909.4     .04  4966.7    .015  5033.4     .04  5090.9     .12
  5432.4     .08
BC Design=,, 0 ,, 0 ,,,,,,
BC HTab HWMax=70.45

Type RM Length L Ch R = 1 ,1093.8  ,109.2,77.3,42.2
BEGIN DESCRIPTION:
WATONGA - XS 2
END DESCRIPTION:
XS GIS Cut Line= 5
 3090671.069197713866121.2680179      3090696.93     13866095.31
      3091412.51     13865377.04      3091141.94     13864577.87
 3091130.189691113864543.1636601
#Sta/Elev= 30
  3671.3   68.62  4178.2   66.52  4398.2   63.32  4498.2   64.72  4748.2   63.42
  4866.1   61.13  4909.4   61.79  4915.5   61.75  4923.6   60.37  4936.3   55.39
  4966.7   51.69  4985.1   42.59  5014.9   42.65  5033.4   51.65  5071.7    56.3
  5090.9   62.24  5253.5   66.02  5273.5   65.92  5313.5   63.52  5333.5   65.12
  5363.5   69.52  5373.5   70.22  5393.5   69.82  5413.5   67.82  5432.4   67.26
  5453.5   67.02  5483.5   67.82  5503.5   66.62  5588.6   67.52  5602.2   70.32
#Mann= 7 ,-1 , 0
  3671.3     .08       0  4909.4     .04       0  4915.5     .04       0
  4966.7    .015       0  5033.4     .04       0  5090.9     .12       0
  5432.4     .08       0
#XS Ineff= 2 , 0
       0    4865      61    5130       0      61
Permanent Ineff=
       F       F
Bank Sta=4915.5,5090.9
XS Rating Curve= 0
Exp/Cntr=.5,.3

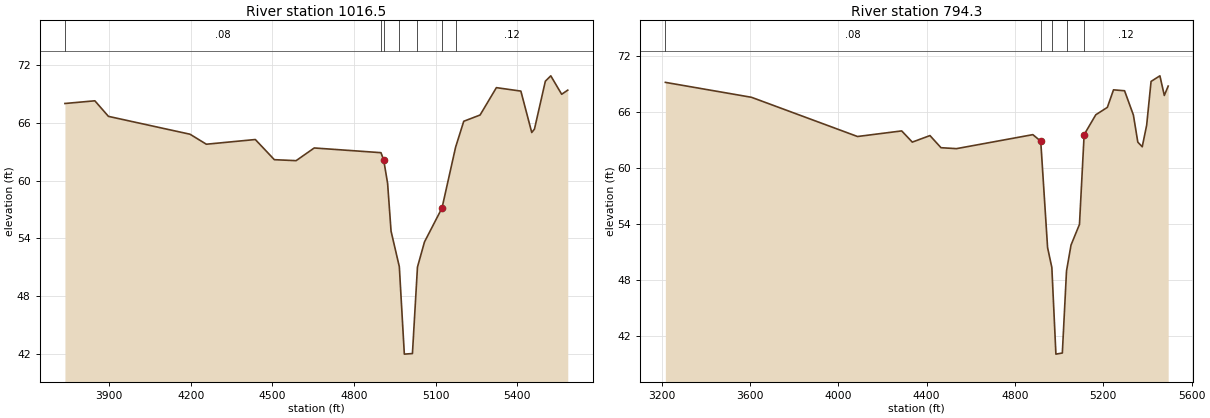
Type RM Length L Ch R = 1 ,1016.5  ,241.6,222.2,194.4
BEGIN DESCRIPTION:
WATONGA - XS 1
Interplotated channel, LIDAR overbanks
END DESCRIPTION:
XS GIS Cut Line= 6
      3090775.92     13866035.41      3091422.83     13865386.07
      3091488.17     13865197.66      3091471.34     13865154.86
      3091300.94     13865008.88      3091147.76     13864572.54
#Sta/Elev= 30
  3737.2   68.03  3847.2   68.31  3897.2   66.69  4197.2   64.83  4257.2   63.79
  4437.2   64.28  4507.2   62.18  4587.2   62.08  4653.8    63.4  4899.2   62.91
  4909.2   62.15  4923.6   59.72  4936.3   54.74  4966.7   51.04  4985.1   41.94
  5014.9      42  5033.4      51  5059.2   53.62  5123.6   57.15  5173.6   63.48
  5203.6   66.18  5263.6   66.83  5323.6   69.68  5413.6   69.32  5453.6   65.01
  5463.6   65.37  5503.6   70.35  5523.6   70.91  5563.6   68.99    5586   69.42
#Mann= 7 ,-1 , 0
  3737.2     .08       0  4899.2     .04       0  4909.2     .04       0
  4966.7    .015       0  5033.4     .04       0  5123.6     .04       0
  5173.6     .12       0
Bank Sta=4909.2,5123.6
XS Rating Curve= 0
Exp/Cntr=.3,.1

Type RM Length L Ch R = 1 ,794.3   ,0,0,0
BEGIN DESCRIPTION:
Cross Section x01
Located At: DS WATONGA BLVD
END DESCRIPTION:
XS GIS Cut Line= 6
 3090645.8124057 13866231.553398      3090661.35     13866216.24
      3091389.73     13865498.37      3091594.57     13864937.09
      3091259.36     13864792.29 3091146.205846813864547.8426443
#Sta/Elev= 30
  3217.2    69.2  3607.2    67.6  4087.2    63.4  4287.2      64  4335.2    62.8
  4415.2    63.5  4465.2    62.2  4535.2    62.1    4881    63.6  4916.7    62.9
  4947.7    51.5    4967   49.37  4985.4   40.09  5014.5   40.21  5033.4      49
  5053.8   51.77  5092.1   53.99  5113.2    63.6    5166   65.73  5218.3   66.52
  5246.2    68.4  5296.2    68.3  5336.2    65.7  5356.2    62.8  5376.2    62.3
  5396.2    64.6  5416.2    69.3  5456.2    69.9  5476.2    67.8  5493.7    68.8
#Mann= 5 ,-1 , 0
  3217.2     .08       0  4916.7     .04       0    4967    .015       0
  5033.4     .04       0  5113.2     .12       0
Bank Sta=4916.7,5113.2
XS Rating Curve= 0
Exp/Cntr=.3,.1

Chan Stop Cuts=-1